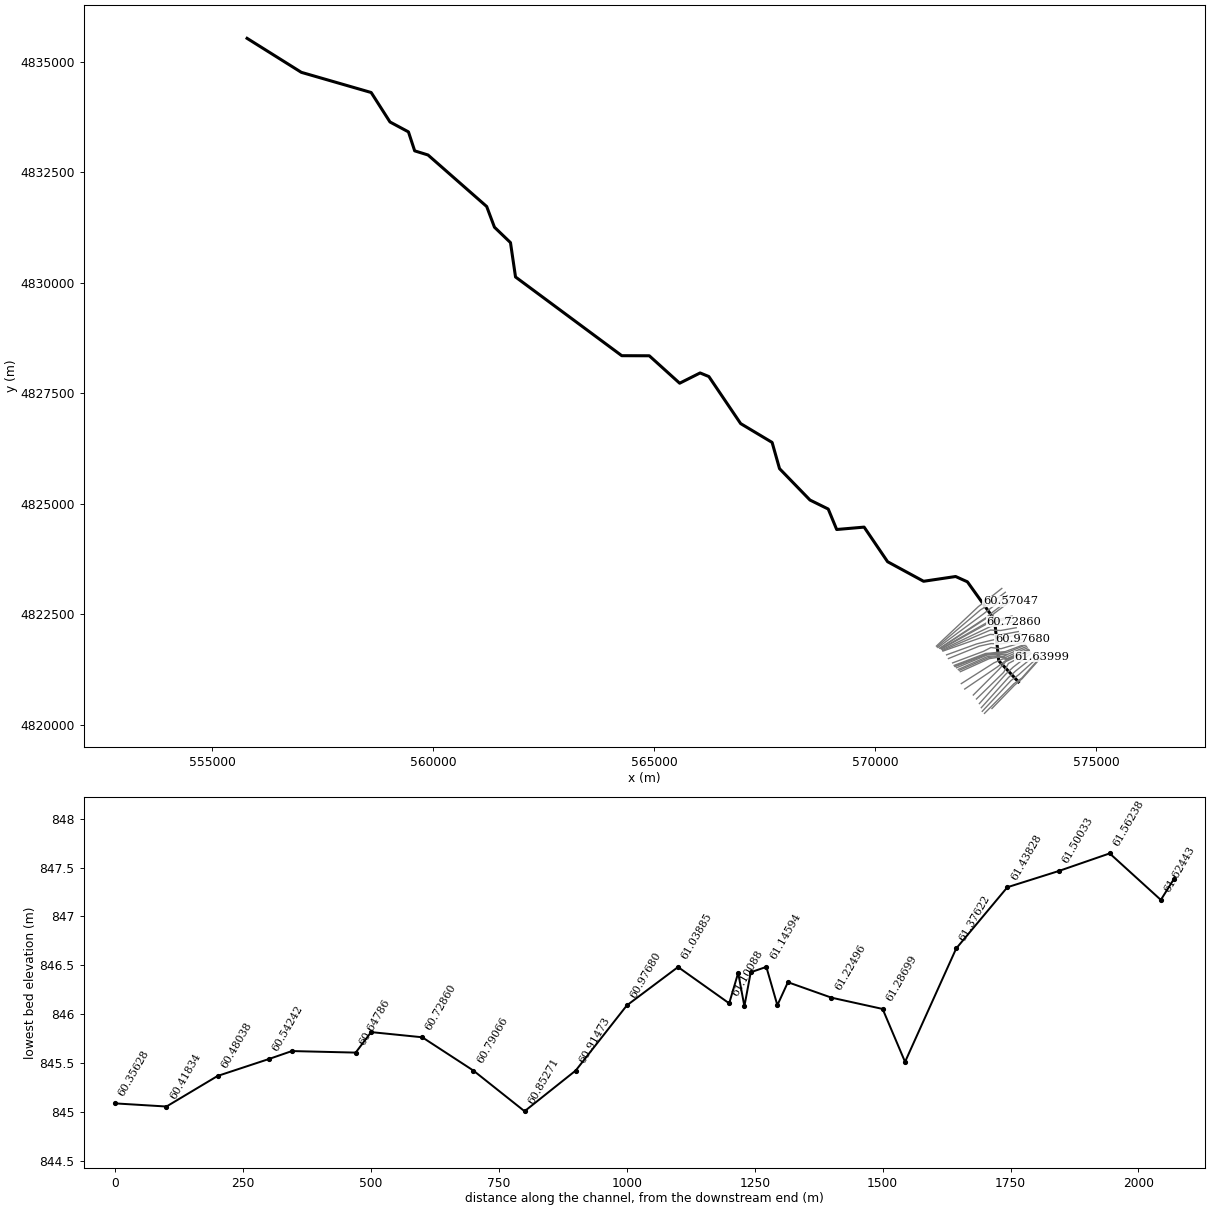
--- Boise2.prj (project) ---

Proj Title=BoiseRiver_All_reaches
Current Plan=p01
Default Exp/Contr=0.3,0.1
SI Units
Geom File=g01
Flow File=f02
Plan File=p01
Y Axis Title=Elevation
X Axis Title(PF)=Main Channel Distance
X Axis Title(XS)=Station
BEGIN DESCRIPTION:
END DESCRIPTION:
DSS File=dss
DSS Export Rating Curves= 0
DSS Export Rating Curve Sorted= 0
DSS Export Volume Flow Curves= 0
DXF OffsetX= 0
DXF OffsetY= 0
DXF ScaleX= 1
DXF ScaleY= 10

--- Boise2.p01 (plan) ---

Plan Title=Q_Without_Flooding
Program Version=4.00
Short Identifier=Q_Without_Floodi
Geom File=g01
Flow File=f02
Subcritical Flow
K Sum by GR= 0
Std Step Tol= 0.0001
Critical Tol= 0.0001
Num of Std Step Trials= 40
Max Error Tol= 0.1
Flow Tol Ratio= 0.0001
Split Flow NTrial= 60
Split Flow Tol= 0.003
Split Flow Ratio= 0.0001
Log Output Level= 0
Friction Slope Method= 1
Unsteady Friction Slope Method= 2
Unsteady Bridges Friction Slope Method= 1
Parabolic Critical Depth
Global Vel Dist= 0 , 0 , 0
Global Log Level= 0
CheckData=True
Encroach Param=-1 ,0,0, 0
Computation Interval=1HOUR
Output Interval=1HOUR
Run HTab= 0
Run UNet= 0
Run PostProcess= 0
Run WQNet= 0
UNET Theta= 1
UNET Theta Warmup= 1
UNET ZTol= 0.006
UNET ZSATol= 0.015
UNET MxIter= 20
UNET MaxInSteps= 0
UNET DtIC= 0
UNET DtMin= 0
UNET MaxCRTS= 20
UNET WFStab= 2
UNET SFStab= 1
UNET WFX= 1
UNET SFX= 1
UNET DSS MLevel= 4
UNET DZMax Abort= 30
UNET Convert EG Bridges= 0
UNET Use Existing IB Tables=-1
UNET Froude Reduction=False
UNET Froude Limit= 1
UNET Froude Power= 10
UNET Time Slicing=0,0, 5
Instantaneous Interval=1HOUR
DSS File=dss
Write IC File= 0
Echo Input=False
Echo Output=False
Write Detailed= 0
Detailed Automatic Start=False, 10
WQ ULTIMATE=-1
WQ Max Comp Step=1HOUR
WQ Output Interval=15MIN
WQ Output Selected Increments= 0
WQ Output face flow=0
WQ Output face velocity=0
WQ Output face area=0
WQ Output face dispersion=0
WQ Output cell volume=0
WQ Output cell surface area=0
WQ Output cell continuity=0
WQ Output face conc=0
WQ Output face dconc_dx=0
WQ Output face courant=0
WQ Output face peclet=0
WQ Output face adv mass=0
WQ Output face disp mass=0
WQ Output cell mass=0
WQ Output cell source sink temp=0
WQ Output cell source sink nsm=0
WQ Output MaxMinRange=-1
WQ Daily Max Min Mean=-1
WQ Daily Range=0
WQ Daily Time=0
WQ Create Restart=0
WQ Fixed Restart=0
WQ System Summary=False
Sorting and Armoring Iterations= 10
XS Update Threshold= 0.02
Hydraulics Update Threshold= 0.02
Energy Slope Method= 1
Volume Change Method= 0
XS Weighting Method= 0
Number of US Weighted Cross Sections= 1
Number of DS Weighted Cross Sections= 1
Upstream XS Weight=0.25
Main XS Weight=0.5
Downstream XS Weight=0.25
Number of DS XS's Weighted with US Boundary= 1
Upstream Boundary Weight= 1
Weight of XSs Associated with US Boundary= 0
Number of US XS's Weighted with DS Boundary= 1
Downstream Boundary Weight= 0.5
Weight of XSs Associated with DS Boundary= 0.5
Sediment Output Level= 4
Mass or Volume Output= 0
Output Increment Type= 1
Profile and TS Output Increment= 10
XS Output Flag= 0
XS Output Increment= 10
Disregard all LS=0
Disregard all Conn=0
Disregard all Breaches=0
Disregard all Pumps=0

--- Boise2.f02 (steady flow) ---

Flow Title=Q_Without_Flooding
Program Version=4.00
Number of Profiles= 1
Profile Names=PF 1
River Rch & RM=BoiseRiver,Reach1          ,61.63999
     184
Boundary for River Rch & Prof#=BoiseRiver,Reach1          , 1
Up Type= 0
Dn Type= 2
DSS Import GetInterval= 0
DSS Import GetPeak= 0
DSS Import FillOption= 0

--- Boise2.g01 (geometry) ---

Geom Title=Geometry_21_2-YR_Calibration
Program Version=4.00
BEGIN GEOM DESCRIPTION:
Summary of changes performed on data (using Geometry_13 as base geometry):
1. Calibrated for 100 year flows by changing Manning's n, contraction/expansion coefficients, and levees positions/elevations.
2. Set last 2 XS's ponds to ineffective.
3. Adjusted Brodway Bridge alignment.
END GEOM DESCRIPTION:

River Reach=BoiseRiver      ,Reach1
Reach XY= 30
       573246.53      4820971.58       572800.28      4821449.47
       572706.93      4822376.57       572091.61      4823235.73
       571825.55      4823355.74       571100.42      4823247.91
       570285.71       4823690.5       569754.85      4824473.46
       569133.82      4824419.49       568942.68       4824882.4
        568529.3      4825086.24       567840.32       4825796.8
       567672.68      4826389.89       566960.85      4826815.98
       566241.39      4827880.88       566043.27      4827962.16
       565580.35      4827729.75       564893.28      4828350.78
       564270.34      4828352.68       561866.44      4830133.61
       561752.14      4830911.49       561389.56      4831260.11
       561213.66      4831728.74       559885.87       4832894.6
       559584.25      4832987.95       559443.28      4833417.21
       559025.45      4833641.36       558599.99      4834308.11
       557019.48      4834764.68       555791.63      4835534.08

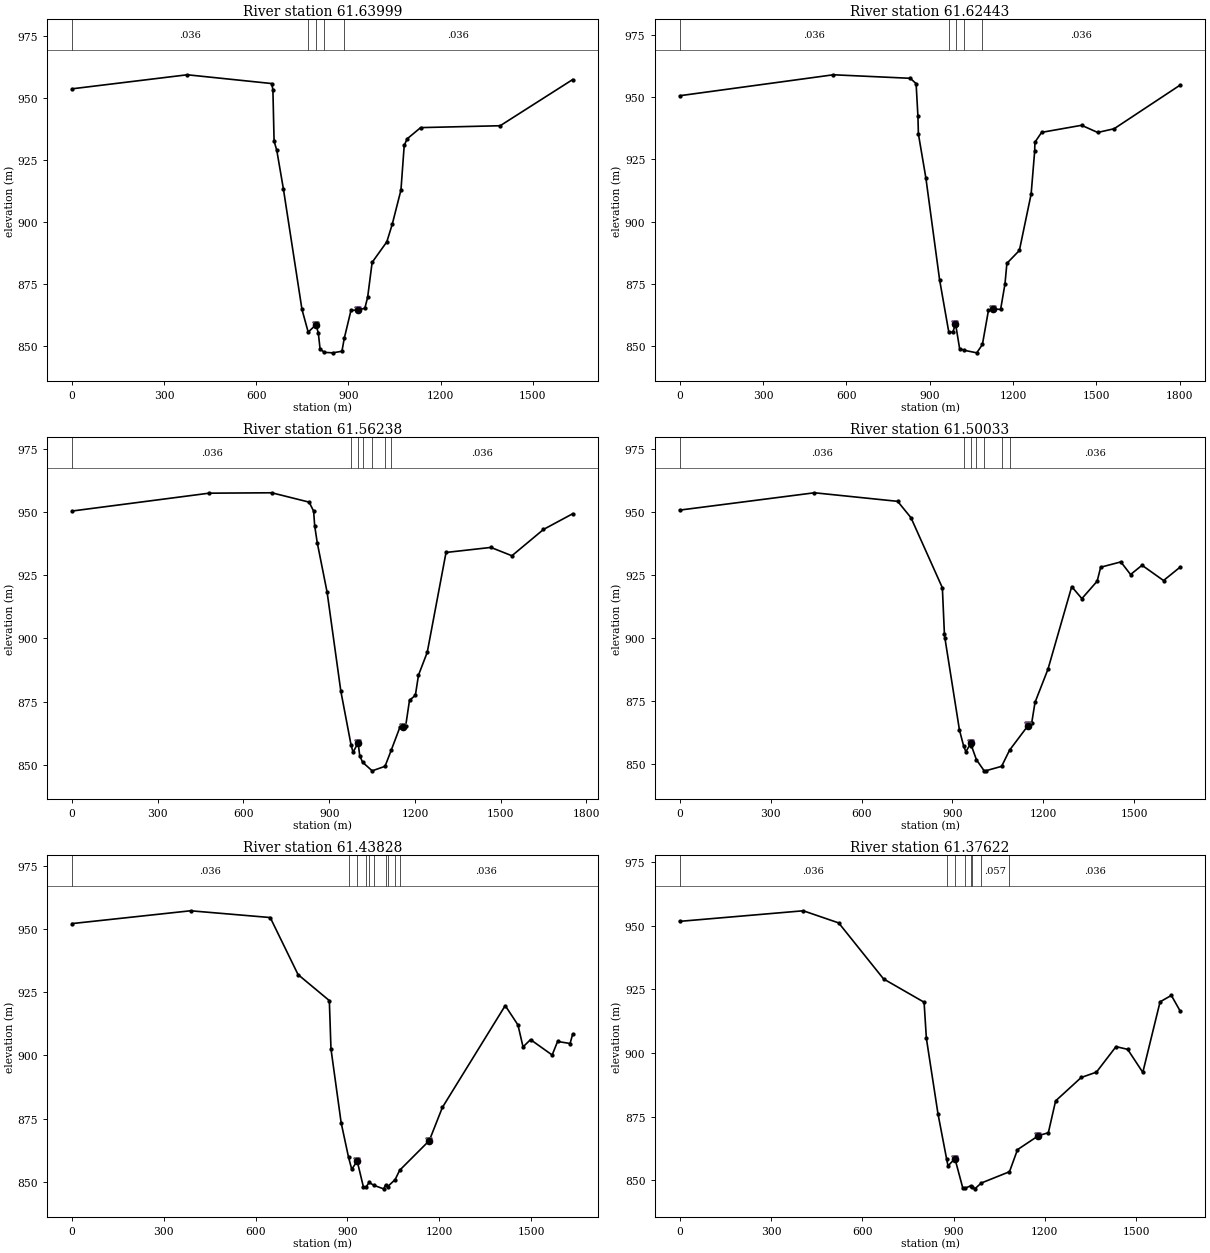
Type RM Length L Ch R = 1 ,61.63999,34.1659,25.0799,20.2189
XS GIS Cut Line= 4
       572647.65      4820368.92       573157.85      4820895.57
       573329.45      4821042.65       573777.17      4821542.36
#Sta/Elev= 30
       0953.7211 375.217959.3781649.9531 955.851654.0551953.4321  657.92 932.656
666.6882928.9429688.1811913.4561748.7311 864.855 768.965855.7238 794.449858.7126
794.5591858.7131802.0471855.2789 807.688 848.915821.2939847.5751848.8702 847.379
878.8232848.0148886.3389853.1589908.3619864.5219929.7894864.5861953.4501865.3431
 962.587869.7971 977.147 883.8161024.928892.07791042.654899.16791071.008912.9659
1081.609 930.921 1091.29 933.5891135.113 938.0971394.053938.85321630.198957.4591
#Mann= 5 ,-1 , 0
       0    .036       0 768.965    .026       0794.5591    .036       0
821.2939    .037       0886.3389    .036       0
Levee=-1,794.449,858.6734,-1,929.7894,864.5927,,
Bank Sta=794.449,929.7894
XS Rating Curve= 0 ,0
Exp/Cntr=0.3,0.1

Type RM Length L Ch R = 1 ,61.62443,100.7879,100.0021,101.528
BEGIN DESCRIPTION:
PROJECT XS "CQ"
END DESCRIPTION:
XS GIS Cut Line= 4
       572478.75      4820258.61       573139.11      4820924.45
       573324.29      4821059.17       573746.71      4821533.55
#Sta/Elev= 30
       0950.6169 553.212959.0471 830.117957.6292850.8699955.4681 857.382942.3801
859.1191 935.223 885.939917.5729935.2751 876.639968.1981855.6711982.6271 855.387
992.2002 858.616 993.786858.17781007.506 848.8431024.599848.18411069.094847.1691
 1089.47850.52891111.182 864.2261127.769864.82291154.985864.63011170.742874.9199
1177.572 883.1751222.528888.37011264.821 911.056 1277.69928.48911278.347931.8879
1302.585935.87711446.403938.72391504.343935.83691563.483 937.3311801.969954.9649
#Mann= 5 ,-1 , 0
       0    .036       0968.1981    .026       0 993.786    .036       0
1024.599    .037       0 1089.47    .036       0
Levee=-1,992.2002,858.6155,-1,1127.769,864.8304,,
Bank Sta=992.2002,1127.769
XS Rating Curve= 0 ,0
Exp/Cntr=0.3,0.1

Type RM Length L Ch R = 1 ,61.56238,97.2809,100.007,104.8649
XS GIS Cut Line= 4
       572428.12      4820305.13       573080.13      4821002.05
       573262.29      4821140.82        573684.5      4821521.89
#Sta/Elev= 30
       0950.3539479.6229957.4109699.0399957.5709829.7952953.8701 845.506950.3091
849.2332944.4731858.2881937.7642 892.775   918.2940.6868  879.17976.6292 857.784
 983.543854.99381000.957858.66391001.159858.71091006.774 853.6781016.753851.0659
1050.393847.64511095.423849.44011117.675855.9882 1147.55 864.9241158.231865.1089
1167.482 865.269 1181.01875.54991201.493877.46981212.471885.47811243.045894.4771
 1308.85933.9792 1465.85 935.9681539.401932.67491649.915 943.0781752.116949.2859
#Mann= 7 ,-1 , 0
       0    .036       0976.6292    .026       01001.159    .036       0
1016.753    .082       01050.393    .037       01095.423    .082       0
1117.675    .036       0
Levee=-1,1000.957,858.7435,-1,1158.231,865.1047,,
Bank Sta=1000.957,1158.231
XS Rating Curve= 0 ,0
Exp/Cntr=0.3,0.1

Type RM Length L Ch R = 1 ,61.50033,99.4889,100.0021,102.1589
XS GIS Cut Line= 4
       572406.32       4820387.5       573019.64      4821069.01
       573189.34      4821222.77       573585.17      4821538.38
#Sta/Elev= 30
       0950.8861 444.684957.7599719.1689954.3638 763.136 947.878866.7408920.0781
873.5239901.6398 875.132900.1381 923.027863.7161936.9088857.2911944.2759855.0688
960.6442 858.359962.6821857.4009 979.038851.89711004.315847.52811009.279847.4641
1062.304 849.2591088.407 855.651 1149.66865.44341161.316866.30711172.476874.6321
1215.172887.77121293.557 920.5351327.058915.77891377.504 922.6861389.109 928.233
1455.656930.34011487.741 925.335 1525.57929.01091596.517922.95091652.106928.3519
#Mann= 7 ,-1 , 0
       0    .036       0936.9088    .026       0962.6821    .036       0
 979.038    .082       01004.315    .037       01062.304    .082       0
1088.407    .036       0
Levee=-1,960.6442,858.3808,-1,1149.66,865.4491,,
Bank Sta=960.6442,1149.66
XS Rating Curve= 0 ,0
Exp/Cntr=0.3,0.1

Type RM Length L Ch R = 1 ,61.43828,78.1849,100.0219,125.727
BEGIN DESCRIPTION:
PROJECT XS "CP"
END DESCRIPTION:
XS GIS Cut Line= 4
        572363.1      4820480.25       572958.59      4821145.09
       573124.97      4821302.44       573532.74      4821616.02
#Sta/Elev= 30
       0952.0751387.2899957.1351 647.625954.4642738.5349931.9312 840.761921.6548
846.1251902.5631879.3291873.4309903.5269 859.753  914.03854.9982931.6517858.2675
931.8278858.2711952.0529848.0609961.2752848.1139970.7639849.8049986.6321 848.675
1017.974847.2989 1025.24  848.911031.293 848.1731055.669 850.9341070.556 854.637
1167.372866.34881210.083879.44621415.458919.68011457.019912.04791473.673903.3641
1498.165906.2481 1568.81  900.161586.575905.51511627.382904.70791635.935908.4531
#Mann= 10 ,-1 , 0
       0    .036       0903.5269    .026       0931.8278    .036       0
961.2752    .037       0970.7639    .082       0986.6321    .037       0
 1025.24    .082       01031.293    .037       01055.669    .057       0
1070.556    .036       0
Levee=-1,931.6517,858.3046,-1,1167.372,866.3514,,
Bank Sta=931.6517,1167.372
XS Rating Curve= 0 ,0
Exp/Cntr=0.3,0.1

Type RM Length L Ch R = 1 ,61.37622,113.474,99.986,80.7531
XS GIS Cut Line= 4
       572296.91      4820584.63       572911.75       4821186.4
       573020.31      4821388.04       573512.35      4821647.49
#Sta/Elev= 30
       0951.6332 406.093955.7852522.6149951.0202670.0589 929.042 803.223 919.905
810.7369 905.751848.9619 876.079 877.261858.4009 881.851855.6711904.3934858.5169
904.5781858.5317 930.686846.8859936.1731846.8551955.9199 847.822 960.199847.5881
970.0781846.6719990.9709848.94121083.947  853.391110.245862.04511179.186867.5364
1211.603868.69011235.496881.17711319.647 890.3691369.686 892.4661434.006 902.478
1472.241 901.4141522.096892.36991578.832920.0571 1615.91922.57681645.585916.2861
#Mann= 8 ,-1 , 0
       0    .036       0 877.261    .026       0904.5781    .036       0
936.1731    .037       0955.9199    .082       0 960.199    .037       0
990.9709    .057       01083.947    .036       0
Levee=-1,904.3934,858.5149,-1,1179.186,867.5431,,
Bank Sta=904.3934,1179.186
XS Rating Curve= 0 ,0
Exp/Cntr=0.3,0.1

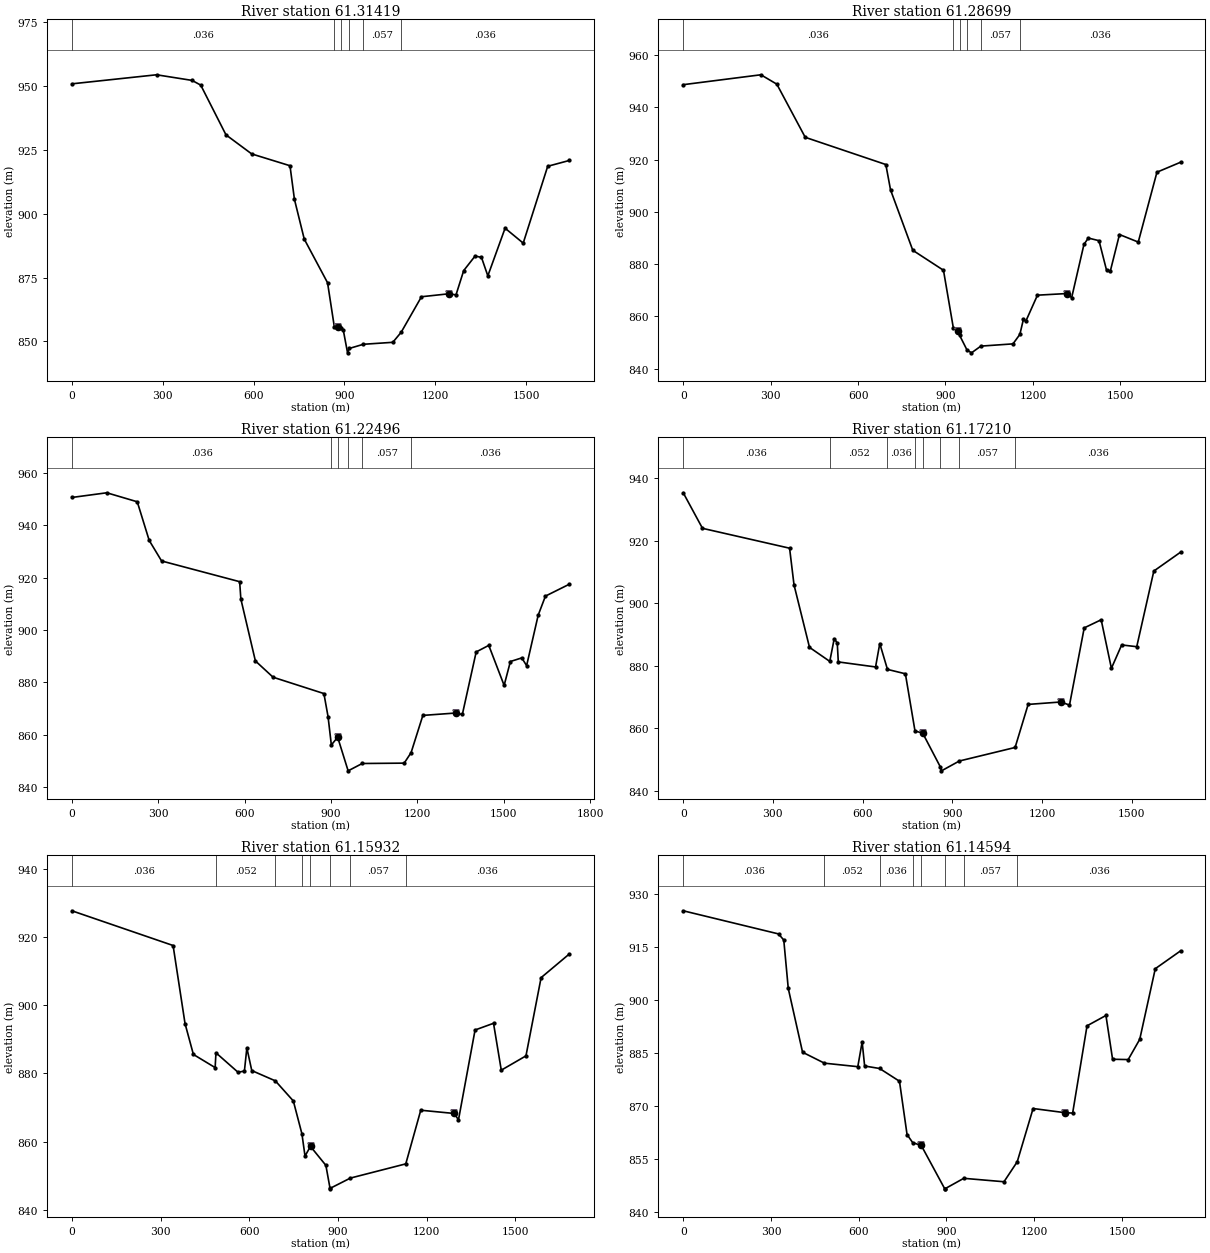
Type RM Length L Ch R = 1 ,61.31419,52.4509,43.8391,24.224
XS GIS Cut Line= 4
       572225.33      4820674.15       572809.46      4821258.22
       572959.65      4821431.09       573493.25      4821677.09
#Sta/Elev= 30
       0 950.816 279.786 954.362396.9301952.1632425.6989950.3158 509.116930.8439
594.0421923.3791 720.488918.7581 735.202 905.595767.5848890.0449844.5929872.9481
866.8101   855.8880.3721855.7244888.6569 855.043896.7841854.2681 910.661 845.511
916.0889  847.22962.9031 848.8611060.109849.62911087.742 853.5691154.755867.4691
1247.251868.65591268.783 868.1781294.254  877.711331.918883.4131 1352.99882.8691
1373.985 875.6411430.942894.30121490.814  888.461571.698 918.5371642.619 920.806
#Mann= 6 ,-1 , 0
       0    .036       0866.8101    .026       0888.6569    .036       0
916.0889    .037       0962.9031    .057       01087.742    .036       0
Levee=-1,880.3721,855.7382,-1,1247.251,868.6617,,
Bank Sta=880.3721,1247.251
XS Rating Curve= 0 ,0
Exp/Cntr=0.3,0.1

Type RM Length L Ch R = 1 ,61.28699,111.3221,99.9771,77.4689
XS GIS Cut Line= 4
        572031.2      4820809.72       572760.62      4821303.73
        572942.3      4821443.13        573486.1      4821688.53
#Sta/Elev= 30
       0 948.658266.5019 952.446321.1909948.8549 418.673 928.519695.2601918.1039
711.3931908.4022787.7181885.2919893.0601 877.646927.0111 855.516 942.152854.3197
948.5142852.7359 973.601847.1779989.1799846.05291021.385 848.6261131.578849.4849
 1155.18853.10021167.496858.9511 1175.48 858.1291215.561868.11881318.348868.7521
1332.846867.1332 1375.04887.5099 1389.94889.97791426.773888.96691452.554877.7009
1465.449877.27291497.011891.32511561.452888.43021625.591915.17211706.574918.9781
#Mann= 6 ,-1 , 0
       0    .036       0927.0111    .026       0948.5142    .036       0
 973.601    .037       01021.385    .057       0 1155.18    .036       0
Levee=-1,942.152,854.2904,-1,1318.348,868.7532,,
Bank Sta=942.152,1318.348
XS Rating Curve= 0 ,0
Exp/Cntr=0.3,0.1

Type RM Length L Ch R = 1 ,61.22496,102.51,85.18,36.9189
XS GIS Cut Line= 5
       571953.73      4820932.38       572691.12      4821400.66
       572900.31      4821493.82       572995.86      4821476.51
       573479.37      4821687.83
#Sta/Elev= 30
       0950.5953121.3682952.3872227.2044948.9476268.6561934.1833311.7053926.3359
582.7904918.4246587.0064911.8049637.4435888.1555   698.9881.9299875.4335875.6855
889.8694866.8637901.3049856.0567923.2178859.0038923.2453859.0003959.5915846.1684
1008.516848.97341154.268849.11131178.196853.10471219.129867.34531333.162868.2528
1356.223867.69211404.315891.58571448.047894.09421501.402878.81271523.114887.9333
1562.666889.31041579.486886.3535 1619.69905.63551644.857912.91861727.285 917.426
#Mann= 6 ,-1 , 0
       0    .036       0901.3049    .026       0923.2178    .036       0
959.5915    .037       01008.516    .057       01178.196    .036       0
Levee=-1,923.2453,858.9996,-1,1333.162,868.2654,,
Bank Sta=923.2453,1333.162
XS Rating Curve= 0 ,0
Exp/Cntr=0.3,0.1

Type RM Length L Ch R = 1 ,61.17210,21.5481,20.5999,17.665
XS GIS Cut Line= 6
        571931.3      4821201.41       572584.02      4821496.11
       572802.93      4821530.24       572911.71      4821521.56
       572991.67       4821483.5       573475.66      4821693.76
#Sta/Elev= 30
       0935.3141 64.4442923.9369355.7851917.5776370.6252 905.833422.3857885.8408
490.1958881.3572505.0716888.6146515.2653887.2539518.6983881.1829643.3938879.5714
657.4557887.0659683.1906878.7911743.1338877.3854775.3347859.0547800.6953858.4478
800.7797858.4357860.5242847.5034863.8431846.3266923.5334  849.471110.141853.8082
1153.786 867.5871262.665868.3581 1292.09867.38891341.316892.07491398.057894.6715
1432.247879.13921466.627886.6157 1517.01886.05821574.178910.26661663.556916.2977
#Mann= 8 ,-1 , 0
       0    .036       0490.1958    .052       0683.1906    .036       0
775.3347    .026       0800.6953    .036       0860.5242    .037       0
923.5334    .057       01110.141    .036       0
Levee=-1,800.7797,858.4357,-1,1262.665,868.3599,,
Bank Sta=800.7797,1262.665
XS Rating Curve= 0 ,0
Exp/Cntr=0.3,0.1

Type RM Length L Ch R = 1 ,61.15932,24.8519,21.5661,17.384
XS GIS Cut Line= 6
       571906.98      4821232.11       572570.96      4821521.63
        572791.9      4821548.63       572907.98      4821535.22
       572992.37      4821491.19       573471.27      4821700.78
#Sta/Elev= 30
       0927.7911342.3983917.5854382.7743894.6502411.0249885.5797 484.568881.7142
 487.345 886.064562.0092880.3472583.5569880.6934591.8372887.4926608.4741880.8406
  688.16877.8209749.0112871.9112778.0855862.2499788.4984855.7175 806.916 858.554
807.1652858.5356859.0626852.9944873.4218846.0912874.0104846.2556941.9482849.2521
1129.263853.42661179.948869.19121292.962868.23521307.509866.36321363.579892.7601
    1426894.73211452.209880.95461535.687885.16031586.889908.14221681.821915.0611
#Mann= 8 ,-1 , 0
       0    .036       0 487.345    .052       0  688.16    .036       0
778.0855    .026       0 806.916    .036       0874.0104    .037       0
941.9482    .057       01129.263    .036       0
Levee=-1,807.1652,858.5332,-1,1292.962,868.238,,
Bank Sta=807.1652,1292.962
XS Rating Curve= 0 ,0
Exp/Cntr=0.5,0.3

Type RM Length L Ch R = 1 ,61.14594,30.818,30.4861,39.4091
BEGIN DESCRIPTION:
Highway 21 Upstream and PROJECT XS "CO"
END DESCRIPTION:
XS GIS Cut Line= 6
       571885.41      4821253.12       572555.62      4821548.36
       572806.61      4821563.35       572927.66      4821539.08
       572999.59      4821501.34       573467.75      4821706.41
#Sta/Elev= 30
       0925.2509 325.851918.6943343.7376916.9594359.0922903.2516407.9522885.1815
482.7078882.0809596.8048881.0897611.6876 888.108620.1391881.2777671.3997880.5736
739.2498876.9642765.1635861.8629784.4226859.5802813.6614858.7701813.8282858.7643
893.8538846.5146894.3369846.4835959.0629849.46481096.545848.49131141.802854.1489
1196.063869.23841303.535868.07011331.239867.93571380.432892.66111445.064895.5917
1467.793883.19061521.165883.0986  1560.6888.82941613.729908.84231700.125913.8922
#Mann= 8 ,-1 , 0
       0    .036       0482.7078    .052       0671.3997    .036       0
784.4226    .026       0813.6614    .036       0893.8538    .037       0
959.0629    .057       01141.802    .036       0
Levee=-1,813.8282,858.7831,-1,1303.535,868.0673,,
Bank Sta=813.8282,1303.535
XS Rating Curve= 0 ,0
Exp/Cntr=0.5,0.3

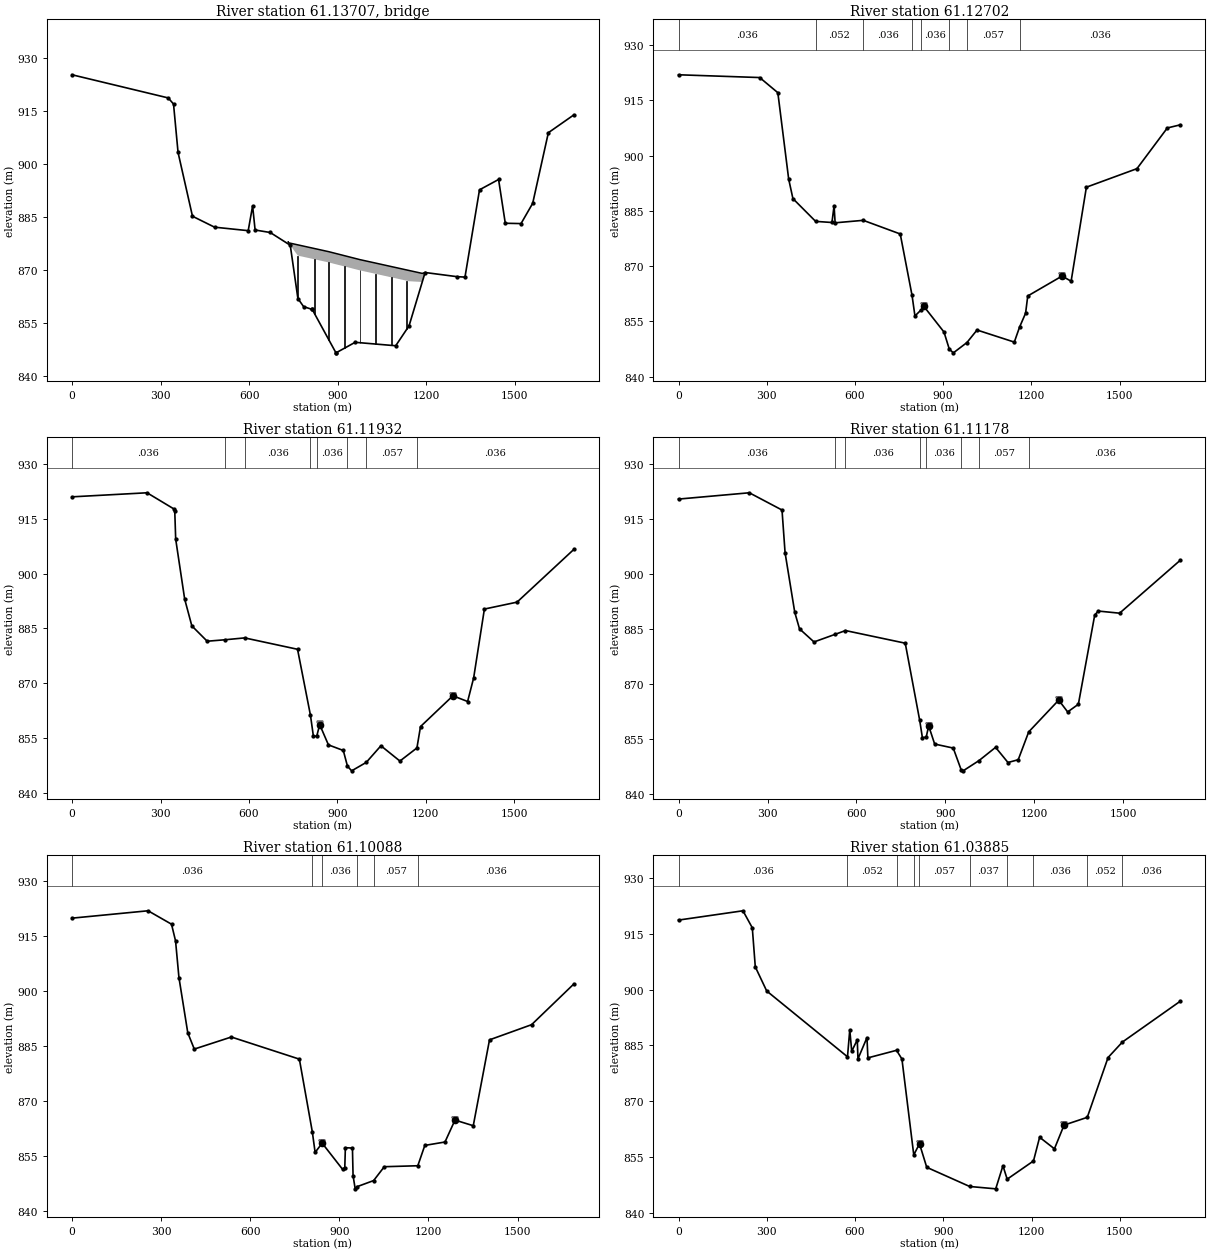
Type RM Length L Ch R = 3 ,61.13707,,,
BEGIN DESCRIPTION:
Highway 21 Bridge
END DESCRIPTION:
Bridge Culvert--1,0,-1,-1, 0
Deck Dist Width WeirC Skew NumUp NumDn MinLoCord MaxHiCord MaxSubmerge Is_Ogee
9.144,12.6492,1.44,0, 13, 14, , , 0.95, 0, 0,0,,
732.4344732.7392732.8916764.8956821.2836870.0516922.3248975.51241028.2431080.973
1133.7041186.4341196.063
877.9277877.6655877.6655877.0742876.0348875.1326874.0201872.8862871.9139870.9385
869.9632868.9909869.2378
 870.204 870.204874.6175874.0262872.9868872.0846870.9721869.8383 868.866867.8906
866.9152865.9429  861.06
754.0752763.2192763.3716795.3756851.7636900.5316952.80481005.9921058.7231111.453
1164.1841216.9141217.0661297.982
878.7079877.6655877.6655877.0742876.0348875.1326874.0201872.8862871.9139870.9385
869.9632868.9909868.9909867.3846
 870.204 870.204874.6175874.0262872.9868872.0846870.9721869.8383 868.866867.8906
866.9152865.9429  861.06  861.06
Pier Skew, UpSta & Num, DnSta & Num=  ,764.8956, 2 ,795.3756, 2 , 0 , 0 , 0 ,,
  3.6576  3.6576
855.7382874.0262
  3.6576  3.6576
855.7382874.0262
Pier Skew, UpSta & Num, DnSta & Num=  ,821.2836, 2 ,851.7636, 2 , 0 , 0 , 0 ,,
  3.6576  3.6576
848.6028872.9868
  3.6576  3.6576
848.6028872.9868
Pier Skew, UpSta & Num, DnSta & Num=  ,870.0516, 2 ,900.5316, 2 , 0 , 0 , 0 ,,
  3.6576  3.6576
844.6526872.0846
  3.6576  3.6576
844.6526872.0846
Pier Skew, UpSta & Num, DnSta & Num=  ,922.3248, 2 ,952.8048, 2 , 0 , 0 , 0 ,,
  4.2672  4.2672
842.3209870.9721
  4.2672  4.2672
842.3209870.9721
Pier Skew, UpSta & Num, DnSta & Num=  ,975.5124, 2 ,1005.992, 2 , 0 , 0 , 0 ,,
   3.048   3.048
845.4543869.8383
   3.048   3.048
845.4543869.8383
Pier Skew, UpSta & Num, DnSta & Num=  ,1028.243, 2 ,1058.723, 2 , 0 , 0 , 0 ,,
   3.048   3.048
846.9203 868.866
   3.048   3.048
846.9203 868.866
Pier Skew, UpSta & Num, DnSta & Num=  ,1080.973, 2 ,1111.453, 2 , 0 , 0 , 0 ,,
  3.6576  3.6576
846.5546867.8906
  3.6576  3.6576
846.5546867.8906
Pier Skew, UpSta & Num, DnSta & Num=  ,1133.704, 2 ,1164.184, 2 , 0 , 0 , 0 ,,
  4.2672  4.2672
848.0176866.9152
  4.2672  4.2672
848.0176866.9152
BR Coef=-1 , 0 , 0 ,1.25, 0 ,,,0.8,-1,2,0,
WSPro=,,,, 1 ,,,, 0 ,,,, 0 ,,,,-1 ,-1 ,-1 , 0 , 0 , 0 , 0 , 0
BC Design=,, 0 ,, 0 ,,,,,,
BC Use User HTab Curves=0
BC User HTab FreeFlow(D)= 0

Type RM Length L Ch R = 1 ,61.12702,12.594,12.4169,14.1711
BEGIN DESCRIPTION:
Highway 21 Downstream
END DESCRIPTION:
XS GIS Cut Line= 6
       571846.13      4821290.14       572540.25      4821579.25
       572780.13      4821597.18       572876.31      4821592.89
       573003.67      4821548.08       573447.24      4821739.23
#Sta/Elev= 30
       0921.9277276.0908921.1754 337.783917.0609374.5989893.6227389.0635888.3067
466.3257882.1217521.8301881.8203529.0572886.3879532.5798881.7333628.2523882.4066
754.1027878.7015794.3018862.0106804.1084 856.439825.9638858.1571833.8383859.1018
902.9227852.0793921.0403847.4083934.8984846.4284 980.978 849.224 1015.25852.6252
1142.104849.34381159.814853.3873 1180.46 857.1891187.804861.86931304.504867.2782
1335.319865.8759 1387.24 891.4051559.227896.43821662.489907.48471706.766908.3409
#Mann= 8 ,-1 , 0
       0    .036       0466.3257    .052       0628.2523    .036       0
794.3018    .026       0825.9638    .036       0921.0403    .037       0
 980.978    .057       01159.814    .036       0
Levee=-1,833.8383,859.1124,-1,1304.504,867.284,,
Bank Sta=833.8383,1304.504
XS Rating Curve= 0 ,0
Exp/Cntr=0.5,0.3

Type RM Length L Ch R = 1 ,61.11932,11.8589,12.142,21.8069
XS GIS Cut Line= 6
       571816.48      4821317.47       572527.27      4821593.09
       572778.66      4821610.42       572865.77      4821607.54
       572992.49      4821590.77       573429.25      4821771.44
#Sta/Elev= 30
       0920.9578254.2939922.0679345.5908917.6418348.3135917.0911351.4649909.3894
 381.929 893.018 406.231885.6982458.2689881.5024518.3521881.8962585.3562882.4113
764.7664879.3002808.5887861.2648818.6315855.4913830.0905855.6019839.8764858.7203
869.5026853.1752919.9476851.6462934.0675847.3663948.2584846.0812997.8448848.3898
1047.591 852.9311111.987848.75591169.688852.33631181.838858.1763 1291.81866.5919
1341.607865.02881362.104 871.4831398.522890.29221509.204892.18011701.985906.5971
#Mann= 8 ,-1 , 0
       0    .036       0518.3521    .052       0585.3562    .036       0
808.5887    .026       0830.0905    .036       0934.0675    .037       0
997.8448    .057       01169.688    .036       0
Levee=-1,839.8764,858.777,-1,1291.81,866.5921,,
Bank Sta=839.8764,1291.81
XS Rating Curve= 0 ,0
Exp/Cntr=0.5,0.3

Type RM Length L Ch R = 1 ,61.11178,16.589,17.5751,18.11
XS GIS Cut Line= 6
       571803.62      4821329.32       572520.35      4821603.03
       572618.79      4821608.79       572855.52       4821629.9
       572985.97      4821635.49         573411.      4821805.79
#Sta/Elev= 30
       0920.5128238.6667922.2306348.9113917.5254359.2662905.8635391.8615  889.65
407.8928885.1373456.7376881.5602528.9316883.6639562.9321 884.668764.4216881.2244
813.1796860.1693822.1763855.5074  834.97855.5709843.4548858.6783863.5898853.7268
926.2527852.6296953.3354846.6176959.5942846.42231012.839849.19871069.045852.8273
1110.787848.69371145.398849.45511180.699  857.041281.916 865.7031312.044  862.48
1348.168864.57681403.225888.87051415.093889.98711487.145889.40251691.943903.8491
#Mann= 8 ,-1 , 0
       0    .036       0528.9316    .052       0562.9321    .036       0
813.1796    .026       0  834.97    .036       0953.3354    .037       0
1012.839    .057       01180.699    .036       0
Levee=-1,843.4548,858.6948,-1,1281.916,865.7051,,
Bank Sta=843.4548,1281.916
XS Rating Curve= 0 ,0
Exp/Cntr=0.3,0.1

Type RM Length L Ch R = 1 ,61.10088,126.3161,99.9741,74.7181
XS GIS Cut Line= 6
       571793.23      4821344.65       572506.14      4821614.87
       572618.01      4821623.33       572777.82       4821640.8
       572947.36       4821656.7       573401.47      4821823.73
#Sta/Elev= 30
       0 919.955255.9474921.9664334.7878918.3073348.4087913.7548359.8326903.7601
389.5865 888.673411.4846884.2364536.2874887.5276765.3208881.4944808.8599861.6843
818.3331856.0543841.8271858.5422841.9326858.5835 910.772851.4357918.2267851.8353
920.1829857.3307943.9973857.2375946.0834849.7296953.2431846.1104960.0966846.7158
1015.409848.36721051.195852.14581164.078852.41011187.682857.95841255.602858.8864
1289.298864.86981350.817863.33011405.481886.75491547.178890.89481689.501902.0026
#Mann= 6 ,-1 , 0
       0    .036       0808.8599    .026       0841.9326    .036       0
960.0966    .037       01015.409    .057       01164.078    .036       0
Levee=-1,841.8271,858.5637,-1,1289.298,864.8822,,
Bank Sta=841.8271,1289.298
XS Rating Curve= 0 ,0
Exp/Cntr=0.3,0.1

Type RM Length L Ch R = 1 ,61.03885,87.11,100.0101,111.1801
XS GIS Cut Line= 5
       571757.16      4821400.76       572457.94       4821663.1
        572624.4      4821748.64       572851.79      4821721.55
       573370.87      4821875.37
#Sta/Elev= 30
       0918.6508219.0081921.1486250.7427916.5781260.9366 906.085299.7542899.6089
574.3596881.9403582.0939889.1775588.7264883.4348607.6033886.4822609.9651881.3846
640.5266887.0792643.7601 881.652741.0587883.6786759.4211881.3392799.6568855.5903
819.0409858.5844819.3359858.5324843.7455852.2631989.6509 847.1161078.251846.4821
1102.813852.68351117.174849.07461206.642853.97131227.481860.33121277.845857.2272
1310.597863.59931389.498865.67991460.171881.74161508.866885.89841705.819896.8715
#Mann= 10 ,-1 , 0
       0    .036       0574.3596    .052       0741.0587    .036       0
799.6568    .026       0819.0409    .057       0989.6509    .037       0
1117.174    .057       01206.642    .036       01389.498    .052       0
1508.866    .036       0
Levee=-1,819.3359,858.6368,-1,1310.597,863.6112,,
Bank Sta=819.3359,1310.597
XS Rating Curve= 0 ,0
Exp/Cntr=0.3,0.1

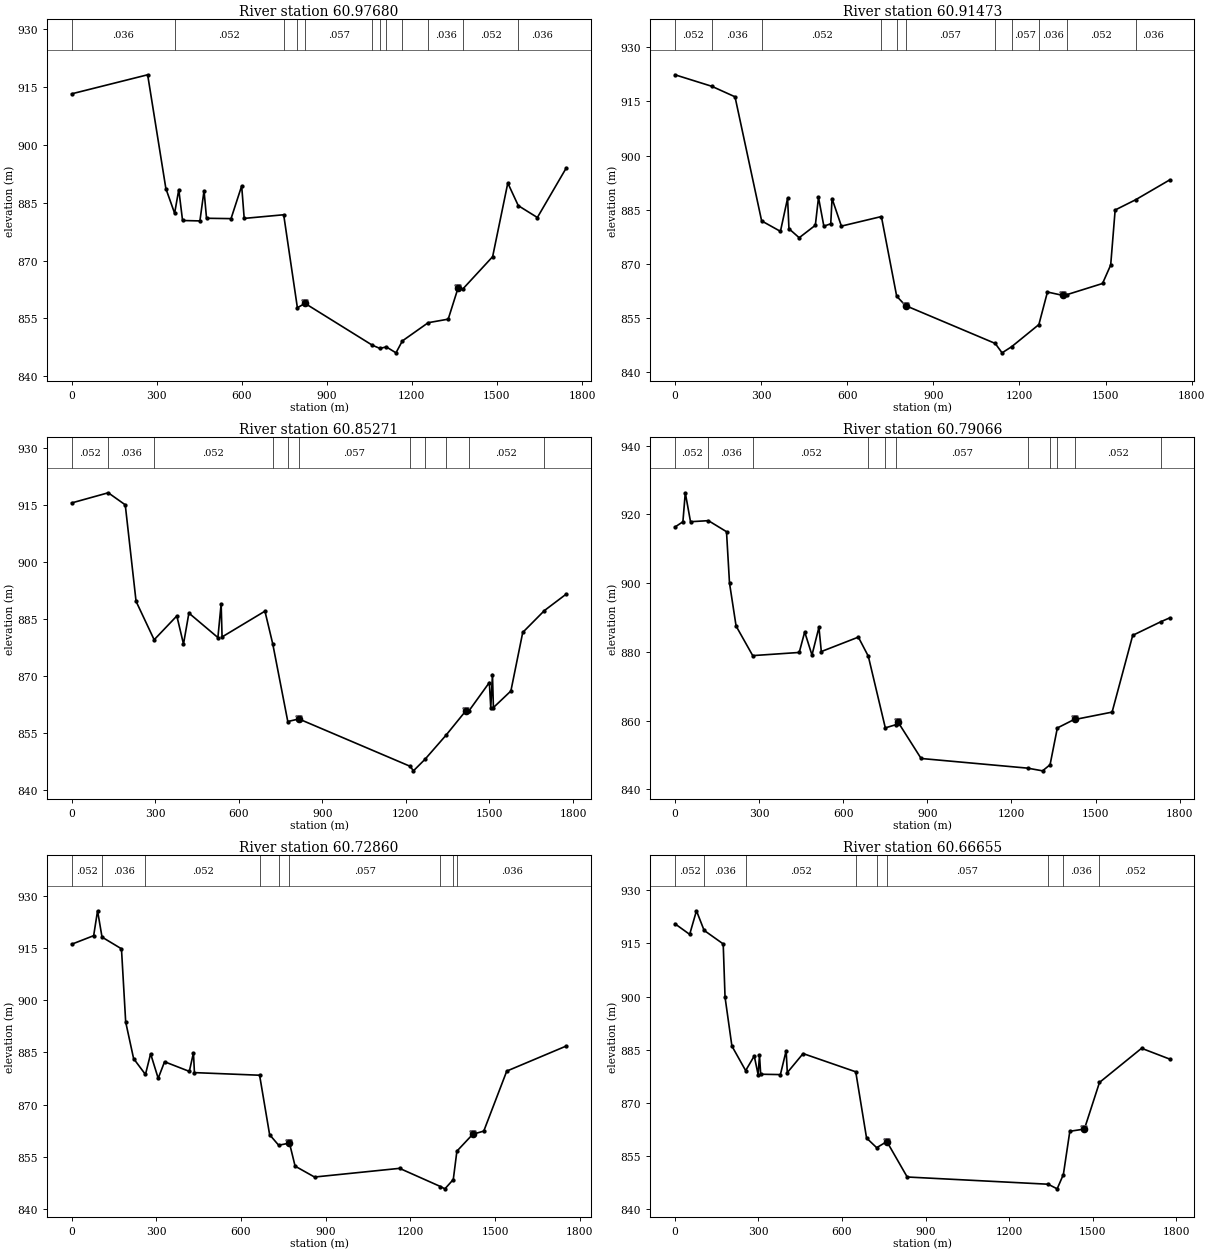
Type RM Length L Ch R = 1 ,60.97680,71.9889,100.0271,120.442
BEGIN DESCRIPTION:
PROJECT XS "CN"
END DESCRIPTION:
XS GIS Cut Line= 5
       571663.08      4821499.43       572359.88      4821779.89
       572629.34      4821837.93       572858.26      4821831.82
       573335.44      4821938.34
#Sta/Elev= 30
       0913.2299267.9005918.1664332.2134888.6505363.0132882.2728377.6841 888.386
391.0404 880.395452.2263880.2834 466.803888.1241475.6364880.9692 562.061880.8799
599.5608889.3536608.4802880.9379747.7707881.8815796.0934857.7795823.2252858.9297
823.3989858.89511060.554848.06031086.993847.24311109.947847.62511143.851846.0897
1166.419849.17771257.497853.90211328.119854.82171362.535862.81611379.807862.6498
 1484.83871.01141538.332890.10721575.272884.24761642.624 881.1681744.688894.0284
#Mann= 12 ,-1 , 0
       0    .036       0363.0132    .052       0747.7707    .036       0
796.0934    .026       0823.2252    .057       01060.554    .037       0
1086.993    .082       01109.947    .037       01166.419    .057       0
1257.497    .036       01379.807    .052       01575.272    .036       0
Levee=-1,823.3989,858.902,-1,1362.535,862.8096,,
Bank Sta=823.3989,1362.535
XS Rating Curve= 0 ,0
Exp/Cntr=0.3,0.1

Type RM Length L Ch R = 1 ,60.91473,127.8319,99.9701,74.156
XS GIS Cut Line= 5
       571620.89      4821582.99       572301.98      4821830.42
       572607.58      4821905.79       572831.22      4821955.03
       573276.31      4822047.56
#Sta/Elev= 30
       0922.3766128.1164919.1936209.1658916.2819301.9167881.9343367.4233879.0402
392.2968 888.207397.0901879.7735432.7404877.2766489.0046880.7236 500.008888.4283
518.7214880.4651542.6705881.1463547.2401888.1071579.7772880.4959719.0969  883.14
772.3741861.0993803.1297858.4968803.1371858.50341115.567 848.0281139.524845.4225
1172.967847.12511267.752853.25231297.592862.25451350.721861.32911366.646861.5587
1489.486 864.6141517.931869.7291 1533.46884.95481604.857887.79221723.013893.2615
#Mann= 11 ,-1 , 0
       0    .052       0128.1164    .036       0301.9167    .052       0
719.0969    .036       0772.3741    .026       0803.1371    .057       0
1115.567    .037       01172.967    .057       01267.752    .036       0
1366.646    .052       01604.857    .036       0
Levee=-1,803.1297,858.4539,-1,1350.721,861.3526,,
Bank Sta=803.1297,1350.721
XS Rating Curve= 0 ,0
Exp/Cntr=0.3,0.1

Type RM Length L Ch R = 1 ,60.85271,91.8429,100,101.389
XS GIS Cut Line= 4
       571539.51      4821668.69       572608.22      4822045.26
       572836.95      4822034.14       573243.81      4822110.17
#Sta/Elev= 30
       0915.6329131.2469 918.309 192.284  915.13 231.089889.6929296.0611879.5589
377.5079885.8448  401.41 878.433420.8081886.5961 524.968 880.145536.6199 889.059
539.9432880.3038693.8541 887.096 721.949878.4589775.9401858.0041815.7231 858.681
815.9191858.67881215.325846.20011227.073845.00591268.606 848.0461343.553854.3489
1415.068860.81271425.073860.68291499.718868.28891504.798861.65411510.931870.4031
1514.267861.68121577.014 866.053  1619.6881.49411697.335 887.2521776.013891.6119
#Mann= 11 ,-1 , 0
       0    .052       0131.2469    .036       0296.0611    .052       0
 721.949    .036       0775.9401    .026       0815.7231    .057       0
1215.325    .037       01268.606    .057       01343.553    .036       0
1425.073    .052       01697.335    .036       0
Levee=-1,815.9191,858.6978,-1,1415.068,860.8009,,
Bank Sta=815.9191,1415.068
XS Rating Curve= 0 ,0
Exp/Cntr=0.3,0.1

Type RM Length L Ch R = 1 ,60.79066,73.1109,100.021,112.9311
XS GIS Cut Line= 4
       571532.35      4821683.42       572615.72      4822144.85
       572844.46      4822133.95       573196.18      4822196.73
#Sta/Elev= 30
       0 916.309 28.2891917.8299 36.7589926.2631 55.4401  917.85119.2341918.1569
  183.77914.9511 194.459 900.033217.9549887.5191 277.272  878.92443.1021879.8408
462.6139   885.8  488.62879.0801513.3981887.1552521.8792880.1021653.9749884.2988
689.4771878.7469750.1531 857.912790.0151858.8941794.4398859.7343 877.799 849.014
 1257.78 846.2041310.958845.42191337.681 847.1981363.609857.88611425.995860.4514
1427.107 860.3661558.897862.49591632.404884.8121 1733.13888.7889 1763.82889.8721
#Mann= 11 ,-1 , 0
       0    .052       0119.2341    .036       0 277.272    .052       0
689.4771    .036       0750.1531    .026       0790.0151    .057       0
 1257.78    .037       01337.681    .057       01363.609    .036       0
1427.107    .052       0 1733.13    .036       0
Levee=-1,794.4398,859.7463,-1,1425.995,860.4504,,
Bank Sta=794.4398,1425.995
XS Rating Curve= 0 ,0
Exp/Cntr=0.3,0.1

Type RM Length L Ch R = 1 ,60.72860,92.904,100.0021,101.0561
XS GIS Cut Line= 4
       571523.32      4821701.98       572613.76      4822223.51
       572840.67      4822254.38       573145.51      4822333.88
#Sta/Elev= 30
       0 916.127 77.8179 918.584 91.6272925.7459107.4451918.1728 176.353914.8091
191.3019893.7529219.3789 883.222261.3389 878.658279.6549884.6189306.5151877.5469
  329.07882.3189416.8469879.5461431.4401884.8749434.9319 879.195 665.881878.4449
701.3771861.3411733.3632858.3119771.6042858.9106771.7481858.9249 791.679852.2921
860.5602849.15911161.957851.65691306.697846.42991322.538 845.7631352.269 848.441
1365.064856.60111421.163861.45561460.332862.37711541.762879.63091752.779886.8461
#Mann= 9 ,-1 , 0
       0    .052       0107.4451    .036       0261.3389    .052       0
 665.881    .036       0733.3632    .026       0771.7481    .057       0
1306.697    .037       01352.269    .057       01365.064    .036       0
Levee=-1,771.6042,858.9355,-1,1421.163,861.4684,,
Bank Sta=771.6042,1421.163
XS Rating Curve= 0 ,0
Exp/Cntr=0.3,0.1

Type RM Length L Ch R = 1 ,60.66655,26.0119,30.128,31.456
XS GIS Cut Line= 4
       571505.48      4821717.25       572599.54       4822320.6
       572825.92      4822355.18       573116.12      4822423.89
#Sta/Elev= 30
       0920.5219 52.7981917.5419 77.1909924.1929 104.643  918.67 173.263914.8499
179.8701  899.83204.4961886.0649253.8801 879.145 284.817883.2659298.7119 877.981
303.6119883.4969307.9251878.1221378.6982878.0178399.3069 884.735403.5311 878.582
 460.202883.9429649.3569 878.804 688.178860.1441724.5081857.4149760.7168859.1168
 761.284 859.112834.1848849.15391340.641847.11691372.869 845.8161395.184849.8558
1418.361862.03691470.666862.66691524.877 875.8081676.086 885.4331776.625 882.403
#Mann= 9 ,-1 , 0
       0    .052       0 104.643    .036       0253.8801    .052       0
649.3569    .036       0724.5081    .026       0 761.284    .057       0
1340.641    .037       01395.184    .036       01524.877    .052       0
Levee=-1,760.7168,859.1184,-1,1470.666,862.6755,,
Bank Sta=760.7168,1470.666
XS Rating Curve= 0 ,0
Exp/Cntr=0.3,0.1

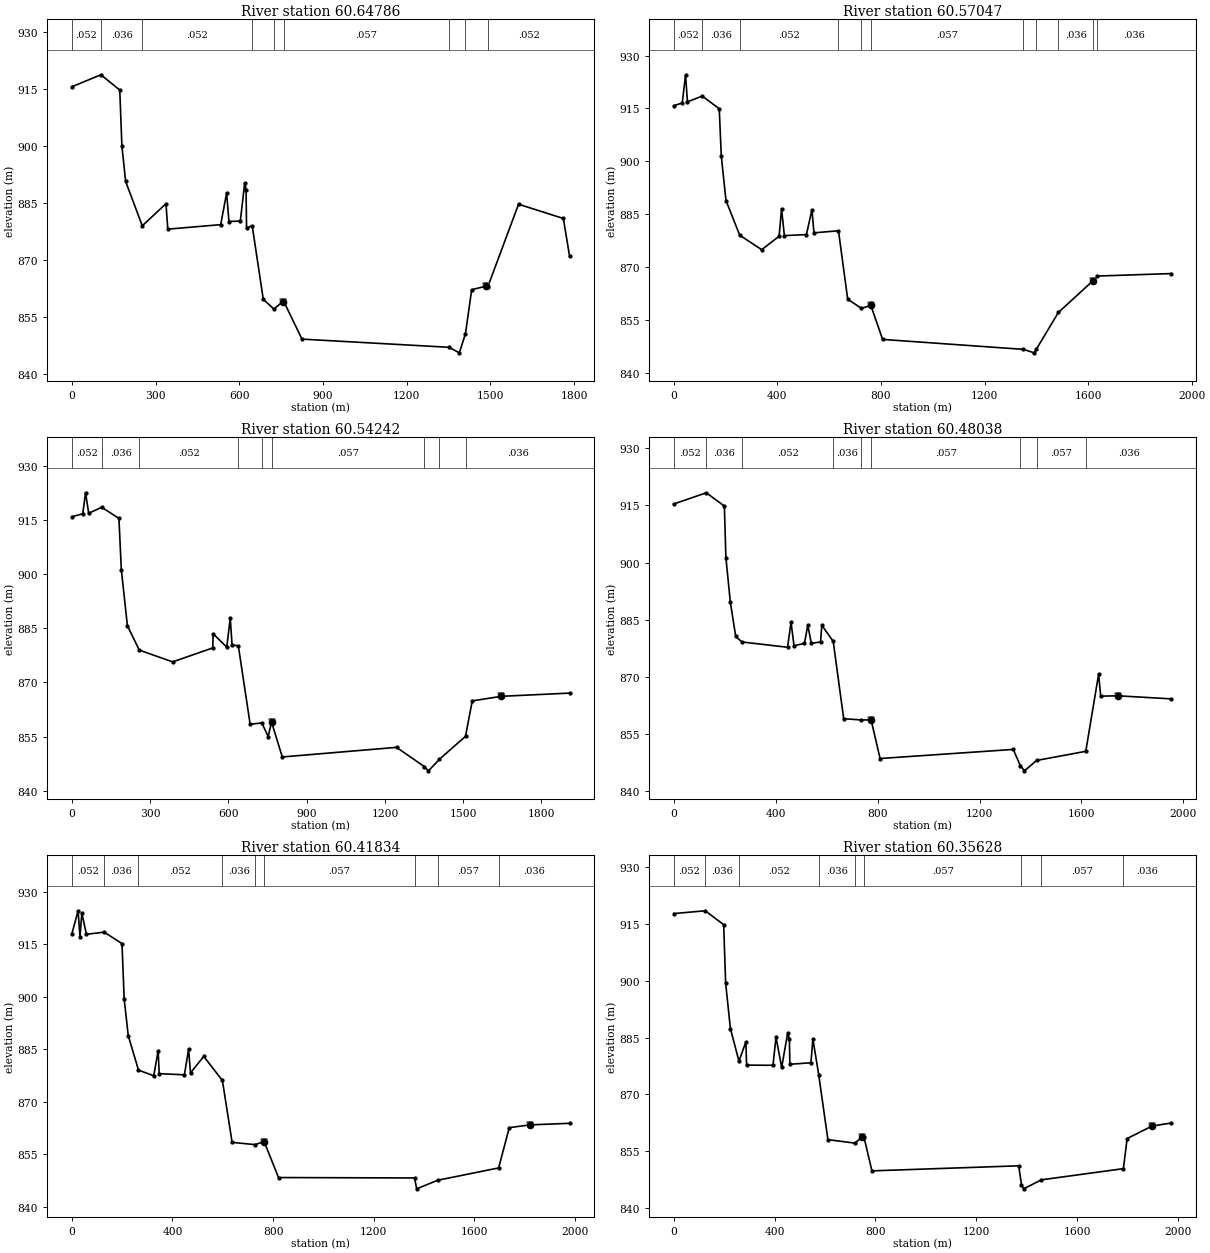
Type RM Length L Ch R = 1 ,60.64786,92.277,124.719,153.5729
XS GIS Cut Line= 4
       571497.33      4821724.04       572594.71      4822347.69
       572805.49       4822384.8       573102.82      4822461.69
#Sta/Elev= 30
       0915.6201104.1471918.7659171.7091 914.746179.3589899.9952192.7141890.6969
 252.343879.0301 337.196 884.835  343.84878.1529 533.343879.3331554.5519 887.641
 562.944880.1591 603.696880.2858619.3188890.2379624.3441 888.566626.0071878.4461
 646.283879.0359 685.918859.7048723.6799 857.139 755.331859.0238760.2388858.9861
824.7098 849.2171351.595847.06211388.663845.60611410.445850.63491432.799 862.217
1484.528863.16111490.517862.96411600.655884.70791761.312880.95791783.342871.1409
#Mann= 9 ,-1 , 0
       0    .052       0104.1471    .036       0 252.343    .052       0
 646.283    .036       0723.6799    .026       0760.2388    .057       0
1351.595    .037       01410.445    .036       01490.517    .052       0
Levee=-1,755.331,859.0605,-1,1484.528,863.157,,
Bank Sta=755.331,1484.528
XS Rating Curve= 0 ,0
Exp/Cntr=0.3,0.1

Type RM Length L Ch R = 1 ,60.57047,16.2251,45.2079,43.8589
BEGIN DESCRIPTION:
PROJECT XS "CM"
END DESCRIPTION:
XS GIS Cut Line= 5
       571475.45      4821732.44       572525.46      4822413.67
       572591.08      4822428.01       572708.35      4822528.95
       573067.72      4822796.55
#Sta/Elev= 30
       0915.7671  32.816916.5629 45.4719 924.556  52.902 916.878109.9152918.5129
175.6389  914.91183.3771 901.563 201.556888.8669254.6101879.0209339.6371874.9061
406.8199878.7241416.2019 886.548426.9529878.9021512.2231879.1819533.5039886.2599
541.3409 879.686  636.05880.2752 671.532860.8549  724.63858.2421760.9482  859.08
760.9484  859.08806.3691849.43311350.105846.60791391.807845.62191400.451 846.713
1485.193  857.091618.403866.06621618.935866.07791635.461867.42081921.585868.1259
#Mann= 11 ,-1 , 0
       0    .052       0109.9152    .036       0254.6101    .052       0
  636.05    .036       0  724.63    .026       0760.9482    .057       0
1350.105    .037       01400.451    .057       01485.193    .036       0
1618.935    .052       01635.461    .036       0
Levee=-1,760.9484,859.0513,-1,1618.403,866.0831,,
Bank Sta=760.9484,1618.403
XS Rating Curve= 0 ,0
Exp/Cntr=0.3,0.1

Type RM Length L Ch R = 1 ,60.54242,104.6281,99.9979,99.7531
XS GIS Cut Line= 4
       571466.14       4821734.4        572517.1      4822427.47
       572694.08      4822572.79       573028.36      4822826.54
#Sta/Elev= 30
       0915.8801  41.718 916.732 52.4759922.5281 64.5469916.8531114.4561918.5178
180.4209915.4329189.6639901.2101212.8741885.7202258.4789878.9631386.3682875.7081
540.0892879.5739 541.657883.4698593.8419 879.801607.1219 887.869 614.137880.3679
  638.09880.1679683.3991 858.425728.1279858.8121 752.465855.0372765.4504859.0377
765.5171859.0441806.6349849.37921244.532 852.0441351.339 846.6991366.963845.5399
1408.758 848.7361508.906855.08891534.788864.9042  1645.6866.17291907.593  867.06
#Mann= 9 ,-1 , 0
       0    .052       0114.4561    .036       0258.4789    .052       0
  638.09    .036       0728.1279    .026       0765.5171    .057       0
1351.339    .037       01408.758    .057       01508.906    .036       0
Levee=-1,765.4504,859.0392,-1,1645.6,866.1898,,
Bank Sta=765.4504,1645.6
XS Rating Curve= 0 ,0
Exp/Cntr=0.3,0.1

Type RM Length L Ch R = 1 ,60.48038,111.551,99.989,89.168
XS GIS Cut Line= 4
       571427.02      4821749.55       572453.03      4822507.85
       572633.51       4822648.8       572989.87      4822920.71
#Sta/Elev= 30
       0 915.383127.5359 918.324198.5809914.8358204.6019 901.264 222.127889.5649
243.1801 880.623267.5711879.1779446.5219877.7929460.1791884.3221471.9542 878.187
512.7961878.8101 525.993883.5601 540.033 878.807576.0878 879.188581.0211883.5688
625.7639879.3389666.8549 859.049733.9639858.7219 774.588858.7131774.7711858.6212
809.7048848.60411332.318850.98691360.119846.74511376.176845.3671 1424.18848.0959
1616.948850.48621667.323870.68591675.527864.9651  1743.2865.05591953.072864.2479
#Mann= 9 ,-1 , 0
       0    .052       0127.5359    .036       0267.5711    .052       0
625.7639    .036       0733.9639    .026       0 774.588    .057       0
1360.119    .037       0 1424.18    .057       01616.948    .036       0
Levee=-1,774.7711,858.7253,-1,1743.2,865.056,,
Bank Sta=774.7711,1743.2
XS Rating Curve= 0 ,0
Exp/Cntr=0.3,0.1

Type RM Length L Ch R = 1 ,60.41834,90.785,100.0091,116.02
XS GIS Cut Line= 4
       571406.48      4821764.05       572390.37      4822602.48
       572586.34      4822720.94       572949.02      4822998.66
#Sta/Elev= 30
       0917.9131 24.8369924.5059  32.243917.0469  39.588  923.84 57.8681917.7848
   128.6918.4011199.3761915.1199207.9199 899.356 224.081888.8611264.9169878.9692
325.4249877.3662343.0789 884.497347.2391877.9639447.3681877.6399464.0979884.8801
471.6689878.1681524.1789882.8932598.4861 876.025 637.071858.3329728.2729857.6902
764.2372858.5535764.4789858.5631821.5408848.27921362.372848.1661 1371.06845.0541
 1454.37 847.5071696.733851.02911739.022  862.53 1819.65863.32461978.466863.7779
#Mann= 9 ,-1 , 0
       0    .052       0   128.6    .036       0264.9169    .052       0
598.4861    .036       0728.2729    .026       0764.4789    .057       0
1362.372    .037       0 1454.37    .057       01696.733    .036       0
Levee=-1,764.2372,858.5149,-1,1819.65,863.3246,,
Bank Sta=764.2372,1819.65
XS Rating Curve= 0 ,0
Exp/Cntr=0.3,0.1

Type RM Length L Ch R = 1 ,60.35628,119.3771,99.9838,81.502
XS GIS Cut Line= 4
       571390.78      4821781.87       572339.42      4822674.61
       572522.43      4822812.27       572870.39      4823086.03
#Sta/Elev= 30
       0 917.722124.7821918.4609 197.978 914.796205.8141899.3721224.6571887.3792
258.6469 878.793 286.156 883.874 288.976877.7319393.5691 877.689405.6151885.0989
428.1151877.1309452.1129 886.278458.8179884.4991460.5531 877.956544.0201878.3571
 552.027884.5741574.9461875.2579611.5001858.0651718.0899857.1561748.5126858.7877
 754.419858.7762786.2858  849.831368.627851.16311379.318 846.2221387.713845.0861
1458.886847.46591783.873850.41491798.679858.35711898.224861.67481974.403 862.459
#Mann= 9 ,-1 , 0
       0    .052       0124.7821    .036       0258.6469    .052       0
574.9461    .036       0718.0899    .026       0 754.419    .057       0
1379.318    .037       01458.886    .057       01783.873    .036       0
Levee=-1,748.5126,858.7862,-1,1898.224,861.6757,,
Bank Sta=748.5126,1898.224
XS Rating Curve= 0 ,0
Exp/Cntr=0.3,0.1