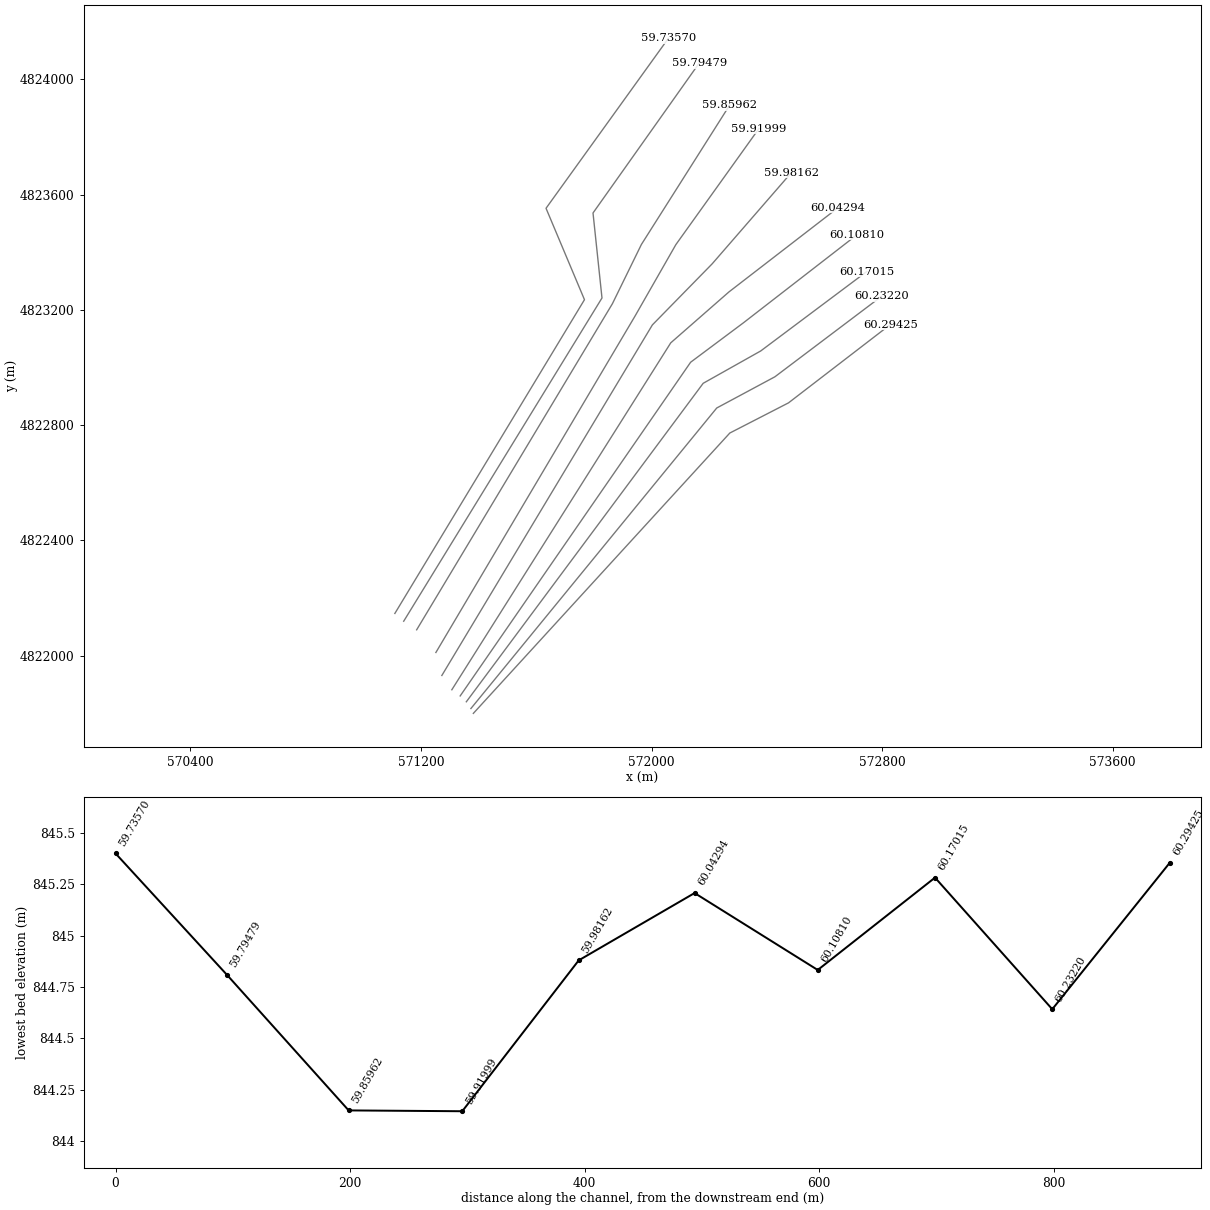
HEC-RAS study Boise2.prj: BoiseRiver_All_reaches

--- Boise2.g01 (geometry) --- (continued)

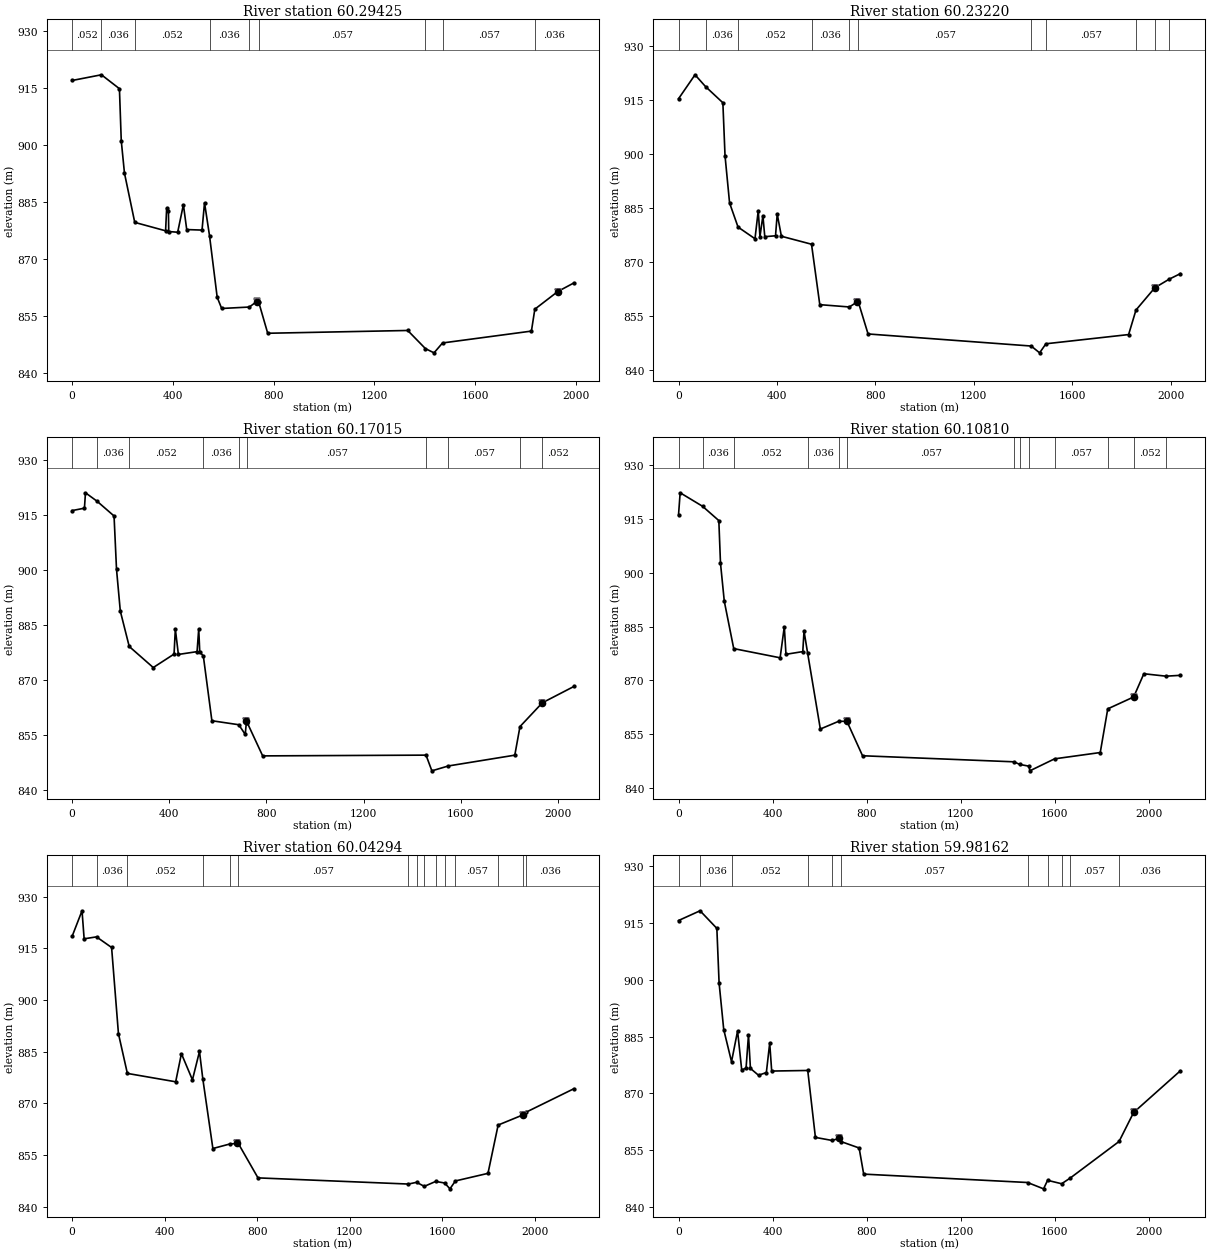
Type RM Length L Ch R = 1 ,60.29425,91.0861,100.0021,100.3761
XS GIS Cut Line= 4
        571381.7      4821800.03       572271.41       4822772.6
       572475.08      4822877.29       572827.83      4823148.61
#Sta/Elev= 30
       0916.9429116.5409 918.445188.0549914.7871 195.279 901.114208.0391892.5909
 248.821879.6461371.3089877.4321375.5139883.3561382.5331882.6551383.8011877.2421
419.2899 877.055441.9508884.2919 455.206  877.76515.9639877.6201525.8782884.8052
 545.653876.1689 576.119859.9679593.9321 857.015703.8301857.3929 733.175 858.843
 740.486858.7941 776.728850.49991332.578851.23211403.079846.45091436.997845.3539
1470.812847.95091823.667851.06811837.171 856.8261928.305861.46731992.161863.7279
#Mann= 9 ,-1 , 0
       0    .052       0116.5409    .036       0 248.821    .052       0
 545.653    .036       0703.8301    .026       0 740.486    .057       0
1403.079    .037       01470.812    .057       01837.171    .036       0
Levee=-1,733.175,858.9539,-1,1928.305,861.4715,,
Bank Sta=733.175,1928.305
XS Rating Curve= 0 ,0
Exp/Cntr=0.3,0.1

Type RM Length L Ch R = 1 ,60.23220,88.6041,100.0021,102.3759
BEGIN DESCRIPTION:
PROJECT XS "CL"
END DESCRIPTION:
XS GIS Cut Line= 4
       571373.23      4821816.82       572226.07      4822859.45
       572427.85      4822967.72       572797.76      4823246.87
#Sta/Elev= 30
       0915.4321 67.0209922.1041109.7201918.8168 180.174914.3101188.9559899.5471
 207.421 886.402 241.874 879.675310.7119876.4241323.9759 884.258330.8951876.9919
342.8781 882.851 350.542 877.001 394.196877.2501 401.061883.3018 418.056 877.119
540.4431   874.9574.0959858.0641694.2149 857.421 724.095858.7327730.9241858.7429
770.2759849.90191433.297846.53691467.488 844.6421493.255847.16911829.226849.7321
1859.125856.56121935.807862.77781935.962862.7841 1993.93865.15412039.409866.6979
#Mann= 11 ,-1 , 0
       0    .052       0109.7201    .036       0 241.874    .052       0
540.4431    .036       0694.2149    .026       0730.9241    .057       0
1433.297    .037       01493.255    .057       01859.125    .036       0
1935.807    .052       0 1993.93    .036       0
Levee=-1,724.095,858.6917,-1,1935.962,862.7791,,
Bank Sta=724.095,1935.962
XS Rating Curve= 0 ,0
Exp/Cntr=0.3,0.1

Type RM Length L Ch R = 1 ,60.17015,76.4121,100.0119,115.119
XS GIS Cut Line= 4
       571357.32      4821840.23       572179.04      4822945.14
       572378.67      4823057.35       572746.75      4823332.96
#Sta/Elev= 30
       0916.2919 50.9321916.9509 55.1581921.1501 102.877 918.844 172.824914.8179
 182.948900.2701198.5921 888.863235.2949 879.213334.1739873.4642419.8391877.1388
 425.071 883.962 437.605 877.041514.5719877.8051521.3561884.0279525.5499877.7859
 540.415876.5789 575.556 858.952686.0539857.8651712.8979855.2249717.9564858.9276
 720.759 858.464784.6061849.36211457.012849.5682 1481.12 845.2831548.941846.6149
1822.461849.55991843.731857.35491935.866863.85191935.891863.85172065.556868.2981
#Mann= 10 ,-1 , 0
       0    .052       0 102.877    .036       0235.2949    .052       0
 540.415    .036       0686.0539    .026       0 720.759    .057       0
1457.012    .037       01548.941    .057       01843.731    .036       0
1935.866    .052       0
Levee=-1,717.9564,858.9233,-1,1935.891,863.855,,
Bank Sta=717.9564,1935.891
XS Rating Curve= 0 ,0
Exp/Cntr=0.3,0.1

Type RM Length L Ch R = 1 ,60.10810,91.6561,105.0131,116.654
XS GIS Cut Line= 4
       571336.05      4821860.55       572135.43      4823018.16
       572318.91      4823155.19       572713.28      4823460.92
#Sta/Elev= 30
       0916.1481  6.9071922.2761102.0431918.5209  171.45 914.532 178.475902.6671
 194.627892.0828 234.828 878.878 432.164 876.318450.0211884.9719457.0531877.2891
528.6329878.0432 533.866883.7441549.0701877.6819603.3071856.4771681.4271 858.635
716.1794858.6205 717.505858.4592782.8068849.03411427.325847.34491451.875 846.614
1490.942 846.1291494.457844.83311599.817 848.1741794.118849.93211826.105862.0981
1936.261865.40491936.321865.40971979.646871.87492073.955871.19712134.797871.4321
#Mann= 13 ,-1 , 0
       0    .052       0102.0431    .036       0 234.828    .052       0
549.0701    .036       0681.4271    .026       0 717.505    .057       0
1427.325    .037       01451.875    .057       01490.942    .037       0
1599.817    .057       01826.105    .036       01936.261    .052       0
2073.955    .036       0
Levee=-1,716.1794,858.6307,-1,1936.321,865.3973,,
Bank Sta=716.1794,1936.321
XS Rating Curve= 0 ,0
Exp/Cntr=0.3,0.1

Type RM Length L Ch R = 1 ,60.04294,85.016,98.8201,116.8871
XS GIS Cut Line= 4
       571307.05      4821881.95       572066.54      4823085.52
       572268.07      4823261.86       572646.85      4823554.21
#Sta/Elev= 30
       0918.4739  43.057 925.933  52.165 917.797 105.651918.3591170.8849915.2781
200.5179890.2501 239.072 878.718447.9591876.2869472.7671884.4461  520.39876.8481
550.8339885.0831565.1379877.1852 608.795856.9141680.7681858.2059714.1373858.4094
719.1671858.3229803.8369848.38791454.172846.59781489.317847.09991522.943845.9249
1572.189847.36291610.805846.90121633.757845.20791657.231847.49791798.109 849.701
1842.067863.72791950.165866.69851950.321866.70521963.555867.48222169.434874.2691
#Mann= 15 ,-1 , 0
       0    .052       0 105.651    .036       0 239.072    .052       0
565.1379    .036       0680.7681    .026       0719.1671    .057       0
1454.172    .037       01489.317    .057       01522.943    .037       0
1572.189    .057       01610.805    .037       01657.231    .057       0
1842.067    .036       01950.321    .052       01963.555    .036       0
Levee=-1,714.1373,858.5546,-1,1950.165,866.711,,
Bank Sta=714.1373,1950.165
XS Rating Curve= 0 ,0
Exp/Cntr=0.3,0.1

Type RM Length L Ch R = 1 ,59.98162,67.6891,99.3291,145.3021
XS GIS Cut Line= 4
       571272.41      4821931.47       572002.82      4823147.75
       572210.28      4823359.66       572484.71      4823675.68
#Sta/Elev= 30
       0 915.571 91.5421918.1381162.9351913.5029172.4409 899.153192.1831 886.847
 225.335 878.379251.0948886.4681268.6839876.1689287.2039876.7139 297.444 885.444
 305.779876.6021340.1071874.8049373.4861875.5209387.7129883.2851396.1461 875.912
549.4669 876.065 582.082 858.429652.9581857.6279684.2303858.2019691.3681857.3259
 767.957855.6449787.3569848.76011484.307846.54791552.245  844.881569.447 847.123
1628.982 846.222 1664.83847.68381873.308 857.3531935.352865.00722133.851 875.973
#Mann= 11 ,-1 , 0
       0    .052       0 91.5421    .036       0 225.335    .052       0
549.4669    .036       0652.9581    .026       0691.3681    .057       0
1484.307    .037       01569.447    .057       01628.982    .037       0
 1664.83    .057       01873.308    .036       0
Levee=-1,684.2303,858.2528,-1,1935.352,865.0102,,
Bank Sta=684.2303,1935.352
XS Rating Curve= 0 ,0
Exp/Cntr=0.3,0.1

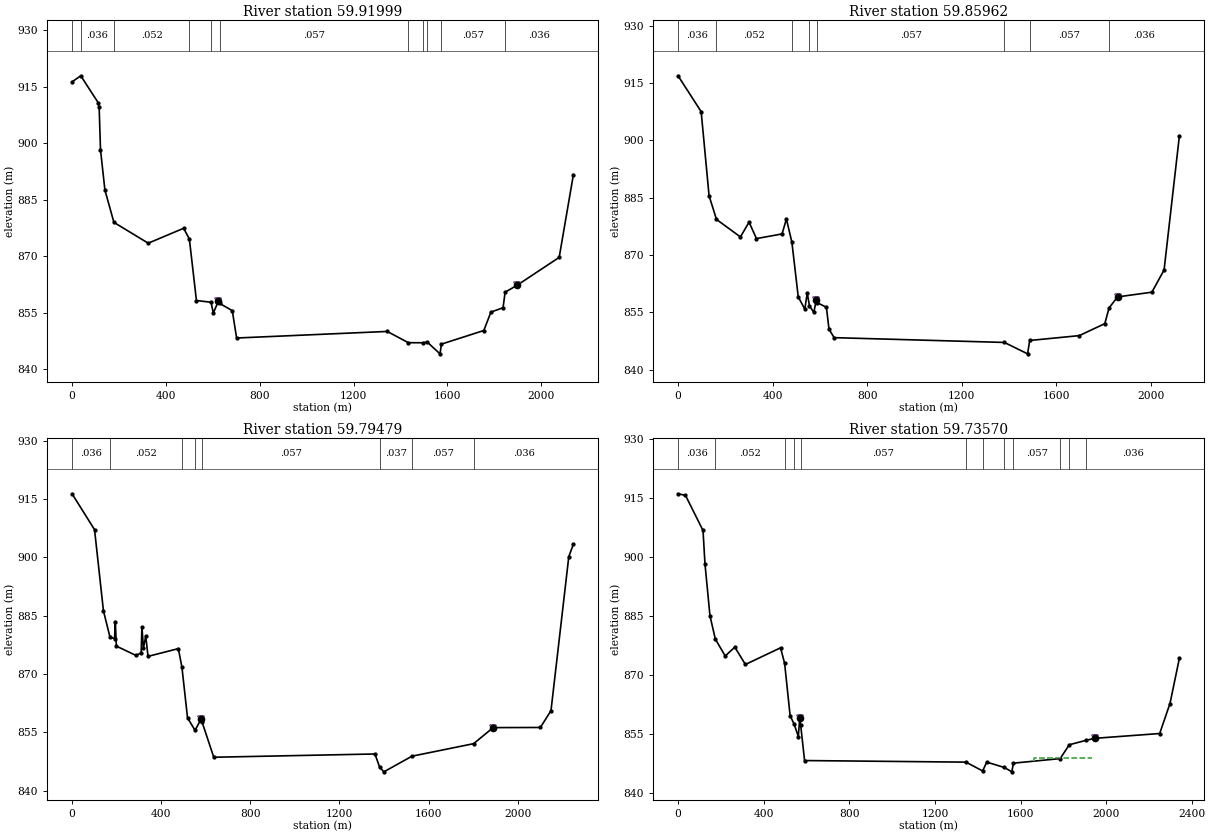
Type RM Length L Ch R = 1 ,59.91999,95.8989,96.8721,103.9999
BEGIN DESCRIPTION:
PROJECT XS "CK"
END DESCRIPTION:
XS GIS Cut Line= 4
       571251.73      4822011.26       571942.06      4823177.39
       572084.32      4823426.34        572372.6      4823829.01
#Sta/Elev= 30
       0 916.231 37.1859917.8519111.0969910.7469115.5591909.4869121.2628898.2542
 140.009887.5901178.4479 878.992324.7111873.4739475.7879 877.428 500.082 874.569
530.2081858.2811592.6181857.8182602.1321854.9439623.9286858.1317 629.162857.5091
682.9589 855.598 701.525 848.3411343.386 850.0821433.567847.09811497.253847.0801
1513.281847.31291568.356844.14511574.616846.72191755.071 850.3251785.551 855.217
 1837.17 856.3631846.028860.48211897.255862.3295 2076.42 869.7092137.101891.6659
#Mann= 11 ,-1 , 0
       0    .052       0 37.1859    .036       0178.4479    .052       0
 500.082    .036       0592.6181    .026       0 629.162    .057       0
1433.567    .037       01497.253    .057       01513.281    .037       0
1574.616    .057       01846.028    .036       0
Levee=-1,623.9286,858.1614,-1,1897.255,862.3249,,
Bank Sta=623.9286,1897.255
XS Rating Curve= 0 ,0
Exp/Cntr=0.3,0.1

Type RM Length L Ch R = 1 ,59.85962,48.651,104.0179,204.287
XS GIS Cut Line= 4
       571185.02      4822089.96       571864.08      4823221.14
       571964.73      4823426.83       572270.96      4823910.25
#Sta/Elev= 30
       0916.9219 97.7771 907.545 131.242 885.511 162.651 879.319263.7669874.7501
300.4081878.6101331.7141874.3099439.9489 875.531 458.389879.4479481.5901 873.338
508.3589859.0788536.1349 855.833546.4951860.0551 555.811 856.731574.1329 854.981
 584.899858.2567589.3171857.5219627.4969856.3359 638.478850.5989 660.191848.3861
1380.303847.13311478.474844.14911487.394847.64611696.882 848.9151805.117852.0529
1823.076856.17711859.228859.05272004.172 860.2842055.782866.09712120.607901.2479
#Mann= 8 ,-1 , 0
       0    .036       0 162.651    .052       0481.5901    .036       0
 555.811    .026       0589.3171    .057       01380.303    .037       0
1487.394    .057       01823.076    .036       0
Levee=-1,584.899,858.2253,-1,1859.228,859.0513,,
#XS Ineff= 1 ,-1
 1798.32 1844.04 848.868
Permanent Ineff=
       T
Bank Sta=584.899,1859.228
XS Rating Curve= 0 ,0
Exp/Cntr=0.3,0.1

Type RM Length L Ch R = 1 ,59.79479,55.1021,94.8041,148.099
XS GIS Cut Line= 4
       571140.08      4822119.74       571827.96      4823241.11
       571796.84        4823536.       572165.58      4824056.54
#Sta/Elev= 30
       0916.3541 100.993907.1199 140.863886.2499 170.549879.4099190.5869 879.095
 194.257  883.49198.8799877.1589 287.028 874.758310.1639875.4179313.5551 882.108
320.3829876.6801330.7041 879.733340.9301 874.516476.8919876.5121 492.971 871.813
518.2359858.7009551.9212855.5002 579.181858.3567583.4201857.6438 635.996 848.566
  1359.3849.40691380.589 845.984 1399.32844.81081525.488848.83511802.236852.0611
1889.629856.18772101.794856.22712149.352860.55192229.236 900.1642249.982903.3961
#Mann= 8 ,-1 , 0
       0    .036       0 170.549    .052       0 492.971    .036       0
551.9212    .026       0583.4201    .057       01380.589    .037       0
1525.488    .057       01802.236    .036       0
Levee=-1,579.181,858.3839,-1,1889.629,856.1924,,
#XS Ineff= 1 ,-1
 1706.88 1874.52 848.868
Permanent Ineff=
       T
Bank Sta=579.181,1889.629
XS Rating Curve= 0 ,0
Exp/Cntr=0.3,0.1

Type RM Length L Ch R = 1 ,59.73570,66.5019,98.828,107.3969
XS GIS Cut Line= 4
       571109.41      4822146.69       571767.21      4823235.18
       571633.84       4823552.3       572058.27      4824141.88
#Sta/Elev= 30
       0916.0008 34.7149915.5991116.6771906.6779 125.869898.1841149.0981885.0411
174.0329 879.131 220.254874.8129265.1471877.0611314.7371 872.661478.8701 876.894
497.9731 872.935523.5769859.6552543.1789857.4271561.9658 854.355568.6806 859.091
572.9261857.2549 591.141 848.2691345.182 847.8631422.947845.62191442.104847.8671
1524.368846.51011559.526845.40091566.764847.6061  1785.3848.7631 1827.93  852.28
1906.397853.40191946.057853.90912250.243855.13012298.263862.75012342.299874.2582
#Mann= 12 ,-1 , 0
       0    .036       0174.0329    .052       0497.9731    .036       0
543.1789    .026       0572.9261    .057       01345.182    .037       0
1422.947    .057       01524.368    .037       01566.764    .057       0
  1785.3    .036       0 1827.93    .046       01906.397    .036       0
Levee=-1,568.6806,859.0574,-1,1946.057,853.9155,,
#XS Ineff= 1 ,-1
 1661.16 1935.48 848.868
Permanent Ineff=
       T
Bank Sta=568.6806,1946.057
XS Rating Curve= 0 ,0
Exp/Cntr=0.3,0.1