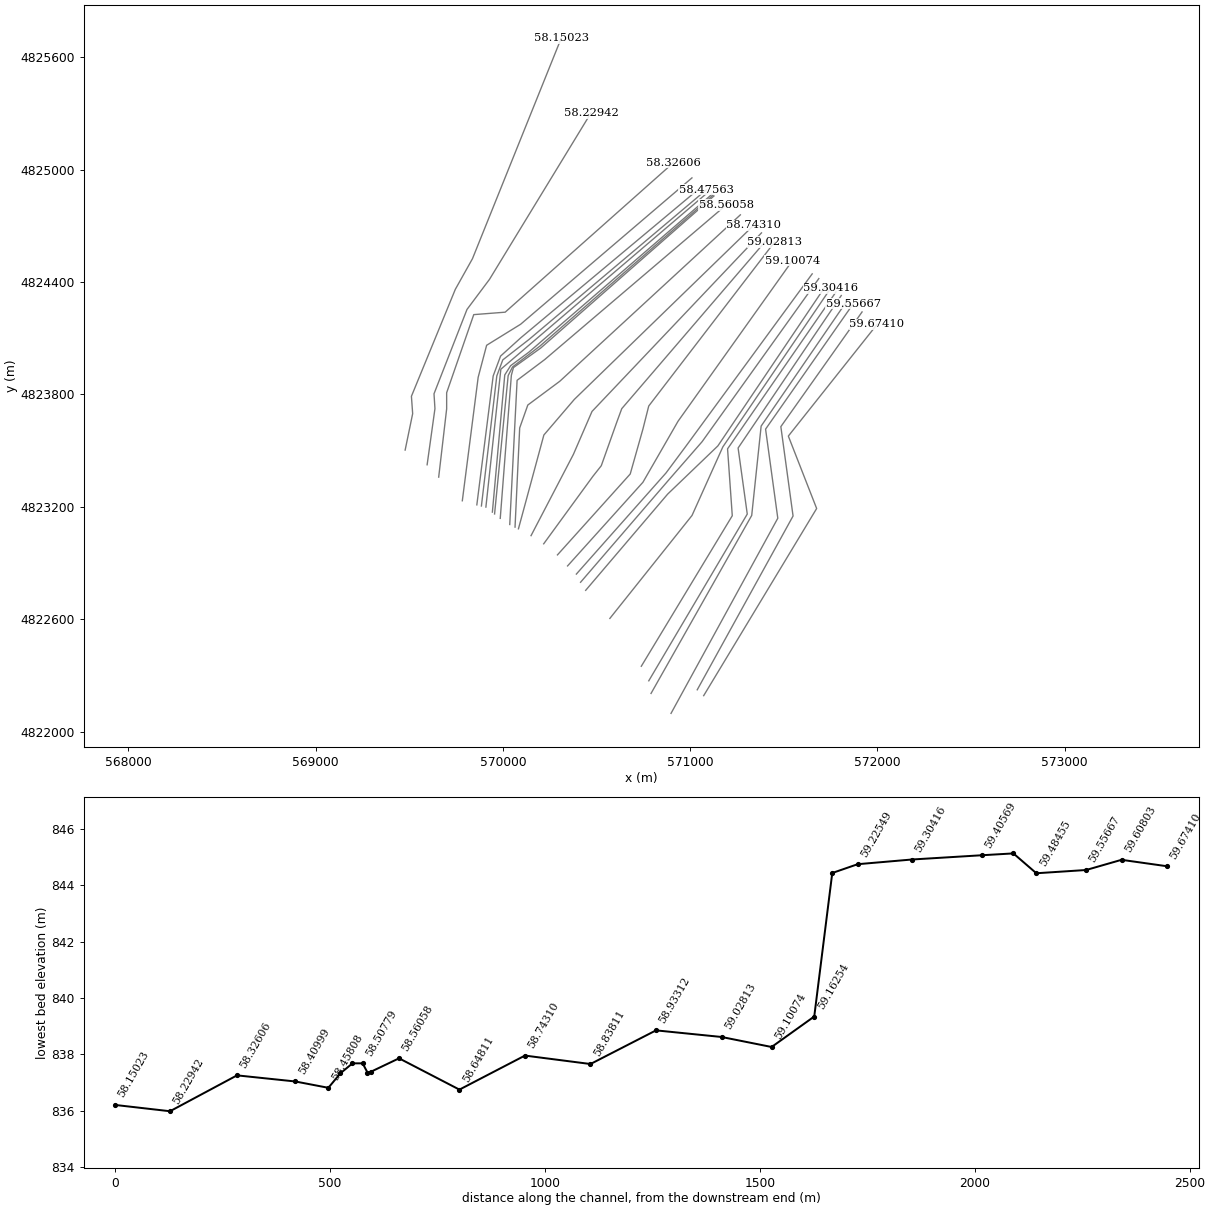
HEC-RAS study Boise2.prj: BoiseRiver_All_reaches

--- Boise2.g01 (geometry) --- (continued)

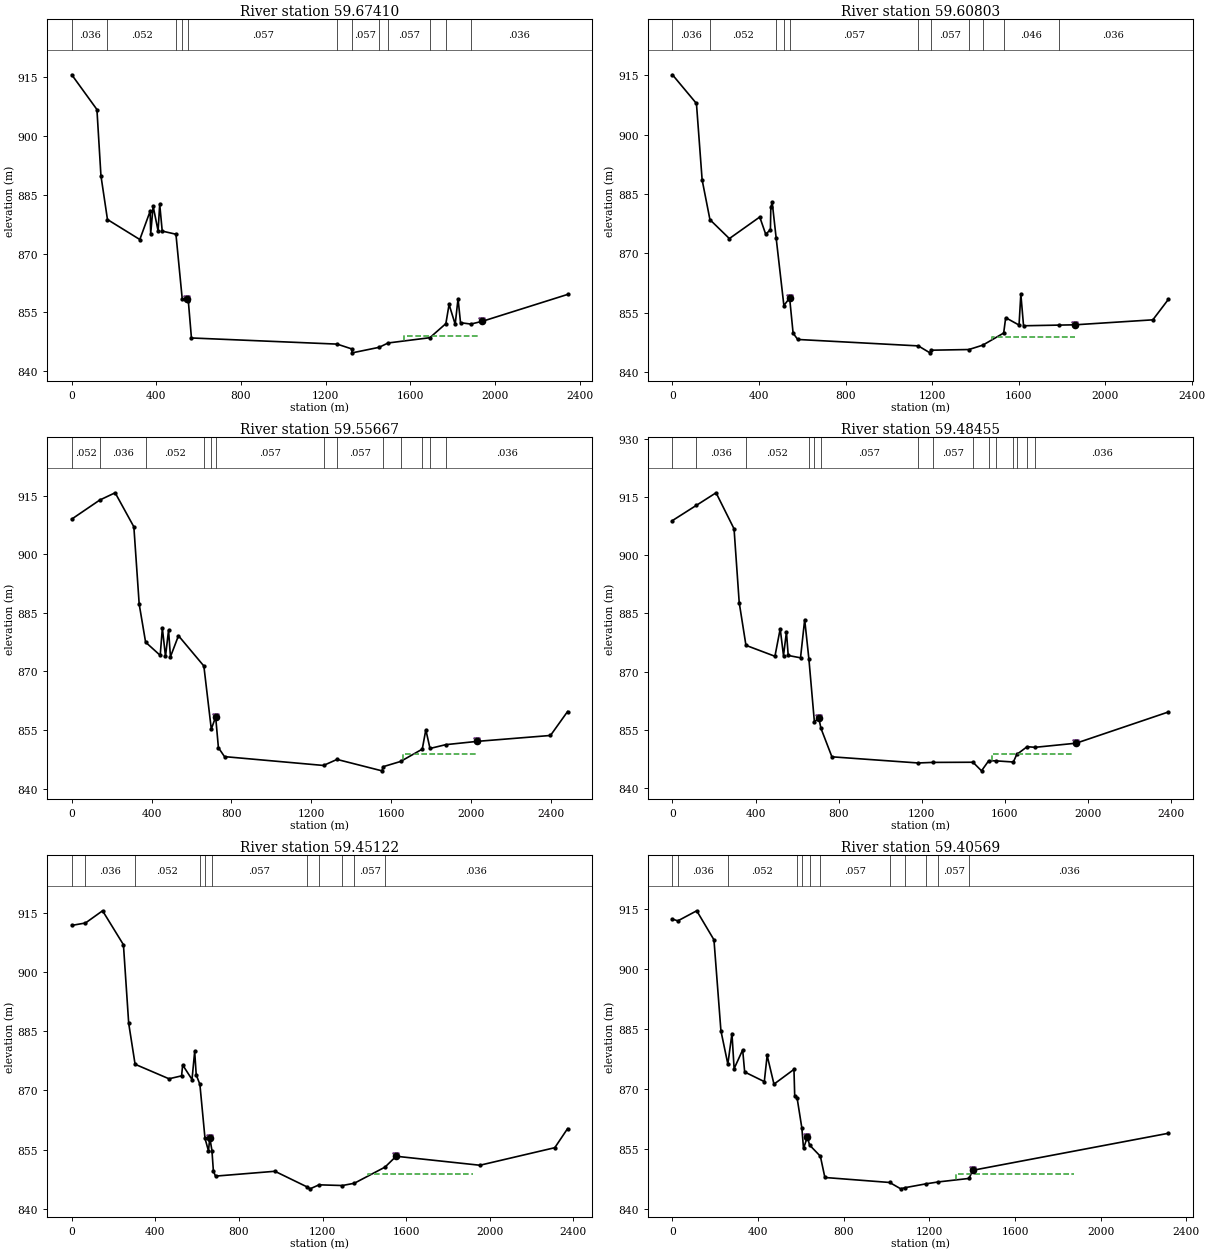
Type RM Length L Ch R = 1 ,59.67410,99.6821,106.0049,73.846
XS GIS Cut Line= 4
        571072.2      4822191.59       571675.33      4823190.73
       571524.18      4823577.49       571997.82      4824173.54
#Sta/Elev= 30
       0915.6091118.9132906.7449137.9071889.8459168.7419878.6772 321.614873.5769
 370.531880.8199372.9771  875.05 384.596882.0931407.9989 875.769415.6841882.5579
 427.549 875.727492.3971874.9299522.1611858.3808544.0467858.3743550.9879857.8651
565.6171848.45981254.312846.89291322.278845.68711325.646844.66611452.818 846.076
1495.238847.18211692.572 848.5261768.271852.12291783.463857.00591812.302851.9581
1825.854858.47991837.536 852.3581886.156 852.0051940.729852.71232343.633859.5659
#Mann= 12 ,-1 , 0
       0    .036       0168.7419    .052       0492.3971    .036       0
522.1611    .026       0550.9879    .057       01254.312    .037       0
1322.278    .057       01452.818    .037       01495.238    .057       0
1692.572    .036       01768.271    .046       01886.156    .036       0
Levee=-1,544.0467,858.393,-1,1940.729,852.7146,,
#XS Ineff= 1 ,-1
 1569.72 1920.24 848.868
Permanent Ineff=
       T
Bank Sta=544.0467,1940.729
XS Rating Curve= 0 ,0
Exp/Cntr=0.3,0.1

Type RM Length L Ch R = 1 ,59.60803,77.101,82.4161,68.95
BEGIN DESCRIPTION:
PROJECT XS "CJ"
END DESCRIPTION:
XS GIS Cut Line= 4
       571037.82      4822222.91       571549.37      4823150.72
       571484.17      4823627.87       571917.77      4824240.24
#Sta/Elev= 30
       0915.0958 110.825 907.848137.1021888.5599 173.231 878.514262.9391873.7409
 403.379879.1862430.8961874.8422452.7429  875.99454.4681881.6151 460.828 882.923
479.3642 873.804514.8809856.8431541.4611858.7261541.4833858.7173557.5579  849.85
578.8749848.27181136.084846.64811189.965 844.8941194.515845.55791369.808845.7301
1433.968 846.8321530.666849.89221539.932853.76621601.711851.90411609.953 859.739
1622.495 851.7271784.096 851.8941859.277851.96842220.029853.22782291.416 858.368
#Mann= 11 ,-1 , 0
       0    .036       0 173.231    .052       0479.3642    .036       0
514.8809    .026       0541.4611    .057       01136.084    .037       0
1194.515    .057       01369.808    .037       01433.968    .057       0
1530.666    .046       01784.096    .036       0
Levee=-1,541.4833,858.6795,-1,1859.277,851.9647,,
#XS Ineff= 1 ,-1
 1478.28 1859.28 848.868
Permanent Ineff=
       T
Bank Sta=541.4833,1859.277
XS Rating Curve= 0 ,0
Exp/Cntr=0.3,0.1

Type RM Length L Ch R = 1 ,59.55667,149.1679,115.7179,34.4589
XS GIS Cut Line= 4
       570897.85      4822096.99       571467.87      4823138.86
       571402.67      4823614.54       571870.32      4824283.38
#Sta/Elev= 30
       0 908.984140.3369913.8611217.2901 915.718311.0341907.0001 337.744887.2051
369.8449877.4741  443.05 874.089453.8051881.0728469.5091 873.832 484.877 880.533
494.3579 873.736 534.533 879.124661.6971871.3729 698.954 855.213720.7392858.3294
 720.812 858.332734.6061  850.46765.1221848.17221261.049845.90991328.858847.4559
1553.593844.53311560.849845.60911647.038 846.9311755.831  850.091773.685855.0521
1794.579  850.261873.565851.23382032.373852.08442398.131  853.592483.846 859.721
#Mann= 13 ,-1 , 0
       0    .052       0140.3369    .036       0369.8449    .052       0
661.6971    .036       0 698.954    .026       0 720.812    .057       0
1261.049    .037       01328.858    .057       01560.849    .037       0
1647.038    .057       01755.831    .036       01794.579    .046       0
1873.565    .036       0
Levee=-1,720.7392,858.3351,-1,2032.373,852.0867,,
#XS Ineff= 1 ,-1
 1661.16 2026.92 848.868
Permanent Ineff=
       T
Bank Sta=720.7392,2032.373
XS Rating Curve= 0 ,0
Exp/Cntr=0.3,0.1

Type RM Length L Ch R = 1 ,59.48455,29.3041,53.4671,48.4979
XS GIS Cut Line= 4
       570791.12      4822203.45       571328.58      4823153.68
       571378.96      4823630.84       571840.87      4824304.54
#Sta/Elev= 30
       0908.9559114.1631912.8409209.9709916.1169 296.646906.8151 321.485 887.805
353.9521876.7792493.6181 873.957518.9611881.0469 534.835 874.128548.9881 880.231
557.5499 874.167616.8439 873.562  636.84883.4119 657.272 873.206683.5438857.0881
705.1761857.9883715.0699855.4081768.0201848.03411183.424 846.4461253.402846.5939
1447.574846.63381488.642844.41791523.285847.02191558.871846.99021641.985846.6951
1658.465848.64091708.382 850.6451746.595 850.4811944.639851.54822388.342 859.586
#Mann= 15 ,-1 , 0
       0    .052       0114.1631    .036       0353.9521    .052       0
 657.272    .036       0683.5438    .026       0715.0699    .057       0
1183.424    .037       01253.402    .057       01447.574    .037       0
1523.285    .057       01558.871    .026       01641.985    .057       0
1658.465    .036       01708.382    .046       01746.595    .036       0
Levee=-1,705.1761,858.012,-1,1944.639,851.5472,,
#XS Ineff= 1 ,-1
 1539.24 1935.48 848.868
Permanent Ineff=
       T
Bank Sta=705.1761,1944.639
XS Rating Curve= 0 ,0
Exp/Cntr=0.3,0.1

Type RM Length L Ch R = 1 ,59.45122,72.158,73.052,73.6189
XS GIS Cut Line= 4
       570779.08      4822270.92       571304.87      4823161.09
       571255.97      4823513.77       571806.71      4824327.85
#Sta/Elev= 30
       0911.7541  65.489912.3621147.4049915.4518247.2151906.8699  272.44886.9811
303.0041876.6279465.2839872.9578525.5471873.6992 530.683876.4551 575.467 872.775
588.2052879.8759595.5359873.9531613.1259871.5461 637.566 857.877  654.23 854.725
660.5046858.0219 670.785854.8171 677.746849.5989687.8619848.3389 972.137849.5621
1123.985845.66091140.241845.12111183.305846.13481294.825845.95991352.007846.5311
1499.113850.61911552.157853.36081953.075851.0891 2311.46855.52692372.779860.3559
#Mann= 11 ,-1 , 0
       0    .052       0  65.489    .036       0303.0041    .052       0
613.1259    .036       0 637.566    .026       0 670.785    .057       0
1123.985    .037       01183.305    .057       01294.825    .037       0
1352.007    .057       01499.113    .036       0
Levee=-1,660.5046,858.0151,-1,1552.157,853.3882,,
#XS Ineff= 1 ,-1
 1417.32 1920.24 848.868
Permanent Ineff=
       T
Bank Sta=660.5046,1552.157
XS Rating Curve= 0 ,0
Exp/Cntr=0.3,0.1

Type RM Length L Ch R = 1 ,59.40569,196.9481,162.9089,54.1011
XS GIS Cut Line= 4
       570739.09      4822348.52       571224.85       4823152.2
       571199.66      4823509.32       571778.53      4824347.07
#Sta/Elev= 30
       0912.5109 25.0061912.0579113.2301914.5801193.7489907.3149226.2881884.5671
 258.628876.2411 277.785 883.871287.8922875.1119327.8551879.7921337.1429874.2731
428.8691 871.864442.0911878.4058 474.031871.2299 567.338874.9229 570.845 868.335
582.0869867.7491604.3151860.2331 612.007855.1679630.1252858.0525639.9721856.0229
 690.679853.2028711.7352847.89391014.369 846.6461066.079845.05621086.609 845.353
 1184.55846.31291242.203846.78991384.367 847.6541403.443849.70812315.383858.9429
#Mann= 12 ,-1 , 0
       0    .052       0 25.0061    .036       0 258.628    .052       0
582.0869    .036       0604.3151    .026       0639.9721    .036       0
 690.679    .057       01014.369    .037       01086.609    .057       0
 1184.55    .037       01242.203    .057       01384.367    .036       0
Levee=-1,630.1252,858.0486,-1,1403.443,849.6848,,
#XS Ineff= 1 ,-1
 1325.88 1874.52 848.868
Permanent Ineff=
       T
Bank Sta=630.1252,1403.443
XS Rating Curve= 0 ,0
Exp/Cntr=0.3,0.1

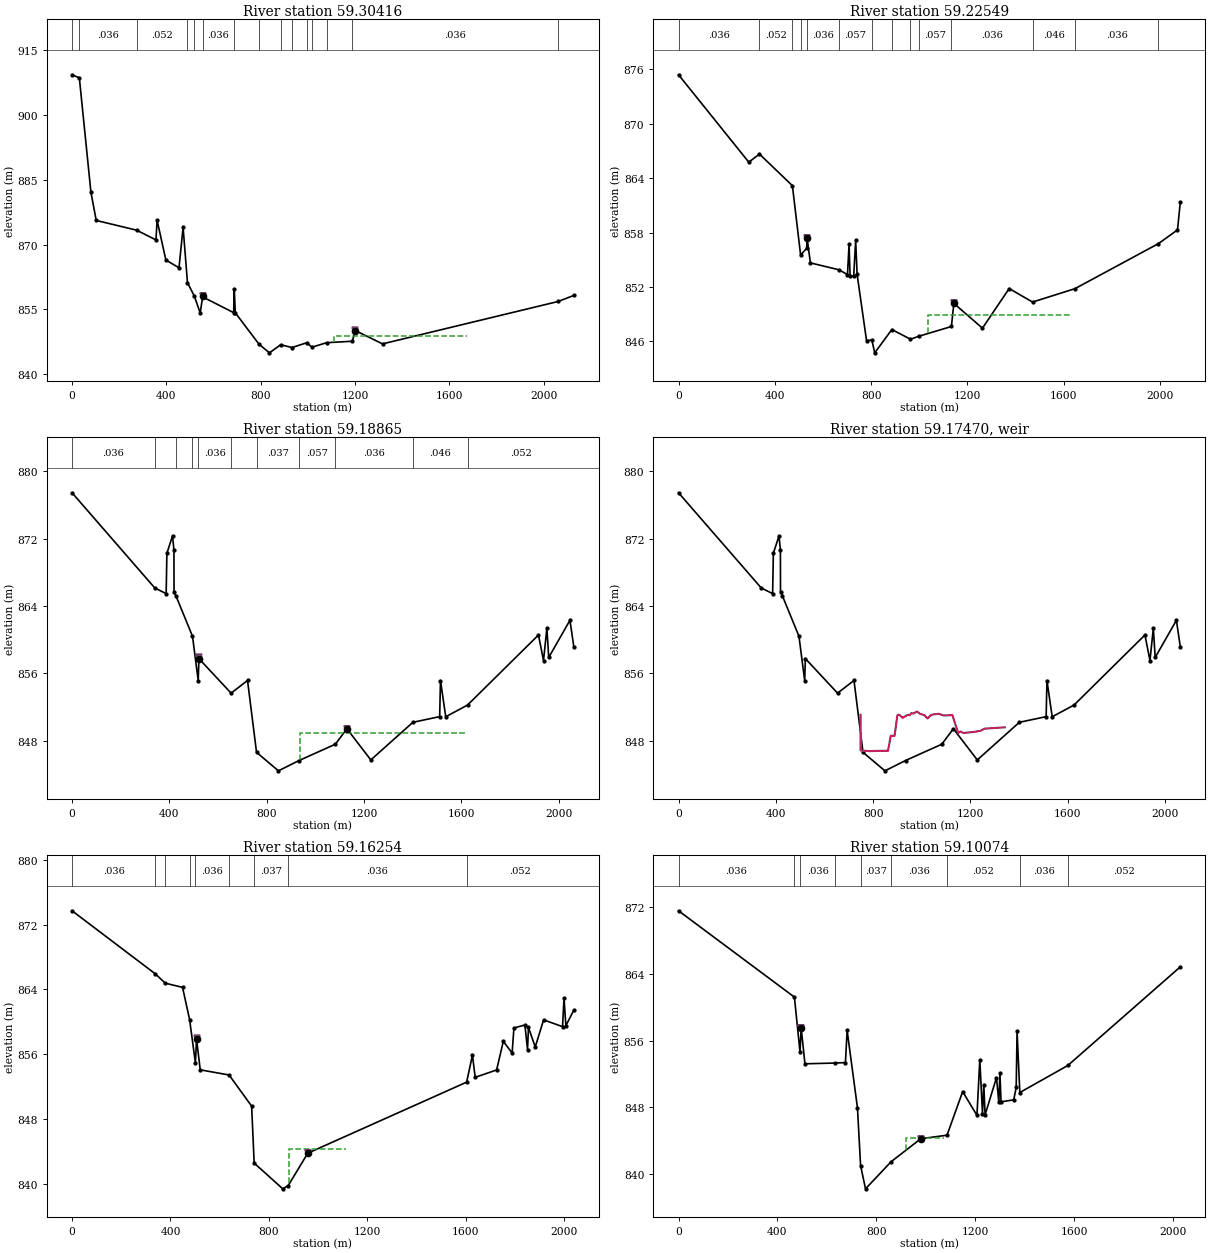
Type RM Length L Ch R = 1 ,59.30416,151.0632,126.2091,44.6791
BEGIN DESCRIPTION:
PROJECT XS "CI"
END DESCRIPTION:
XS GIS Cut Line= 4
       570571.32      4822603.97       571009.98      4823153.68
       571174.47       4823519.7       571750.19      4824366.81
#Sta/Elev= 30
       0909.3671  30.868 908.653  79.975882.1461102.4311875.5999273.7631873.3419
 356.007871.0809 360.661875.6511397.9399 866.426   453.6864.6191471.0199 873.965
489.6231861.1779 518.787858.0532543.5349854.1481554.2331857.9821556.0408 857.816
 685.472854.2209687.9641859.7771692.5562854.1801793.6151846.8701837.4069 844.905
884.7271846.7759 933.264846.1379 995.212847.23491018.203 846.2191079.938 847.259
1188.719847.59181201.991850.05941317.017846.98192062.164856.81112128.796 858.215
#Mann= 15 ,-1 , 0
       0    .052       0  30.868    .036       0273.7631    .052       0
489.6231    .036       0 518.787    .026       0556.0408    .036       0
 685.472    .057       0793.6151    .037       0884.7271    .057       0
 933.264    .037       0 995.212    .057       01018.203    .037       0
1079.938    .057       01188.719    .036       02062.164    .052       0
Levee=-1,554.2331,857.9937,-1,1201.991,850.1086,,
#XS Ineff= 2 ,-1
 1112.52  1676.4 848.868  563.88  594.36 848.868
Permanent Ineff=
       T       T
Bank Sta=554.2331,1201.991
XS Rating Curve= 0 ,0
Exp/Cntr=0.3,0.1

Type RM Length L Ch R = 1 ,59.22549,54.1081,59.119,108.888
XS GIS Cut Line= 4
       570442.19      4822753.93       570879.58      4823267.41
       571147.98      4823524.98        571727.4      4824385.42
#Sta/Elev= 30
       0875.4011 291.785865.7631336.1261866.6601472.8341863.1729507.0031855.5239
532.0089856.2679 534.098857.3487547.6299 854.657665.3759853.9039701.6459853.3721
 708.175 856.709 712.342 853.241727.3159853.1849 735.614857.1409741.5698853.3979
780.7991846.0778  802.91 846.151 814.674844.7388885.8478 847.308963.1589846.2421
 998.793 846.5751133.202847.64391143.372850.19241262.055847.46011373.107851.8279
 1470.37850.33811646.456851.8179 1993.21 856.7872072.095858.29392083.858861.3792
#Mann= 14 ,-1 , 0
       0    .036       0336.1261    .052       0472.8341    .036       0
507.0031    .026       0532.0089    .036       0665.3759    .057       0
  802.91    .037       0885.8478    .057       0963.1589    .037       0
 998.793    .057       01133.202    .036       0 1470.37    .046       0
1646.456    .036       0 1993.21    .052       0
Levee=-1,534.098,857.4024,-1,1143.372,850.203,,
#XS Ineff= 2 ,-1
 1036.32 1630.68 848.868  548.64  716.28 848.868
Permanent Ineff=
       T       T
Bank Sta=534.098,1143.372
XS Rating Curve= 0 ,0
Exp/Cntr=0.3,0.1

Type RM Length L Ch R = 1 ,59.18865,36.0249,41.8941,70.8459
XS GIS Cut Line= 4
       570414.86      4822796.97       570887.48       4823345.4
       571063.48      4823547.17       571686.91      4824418.32
#Sta/Elev= 30
       0 877.457 339.977866.1523 386.851865.4769389.8349 870.275  413.05872.3379
418.8059870.6469419.2411865.6372426.8279865.2281 495.112860.4142  518.63 855.152
521.5159857.7567 653.754 853.657721.3519  855.16758.3461 846.629848.3989844.4271
 933.286845.65391082.438  847.591129.945849.42721228.184 845.7231401.166850.1912
1511.316 850.8661514.614 855.1571536.196850.85111625.823852.23911917.462860.5629
1938.193 857.5251952.007861.3792 1959.64857.89582046.828 862.3092062.966859.1392
#Mann= 11 ,-1 , 0
       0    .036       0 339.977    .052       0426.8279    .036       0
 495.112    .026       0  518.63    .036       0 653.754    .057       0
758.3461    .037       0 933.286    .057       01082.438    .036       0
1401.166    .046       01625.823    .052       0
Levee=-1,521.5159,857.948,-1,1129.945,849.4349,,
#XS Ineff= 2 ,-1
  937.26 1615.44 848.868   533.4  739.14 848.868
Permanent Ineff=
       T       T
Bank Sta=521.5159,1129.945
XS Rating Curve= 0 ,0
Exp/Cntr=0.5,0.3

Type RM Length L Ch R = 5 ,59.17470,,,
BEGIN DESCRIPTION:
Barber Dam
END DESCRIPTION:
IW Pilot Flow=0
#Inline Weir SE= 30
 748.284 851.087 748.619 846.847  783.22 846.774  861.38  846.82 872.399 848.591
 888.276 848.597 899.636 851.029  902.76  851.09 907.557 851.096  920.81  850.73
 942.984 851.081 950.815 851.038 956.124 851.267  964.54 851.239 981.206 851.471
 990.679 851.2391011.284 851.0231023.966 850.6541038.292 851.0631049.475 851.142
1069.811   851.2 1091.05 850.9991125.934 851.0471149.657 848.9141158.725 849.106
1170.703 848.9351209.072 849.0271241.984 849.1821257.492 849.4381341.727 849.596
IW Dist,WD,Coef,Skew,MaxSub,Min_El,Is_Ogee,SpillHt,DesHd
24.384,4.572,1.93,0,0.98,, 0 ,,,0,1,

Type RM Length L Ch R = 1 ,59.16254,90.7929,99.142,117.02
XS GIS Cut Line= 4
       570392.42      4822840.72       570871.14       4823380.6
       570976.74      4823522.66       571651.55      4824443.48
#Sta/Elev= 30
       0873.6961337.8519 865.916379.0639864.7499449.1981864.2321477.8082860.2611
 501.474 854.907506.1357857.8168 521.108 854.046638.3701853.4089 730.114 849.559
740.3781 842.523856.8681 839.343878.9061839.7529958.3491843.74711604.187852.5241
1627.787  855.851639.035853.1182  1726.1 854.031 1753.34857.56791789.166 856.121
1796.456859.21591841.062 859.5861851.816 856.5561855.606  859.281883.105856.8721
1917.148860.22091994.172859.37812000.135862.90712007.668859.49492040.171861.4301
#Mann= 9 ,-1 , 0
       0    .036       0337.8519    .052       0379.0639    .036       0
477.8082    .026       0 501.474    .036       0638.3701    .057       0
740.3781    .037       0878.9061    .036       01604.187    .052       0
Levee=-1,506.1357,857.9694,-1,958.3491,843.7443,,
#XS Ineff= 2 ,-1
  883.92 1112.52 844.296   533.4  731.52 844.296
Permanent Ineff=
       F       F
Bank Sta=506.1357,958.3491
XS Rating Curve= 0 ,0
Exp/Cntr=0.5,0.3

Type RM Length L Ch R = 1 ,59.10074,104.832,116.5119,148.0551
BEGIN DESCRIPTION:
FEMA XS "BY"
PROJECT XS "CH"
END DESCRIPTION:
XS GIS Cut Line= 5
        570345.5      4822884.21       570747.74      4823330.72
       570804.58      4823429.48       570935.39      4823656.79
       571545.81      4824514.07
#Sta/Elev= 30
       0871.5195 468.641861.1954 491.426854.5961 495.934857.5278511.3136853.2181
634.6939853.3093675.0833853.3671681.8876857.2116723.7348847.9411736.3319841.0517
756.3066838.2631859.6667841.5038979.8863844.25631085.928844.67821149.198849.8934
1206.962847.05541218.515853.65491229.353847.26261234.648850.7416 1239.93847.1227
1286.026851.5615 1295.51848.60381299.958852.0812 1304.46 848.6721355.732848.9036
 1365.72 850.3921369.248857.0982 1380.38849.7842  1574.6853.01542029.582864.8154
#Mann= 9 ,-1 , 0
       0    .036       0 468.641    .026       0 491.426    .036       0
634.6939    .057       0736.3319    .037       0859.6667    .036       0
1085.928    .052       0 1380.38    .036       0  1574.6    .052       0
Levee=-1,495.934,857.5212,-1,979.8863,844.2534,,
#XS Ineff= 2 ,-1
  922.02 1074.42 844.296  518.16   685.8 844.296
Permanent Ineff=
       F       F
Bank Sta=495.934,979.8863
XS Rating Curve= 0 ,0
Exp/Cntr=0.3,0.1

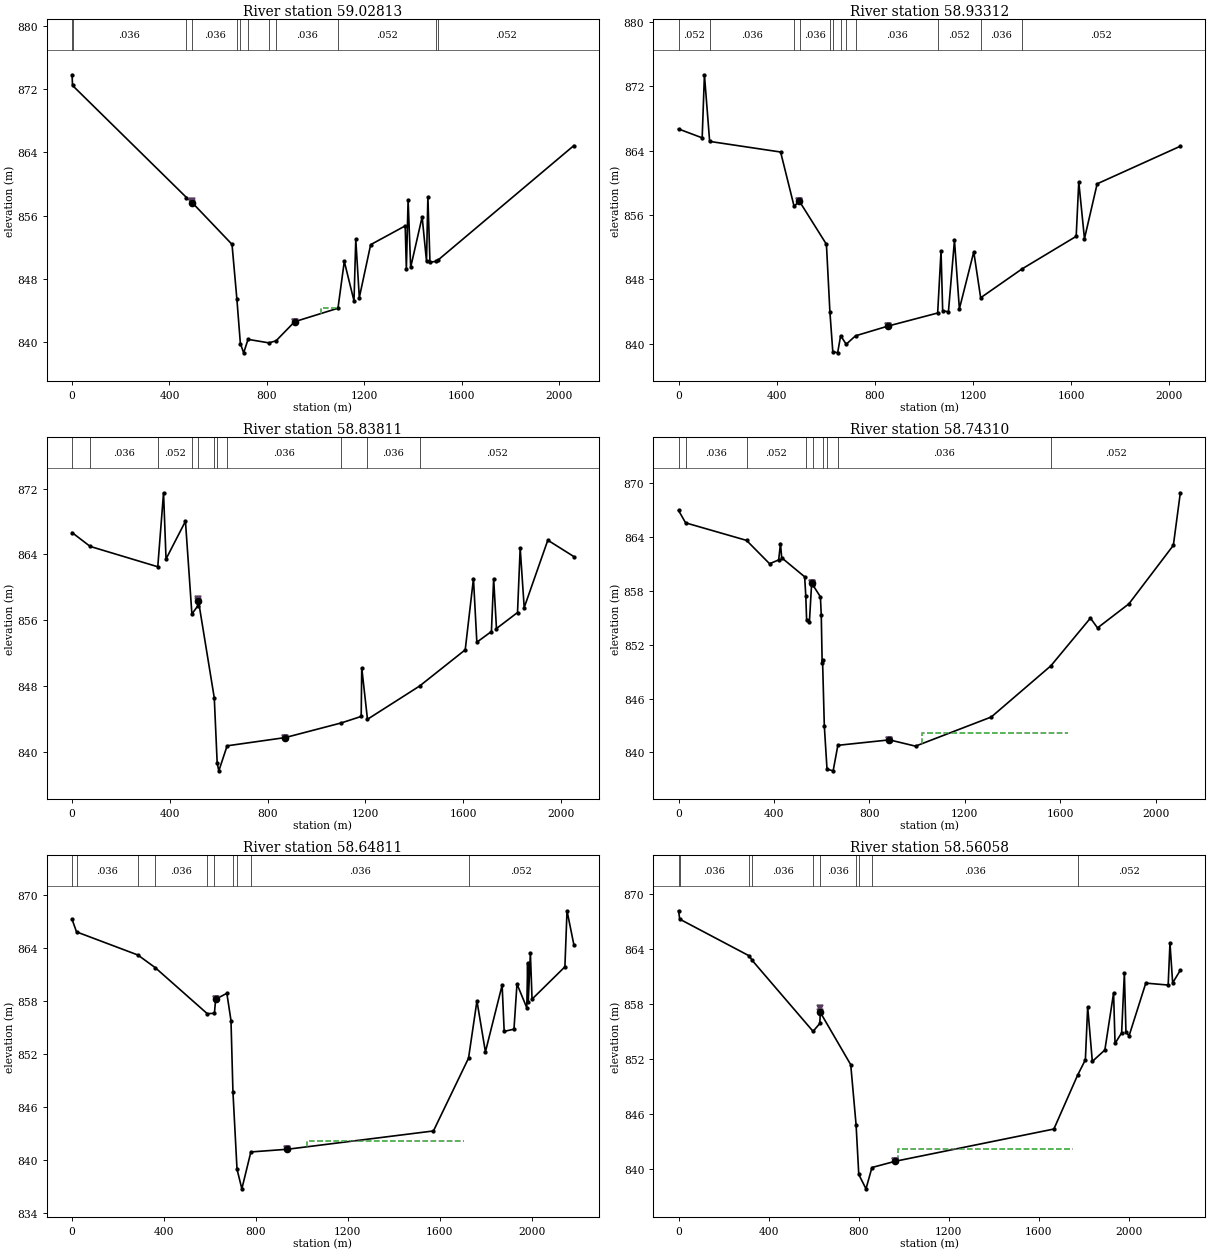
Type RM Length L Ch R = 1 ,59.02813,154.3681,152.439,143.6151
XS GIS Cut Line= 5
       570291.51      4822943.08       570679.99      4823374.97
       570747.97      4823615.55       570778.84      4823738.02
       571450.96      4824613.68
#Sta/Elev= 30
       0873.8421   1.855872.4891469.9208 858.296493.2109857.7709493.5535857.6432
656.9531852.3588 677.058845.3939691.2791839.7932  704.79838.6179722.8131 840.326
807.9349839.8822837.6138 840.134914.3238842.56391092.155844.26791118.158   850.2
1158.015845.19791165.323852.99111179.833 845.6211226.411852.32111368.319854.6992
 1373.05849.19811380.246 858.0271390.757849.44981437.895 855.8321455.833850.2259
1461.473858.37991470.084850.09081493.649 850.2071501.069850.31582061.059864.8721
#Mann= 12 ,-1 , 0
       0    .052       0   1.855    .036       0469.9208    .026       0
493.2109    .036       0 677.058    .057       0691.2791    .037       0
722.8131    .082       0807.9349    .037       0837.6138    .036       0
1092.155    .052       01493.649    .036       01501.069    .052       0
Levee=-1,493.5535,857.8109,-1,914.3238,842.5648,,
#XS Ineff= 2 ,-1
 1021.08 1097.28 844.296  502.92   647.7 844.296
Permanent Ineff=
       F       F
Bank Sta=493.5535,914.3238
XS Rating Curve= 0 ,0
Exp/Cntr=0.3,0.1

Type RM Length L Ch R = 1 ,58.93312,154.615,152.439,145.9901
XS GIS Cut Line= 6
       570218.05      4823002.32       570480.67      4823362.54
        570525.5      4823419.19       570609.32      4823654.71
       570634.76       4823723.8       571418.95      4824637.32
#Sta/Elev= 30
       0866.6838  96.382865.5799 105.537  873.42126.8261865.1361 416.105863.8169
471.0989857.0698492.1545857.7159494.4191 857.614602.8731 852.347617.1539 843.905
 628.814839.0138648.5352838.8519 660.929840.9902683.4311839.9178721.4789840.9669
855.4182842.19141056.341843.80321070.108851.50521076.798 844.0931100.191843.9461
1124.841 852.8351144.874 844.3141203.567851.40091231.648 845.6991399.796 849.274
1621.048 853.3331631.609860.09891654.812 853.0451706.534859.86492045.588 864.539
#Mann= 12 ,-1 , 0
       0    .052       0126.8261    .036       0471.0989    .026       0
494.4191    .036       0617.1539    .082       0 628.814    .037       0
 660.929    .082       0683.4311    .037       0721.4789    .036       0
1056.341    .052       01231.648    .036       01399.796    .052       0
Levee=-1,492.1545,857.759,-1,855.4182,842.1807,,
#XS Ineff= 1 ,-1
  502.92  586.74 844.296
Permanent Ineff=
       F
Bank Sta=492.1545,855.4182
XS Rating Curve= 0 ,0
Exp/Cntr=0.3,0.1

Type RM Length L Ch R = 1 ,58.83811,163.1741,152.439,120.2521
XS GIS Cut Line= 4
        570150.5      4823045.85       570376.53      4823479.61
       570475.95      4823708.99       571380.72      4824662.32
#Sta/Elev= 30
       0866.6461 74.1289 864.963350.7279 862.488 374.335871.4899 384.515 863.435
 463.987 868.024490.3619856.7349514.1821857.7209517.3218858.3213581.9461 846.536
593.8562 838.599600.5941837.6599 634.514 840.704871.9078841.70441102.083843.4929
1183.134 844.2781185.416850.19511208.862 843.9331421.804847.96921608.868852.3821
1642.597 861.0461656.447 853.3081716.067854.61021725.241861.04411736.721854.9719
 1822.88856.92111833.786864.7761 1850.19857.5219 1946.85 865.7212053.443863.7279
#Mann= 11 ,-1 , 0
       0    .052       0 74.1289    .036       0350.7279    .052       0
490.3619    .026       0514.1821    .036       0581.9461    .082       0
593.8562    .037       0 634.514    .036       01102.083    .052       0
1208.862    .036       01421.804    .052       0
Levee=-1,517.3218,858.5668,-1,871.9078,841.693,,
#XS Ineff= 2 ,-1
 1036.32 1112.52842.1624  518.16  541.02 844.296
Permanent Ineff=
       T       F
Bank Sta=517.3218,871.9078
XS Rating Curve= 0 ,0
Exp/Cntr=0.3,0.1

Type RM Length L Ch R = 1 ,58.74310,162.9891,152.4079,129.561
XS GIS Cut Line= 4
       570083.25      4823082.46       570218.93      4823583.13
       570381.44      4823773.11       571339.04      4824702.59
#Sta/Elev= 30
       0866.9161 29.6561 865.535284.9901 863.585381.6011 860.989419.7392 861.413
 427.357863.2341432.3369861.6541528.5829 859.536533.3829857.4119536.8799854.7198
 548.622854.5519557.8693858.7959562.8281 858.628 594.653857.3131 598.212855.2941
602.0681 849.897603.6311850.2661611.0591842.9509622.3501 838.147648.0779837.9589
667.7799 840.796883.9657841.4019993.2441 840.7041310.895 843.9471560.607849.6361
1726.512854.94511756.189853.85211887.742  856.532074.071863.03812103.245 868.879
#Mann= 9 ,-1 , 0
       0    .052       0 29.6561    .036       0284.9901    .052       0
533.3829    .026       0562.8281    .036       0603.6311    .082       0
622.3501    .037       0667.7799    .036       01560.607    .052       0
Levee=-1,557.8693,858.7953,-1,883.9657,841.4034,,
#XS Ineff= 1 ,-1
 1021.08 1630.68842.1624
Permanent Ineff=
       T
Bank Sta=557.8693,883.9657
XS Rating Curve= 0 ,0
Exp/Cntr=0.3,0.1

Type RM Length L Ch R = 1 ,58.64811,140.198,140.4421,141.0651
XS GIS Cut Line= 5
       570065.04      4823091.44       570089.85      4823620.88
       570133.21      4823743.23       570303.91      4823870.06
       571268.02      4824758.62
#Sta/Elev= 30
       0867.2261  19.434865.8109286.0539   863.2361.3889861.7781 588.485 856.559
619.4919 856.609624.7791858.1984673.5782858.8639691.5479855.7891 700.068847.7272
717.7549838.9748 738.845836.7531778.0231840.9249 936.946841.22941572.586 843.299
1725.276851.53111761.855858.00291798.779 852.2431871.461859.78591880.426854.5562
1923.013854.81191936.078859.92491978.869857.22281982.426 862.2531985.133857.9181
 1994.43  863.422001.664 858.2052144.646 861.8612153.848868.19812183.617864.3588
#Mann= 10 ,-1 , 0
       0    .052       0  19.434    .036       0286.0539    .052       0
361.3889    .036       0 588.485    .026       0619.4919    .036       0
 700.068    .082       0717.7549    .037       0778.0231    .036       0
1725.276    .052       0
Levee=-1,624.7791,858.2498,-1,936.946,841.2266,,
#XS Ineff= 1 ,-1
 1021.08 1706.88842.1624
Permanent Ineff=
       T
Bank Sta=624.7791,936.946
XS Rating Curve= 0 ,0
Exp/Cntr=0.3,0.1

Type RM Length L Ch R = 1 ,58.56058,59.735,66.2919,63.2561
XS GIS Cut Line= 4
       570036.79      4823105.36       570076.05      4823875.23
       570223.33      4823985.82       571192.92      4824811.55
#Sta/Elev= 30
       0868.1411  5.3489867.2291314.0089863.2311327.3799 862.733 597.486855.0109
627.5719855.8741629.5735857.0813764.7661851.3798788.4761844.8502800.5109 839.428
832.5911 837.862858.9002 840.184961.2783 840.8581666.999844.37411771.954850.2149
1806.936851.91821817.111857.67221837.742851.7371 1893.44 852.9811932.169 859.183
1938.661853.69511967.903854.8491 1980.09861.36111987.129854.95612000.893 854.519
2075.241860.26512174.607860.05212182.609864.62312194.502860.28612228.593861.6711
#Mann= 10 ,-1 , 0
       0    .052       0  5.3489    .036       0314.0089    .052       0
327.3799    .036       0 597.486    .026       0627.5719    .036       0
788.4761    .082       0800.5109    .037       0858.9002    .036       0
1771.954    .052       0
Levee=-1,629.5735,857.5243,-1,961.2783,840.8517,,
#XS Ineff= 1 ,-1
  975.36  1752.6842.1624
Permanent Ineff=
       T
Bank Sta=629.5735,961.2783
XS Rating Curve= 0 ,0
Exp/Cntr=0.5,0.3

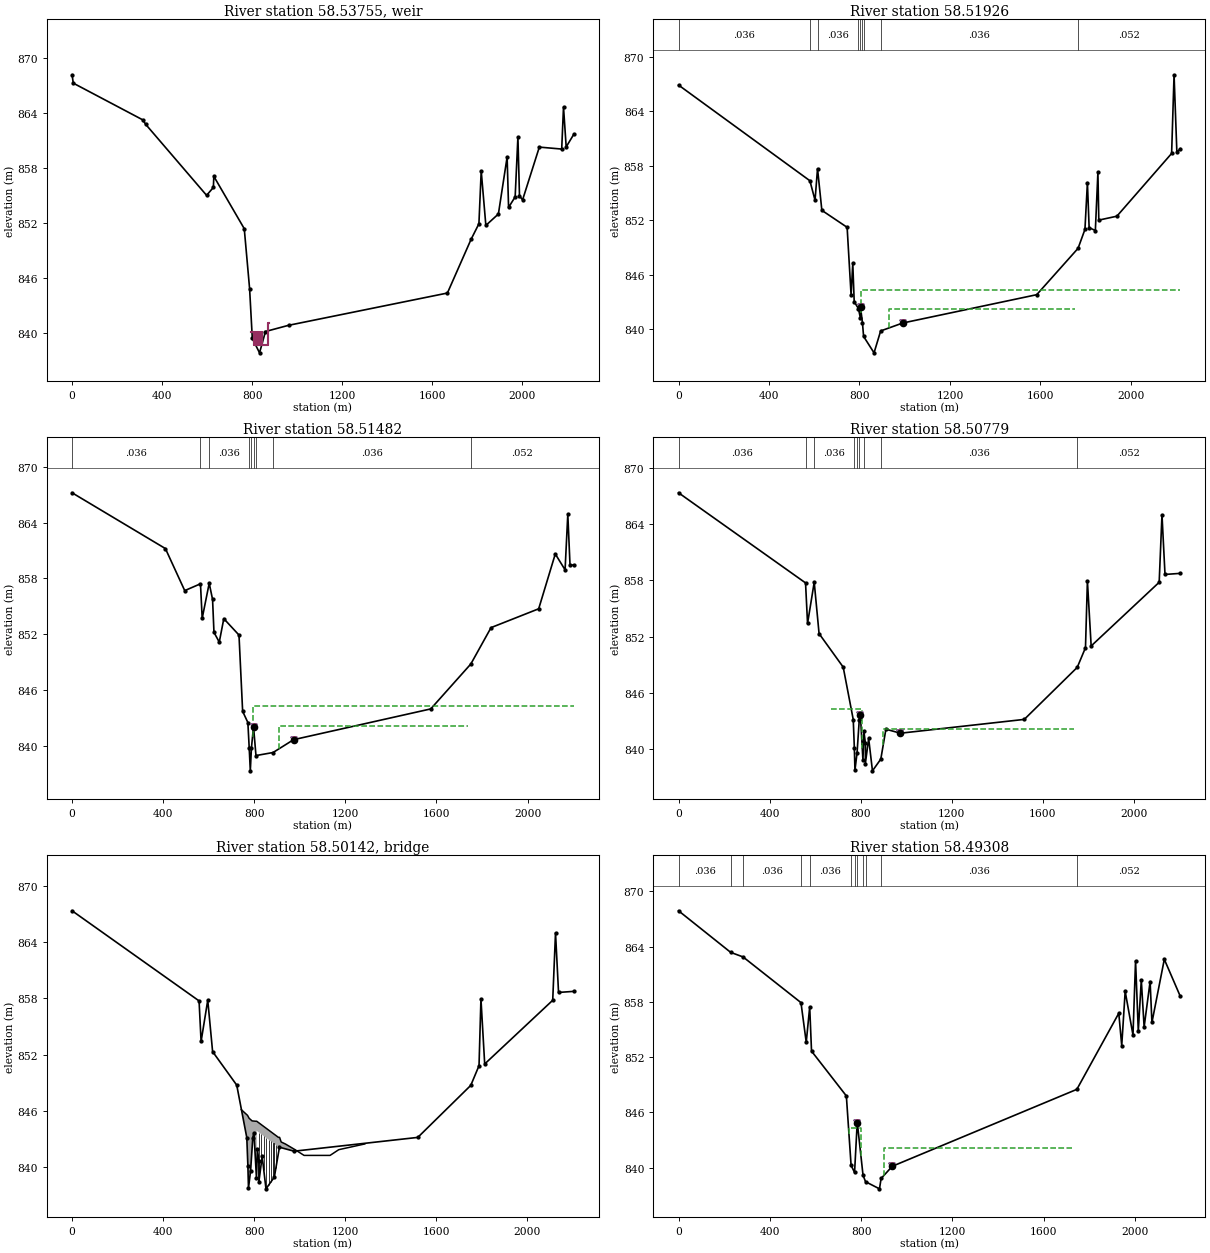
Type RM Length L Ch R = 5 ,58.53755,,,
BEGIN DESCRIPTION:
Ridenbaugh Diversion
END DESCRIPTION:
IW Pilot Flow=0
#Inline Weir SE= 30
  792.48840.1812  807.72840.1812  807.72838.7181813.3588838.7181813.3588840.1812
 813.816840.1812 813.816838.7181819.4548838.7181819.4548840.1812 819.912840.1812
 819.912838.7181825.5508838.7181825.5508840.1812 826.008840.1812 826.008838.7181
831.6468838.7181831.6468840.1812 832.104840.1812 832.104838.7181837.7428838.7181
837.7428840.1812   838.2840.1812   838.2838.7181843.8388838.7181843.8388840.1812
 844.296840.1812 844.296838.7181868.2228838.7181868.2228841.1261 874.776841.1261
IW Dist,WD,Coef,Skew,MaxSub,Min_El,Is_Ogee,SpillHt,DesHd
30.48,6.096,1.93,0,0.98,, 0 ,,,1,1,

Type RM Length L Ch R = 1 ,58.51926,10.3129,7.1299,9.4101
XS GIS Cut Line= 5
       569986.05      4823138.14       570045.41      4823902.01
       570056.47      4823943.08       570202.31      4824047.64
       571127.07      4824859.26
#Sta/Elev= 30
       0 866.864580.8211 856.328603.5281854.1801 614.543857.6608 633.663853.0682
745.3978   851.2762.9339843.7401770.3798 847.223776.6938843.0031795.3561842.2511
803.7869841.2559804.5958842.4009813.1049 840.699818.2078839.1879864.3951837.3801
893.6389839.7911990.5969840.6602 1583.57843.78181766.423 848.886 1796.85850.9699
1807.752856.12291815.371851.16411842.859850.8489 1854.18857.24791858.145851.9941
1938.041 852.4252180.083 859.3332190.868 867.9962203.288859.46812218.567 859.853
#Mann= 9 ,-1 , 0
       0    .036       0580.8211    .026       0 614.543    .036       0
795.3561    .026       0803.7869    .036       0813.1049    .052       0
818.2078    .037       0893.6389    .036       01766.423    .052       0
Levee=-1,804.5958,842.4581,-1,990.5969,840.6597,,
#XS Ineff= 2 ,-1
  807.72  655.32 844.296  929.64  1752.6842.1624
Permanent Ineff=
       T       T
Bank Sta=804.5958,990.5969
XS Rating Curve= 0 ,0
Exp/Cntr=0.5,0.3

Type RM Length L Ch R = 1 ,58.51482,13.9821,11.2682,10.871
XS GIS Cut Line= 5
       569955.82      4823161.71       570028.35      4823900.51
        570051.7      4823946.52       570197.68      4824057.69
       571122.01      4824863.24
#Sta/Elev= 30
       0867.1902 409.881861.2039494.7239856.6932 563.884857.4241571.4009 853.722
 602.226857.4828616.9731855.7471 623.127852.2172646.3821 851.168 666.312853.6851
733.0239851.9252 749.032843.7401771.9819 842.541777.8469839.8289782.7419837.3582
787.5428839.7831 796.735842.0854796.7981842.0881 807.595838.9971882.5148839.3229
 972.882840.70271574.984 844.0011751.148848.82291839.824852.72312049.057 854.743
2121.957860.62692164.964858.92222176.931 864.8842186.692859.41412203.533859.4479
#Mann= 9 ,-1 , 0
       0    .036       0 563.884    .026       0 602.226    .036       0
777.8469    .026       0787.5428    .036       0796.7981    .052       0
 807.595    .037       0882.5148    .036       01751.148    .052       0
Levee=-1,796.735,842.0831,-1,972.882,840.7024,,
#XS Ineff= 2 ,-1
  792.48  655.32 844.296  906.78 1737.36842.1624
Permanent Ineff=
       T       T
Bank Sta=796.735,972.882
XS Rating Curve= 0 ,0
Exp/Cntr=0.5,0.3

Type RM Length L Ch R = 1 ,58.50779,20.3969,23.611,27.9581
BEGIN DESCRIPTION:
Eckert Upstream
END DESCRIPTION:
XS GIS Cut Line= 5
       569944.03      4823171.58       570010.17      4823903.99
       570041.45      4823953.25       570138.15       4824024.8
       571115.94      4824868.01
#Sta/Elev= 30
       0867.3221 558.136857.7161566.9941  853.39 596.286857.7898617.6159 852.311
723.6611 848.739767.8439 843.146772.7031 840.069775.2819837.7611 784.611839.6161
 794.313  843.15799.2526843.6493 810.384838.8309814.6008841.8981  821.03840.6451
  821.04  838.45835.5001 841.144852.2189 837.684888.9169838.9348911.3401842.1201
975.3875 841.6961519.337 843.1671752.253848.71411788.435850.81411796.852857.9358
 1813.35 850.9932112.275857.7819 2124.59864.97792137.863 858.6182205.201858.7328
#Mann= 9 ,-1 , 0
       0    .036       0 558.136    .026       0 596.286    .036       0
772.7031    .026       0 784.611    .036       0 794.313    .052       0
814.6008    .037       0888.9169    .036       01752.253    .052       0
Levee=-1,799.2526,843.6559,-1,975.3875,841.696,,
#XS Ineff= 2 ,-1
  670.56  807.72 844.296  899.16 1737.36842.1624
Permanent Ineff=
       T       T
Bank Sta=799.2526,975.3875
XS Rating Curve= 0 ,0
Exp/Cntr=0.5,0.3

Type RM Length L Ch R = 3 ,58.50142,,,
BEGIN DESCRIPTION:
Eckert Road Bridge
END DESCRIPTION:
Bridge Culvert--1,0,-1,-1, 0
Deck Dist Width WeirC Skew NumUp NumDn MinLoCord MaxHiCord MaxSubmerge Is_Ogee
6.096,11.5824,1.44,0, 17, 17, , , 0.95, 0, 0,0,,
 743.712 771.144778.0751791.0048 806.196811.3776811.3776  906.78  906.78911.9616
 918.972  937.26 979.9321019.5561133.8561171.9561286.256
846.1248845.5152845.2073844.9269844.8903844.8903844.8903843.1713843.1713843.1713
842.6775842.4672841.8576 841.248 841.248841.8576842.4672
 835.152 835.152 835.152 835.152 836.676 836.676843.8693842.1563 836.676 836.676
 835.152 835.152 835.152 835.152 835.152 835.152 835.152
 743.712 771.144778.0751791.0048 806.196811.3776811.3776  906.78  906.78911.9616
 918.972  937.26 979.9321019.5561133.8561171.9561286.256
846.1248845.5152845.2073844.9269844.8903844.8903844.8903843.1713843.1713843.1713
842.6775842.4672841.8576 841.248 841.248841.8576842.4672
 835.152 835.152 835.152 835.152 836.676 836.676843.8693842.1563 836.676 836.676
 835.152 835.152 835.152 835.152 835.152 835.152 835.152
Pier Skew, UpSta & Num, DnSta & Num=  ,821.436, 2 ,821.436, 2 , 0 , 0 , 0 ,,
   .4572   .4572
 836.676843.9912
   .4572   .4572
 836.676843.9912
Pier Skew, UpSta & Num, DnSta & Num=  ,832.104, 2 ,832.104, 2 , 0 , 0 , 0 ,,
   .4572   .4572
 836.676843.9912
   .4572   .4572
 836.676843.9912
Pier Skew, UpSta & Num, DnSta & Num=  ,842.772, 2 ,842.772, 2 , 0 , 0 , 0 ,,
   .4572   .4572
 836.676843.9912
   .4572   .4572
 836.676843.9912
Pier Skew, UpSta & Num, DnSta & Num=  ,853.44, 2 ,853.44, 2 , 0 , 0 , 0 ,,
   .4572   .4572
 836.676843.9912
   .4572   .4572
 836.676843.9912
Pier Skew, UpSta & Num, DnSta & Num=  ,864.108, 2 ,864.108, 2 , 0 , 0 , 0 ,,
   .4572   .4572
 836.676843.9912
   .4572   .4572
 836.676843.9912
Pier Skew, UpSta & Num, DnSta & Num=  ,874.776, 2 ,874.776, 2 , 0 , 0 , 0 ,,
   .4572   .4572
 836.676843.9912
   .4572   .4572
 836.676843.9912
Pier Skew, UpSta & Num, DnSta & Num=  ,885.444, 2 ,885.444, 2 , 0 , 0 , 0 ,,
   .4572   .4572
 836.676843.9912
   .4572   .4572
 836.676843.9912
Pier Skew, UpSta & Num, DnSta & Num=  ,896.112, 2 ,896.112, 2 , 0 , 0 , 0 ,,
   .4572   .4572
 836.676843.9912
   .4572   .4572
 836.676843.9912
BR Coef=-1 , 0 , 0 ,1.25, 0 ,,,0.8,-1,2,0,
WSPro=,,,, 1 ,,,, 0 ,,,, 0 ,,,,-1 ,-1 ,-1 , 0 , 0 , 0 , 0 , 0
BC Design=,, 0 ,, 0 ,,,,,,
BC Use User HTab Curves=0
BC User HTab FreeFlow(D)= 0

Type RM Length L Ch R = 1 ,58.49308,30.33,27.998,24.3611
BEGIN DESCRIPTION:
Eckert Downstream and FEMA XS "BW"
PROJECT XS "CG"
END DESCRIPTION:
XS GIS Cut Line= 5
       569909.44      4823198.43       569977.39      4823824.75
        569989.3      4823934.49       570532.81      4824398.81
        571098.3       4824881.9
#Sta/Elev= 30
       0 867.889228.4729863.3719 282.787862.8751 536.548 857.912559.6119853.6071
574.8101857.4399 582.795852.6451735.4282847.7768 756.225840.2269771.3979839.4619
 783.022844.8848 783.272844.8931808.5601 839.155819.5551838.4578880.5791 837.684
 887.723 838.809936.6199840.1332 1745.54848.49191929.299856.75811942.179 853.244
1957.277  859.141991.489854.3922 2002.77 862.4552014.782854.82412027.917860.3651
2040.346855.27092066.554 860.2022074.538855.75322128.775 862.6162198.967 858.588
#Mann= 12 ,-1 , 0
       0    .036       0228.4729    .052       0 282.787    .036       0
 536.548    .026       0574.8101    .036       0 756.225    .026       0
771.3979    .036       0 783.272    .052       0808.5601    .082       0
819.5551    .037       0 887.723    .036       0 1745.54    .052       0
Levee=-1,783.022,844.8751,-1,936.6199,840.1537,,
#XS Ineff= 2 ,-1
  746.76   800.1 844.296  899.16 1722.12842.1624
Permanent Ineff=
       F       F
Bank Sta=783.022,936.6199
XS Rating Curve= 0 ,0
Exp/Cntr=0.5,0.3

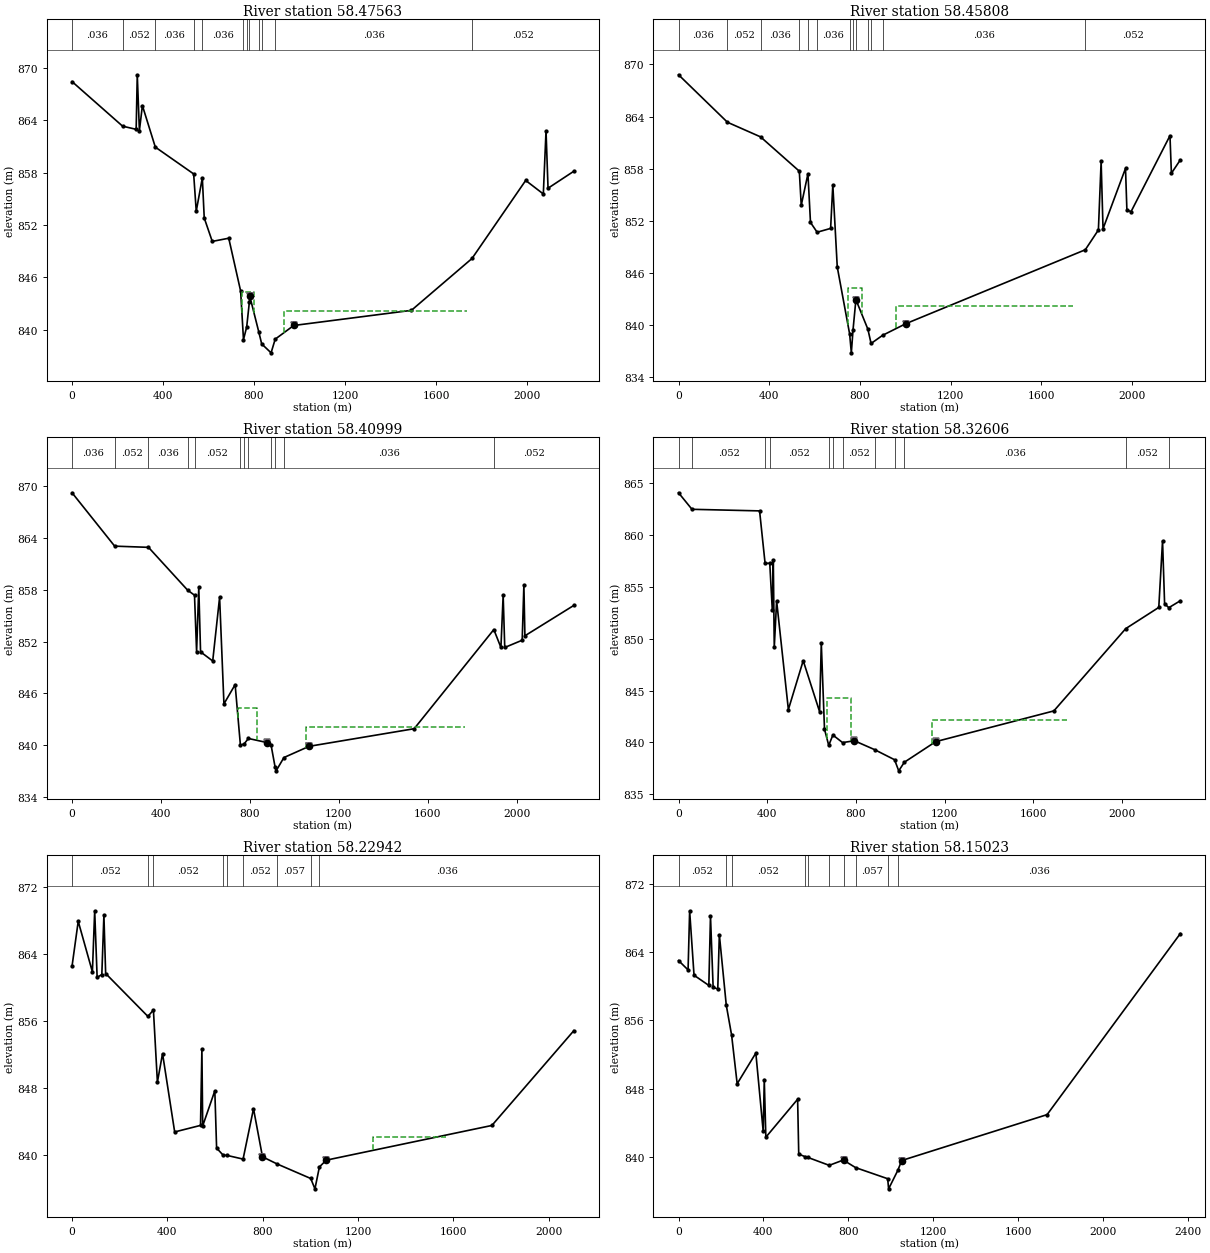
Type RM Length L Ch R = 1 ,58.47563,24.8479,28.1599,35.1059
XS GIS Cut Line= 5
       569885.49       4823204.3       569967.72      4823898.61
       569999.61      4823984.17       570140.43      4824093.89
       571085.62      4824891.88
#Sta/Elev= 30
       0  868.46 222.144863.3469281.7879 862.983 286.622869.2451296.0081862.8361
309.1961865.7101 365.974860.9438534.5119857.8669 545.902  853.59572.6759  857.41
581.0451  852.81 616.347850.1219688.8002850.4871 741.038 844.425753.5671838.8541
 767.686840.3049 779.598843.2051781.6139843.7991820.8499839.7341 833.645838.3579
874.8922837.3331 892.986 838.902974.3999840.47171491.721842.20811758.177848.1608
1994.215 857.1182071.756 855.5662083.634862.79712092.478 856.2252205.993858.1769
#Mann= 12 ,-1 , 0
       0    .036       0 222.144    .052       0 365.974    .036       0
534.5119    .026       0572.6759    .036       0753.5671    .026       0
 767.686    .036       0 779.598    .052       0820.8499    .082       0
 833.645    .037       0 892.986    .036       01758.177    .052       0
Levee=-1,781.6139,843.851,-1,974.3999,840.4769,,
#XS Ineff= 2 ,-1
  746.76   800.1 844.296  929.64 1737.36842.1624
Permanent Ineff=
       F       F
Bank Sta=781.6139,974.3999
XS Rating Curve= 0 ,0
Exp/Cntr=0.5,0.3

Type RM Length L Ch R = 1 ,58.45808,84.7719,77.1421,61.184
XS GIS Cut Line= 5
       569861.06      4823210.28       569948.37      4823898.54
       569987.77      4824004.47       570095.48      4824101.96
       571062.39      4824910.16
#Sta/Elev= 30
       0868.8071 215.696863.3439361.4849 861.665532.4929857.7151 540.978853.7921
570.5441857.4188581.7251  851.82611.0289 850.694670.5231851.1312680.1749856.1359
699.7711846.6951 754.384  838.98761.8198836.8171769.4271 839.496781.7968842.8853
782.0369842.9338  834.91839.5271848.8482837.8931  899.73 838.834 1002.82840.1794
1793.265 848.6751851.074 850.9551863.103858.8371  1871.5  851.091970.591858.0392
1976.732853.20811995.299 853.0762166.618 861.8012172.875857.47412212.269 859.012
#Mann= 13 ,-1 , 0
       0    .036       0 215.696    .052       0361.4849    .036       0
532.4929    .026       0570.5441    .052       0611.0289    .036       0
 754.384    .026       0769.4271    .036       0782.0369    .052       0
  834.91    .082       0848.8482    .037       0  899.73    .036       0
1793.265    .052       0
Levee=-1,781.7968,842.9366,-1,1002.82,840.1751,,
#XS Ineff= 2 ,-1
  746.76  807.72 844.296  960.12 1737.36842.1624
Permanent Ineff=
       F       F
Bank Sta=781.7968,1002.82
XS Rating Curve= 0 ,0
Exp/Cntr=0.3,0.1

Type RM Length L Ch R = 1 ,58.40999,161.4919,135.347,106.0009
XS GIS Cut Line= 5
       569783.55      4823232.08       569868.19       4823891.3
       569913.33       4824062.2        570094.9      4824174.52
       571009.54      4824955.89
#Sta/Elev= 30
       0869.2271191.6921  863.05343.8711862.9119520.2101 857.948550.9169857.3749
560.3221 850.819570.1379858.3018 578.134 850.812 632.858 849.758663.8352857.1268
 683.353844.7888733.7148847.0209  757.51840.0001774.8961 840.176 793.185840.7889
877.1687840.3162 895.691 839.988913.0768837.5419918.1301837.0421953.2659 838.581
 1066.77839.88131539.356 841.9181897.727 853.3941929.688851.3189 1939.72 857.361
1946.892851.32012025.365852.16112032.971858.55122037.566852.67282257.855856.1921
#Mann= 12 ,-1 , 0
       0    .036       0191.6921    .052       0343.8711    .036       0
520.2101    .026       0550.9169    .052       0  757.51    .026       0
774.8961    .036       0 793.185    .052       0 895.691    .082       0
913.0768    .037       0953.2659    .036       01897.727    .052       0
Levee=-1,877.1687,840.3245,-1,1066.77,839.8856,,
#XS Ineff= 2 ,-1
  746.76  830.58 844.296 1051.56 1767.84842.1624
Permanent Ineff=
       F       F
Bank Sta=877.1687,1066.77
XS Rating Curve= 0 ,0
Exp/Cntr=0.3,0.1

Type RM Length L Ch R = 1 ,58.32606,72.91,155.85,199.0381
XS GIS Cut Line= 6
       569657.43      4823358.41       569699.95      4823722.82
       569699.95      4823808.96       569844.62      4824225.89
       570012.34      4824238.93       570910.35      4825036.81
#Sta/Elev= 30
       0864.0922 60.6711862.4971365.6408862.3441 390.511 857.272411.5641857.2969
 423.123852.7359427.5539857.5789431.8739849.1622442.5111853.6592495.5271843.1728
 562.438847.8881636.3499 842.968  644.05849.5831 658.485841.2839 677.564839.7139
 696.354 840.714740.0458 839.984793.3792840.1616 884.252839.3071974.5791838.3301
 993.366837.25791018.724838.08811160.276840.07541693.264843.04112017.525850.9821
2166.628853.02922183.631859.45792192.878853.37512211.988853.0042 2263.83853.6719
#Mann= 12 ,-1 , 0
       0    .036       0 60.6711    .052       0 390.511    .026       0
411.5641    .052       0 677.564    .026       0 696.354    .036       0
740.0458    .052       0 884.252    .057       0974.5791    .037       0
1018.724    .036       02017.525    .052       02211.988    .036       0
Levee=-1,793.3792,840.2665,-1,1160.276,840.0958,,
#XS Ineff= 2 ,-1
    1143  1752.6842.1624  670.56  777.24 844.296
Permanent Ineff=
       F       F
Bank Sta=793.3792,1160.276
XS Rating Curve= 0 ,0
Exp/Cntr=0.3,0.1

Type RM Length L Ch R = 1 ,58.22942,110.0359,127.7139,133.7161
XS GIS Cut Line= 6
       569595.66      4823424.29       569637.41      4823723.75
       569632.44      4823803.27        569808.5      4824253.53
        569928.7      4824414.27       570470.05      4825302.01
#Sta/Elev= 30
       0 862.605  25.823 867.943 85.3141 861.908  94.937869.2009105.1972861.2419
124.9131861.5892133.6079868.6919140.9279 861.708 318.424856.5792341.3799857.3539
358.1628848.7379379.7079 852.144430.6089 842.782539.1111843.5638 544.883852.6841
548.2261843.5042599.1249847.6952606.6069840.8569633.9011840.0139651.3798839.9749
717.7189839.5399761.4401845.5569799.1703839.8135 860.715838.95681001.598837.2231
1019.297835.98711038.038838.6021  1066.8839.41241761.866843.55682105.982854.8842
#Mann= 9 ,-1 , 0
       0    .052       0 318.424    .026       0341.3799    .052       0
633.9011    .026       0651.3798    .036       0717.7189    .052       0
 860.715    .057       01001.598    .037       01038.038    .036       0
Levee=-1,799.1703,839.8489,-1,1066.8,839.4131,,
#XS Ineff= 1 ,-1
 1264.92 1569.72842.1624
Permanent Ineff=
       F
Bank Sta=799.1703,1066.8
XS Rating Curve= 0 ,0
Exp/Cntr=0.3,0.1

Type RM Length L Ch R = 1 ,58.15023,124.0759,145.431,163.325
XS GIS Cut Line= 6
       569478.32      4823502.74       569518.45      4823697.15
       569511.83      4823789.91       569746.23      4824360.97
       569837.78       4824524.5       570311.36      4825700.97
#Sta/Elev= 30
       0 863.047 44.9641861.9421 52.3201868.8961 73.0179861.3191142.7619 860.123
150.5511868.2999  163.04859.8942 184.878859.7048192.2959 866.084 224.857857.8182
250.1561854.2669276.2899848.5629364.2619 852.169 399.035842.9509403.9771849.0552
411.4138842.2779561.1279846.7411566.3861840.2861595.1259 840.006610.0219839.8968
710.0371 838.972777.9288839.6088780.9702 839.524834.4058838.7029985.4918 837.399
989.8709  836.211033.017838.3671  1051.6839.54021736.567 844.9332364.425 866.216
#Mann= 10 ,-1 , 0
       0    .052       0 224.857    .026       0250.1561    .052       0
595.1259    .026       0610.0219    .036       0710.0371    .057       0
780.9702    .052       0834.4058    .057       0985.4918    .037       0
1033.017    .036       0
Levee=-1,777.9288,839.6295,-1,1051.6,839.535,,
Bank Sta=777.9288,1051.6
XS Rating Curve= 0 ,0
Exp/Cntr=0.3,0.1