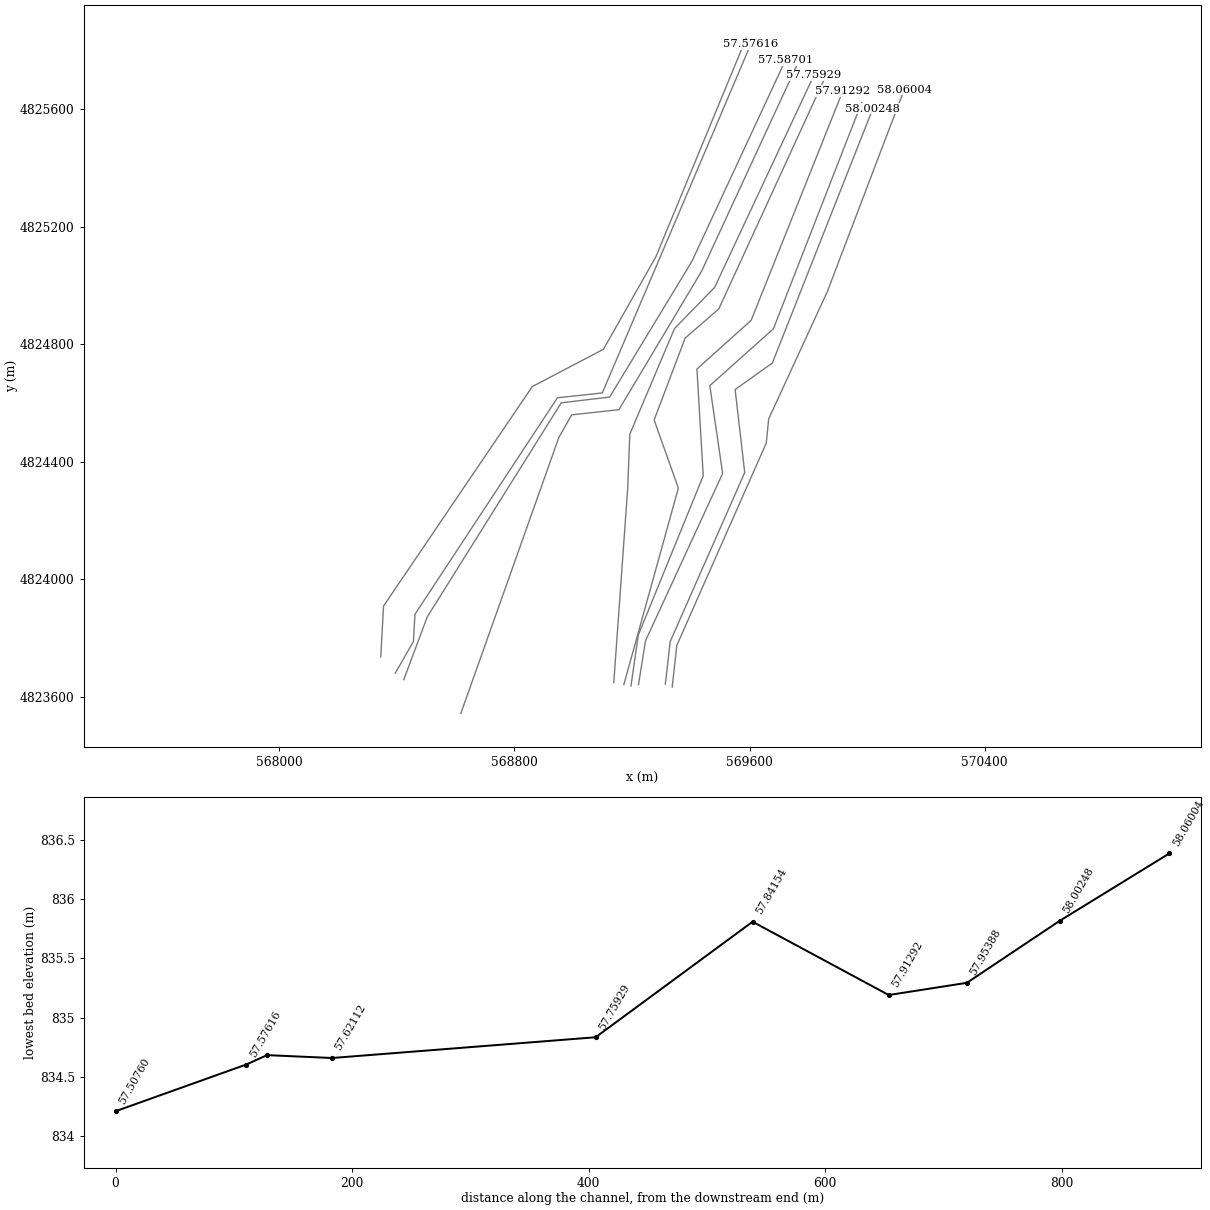
HEC-RAS study Boise2.prj: BoiseRiver_All_reaches

--- Boise2.g01 (geometry) --- (continued)

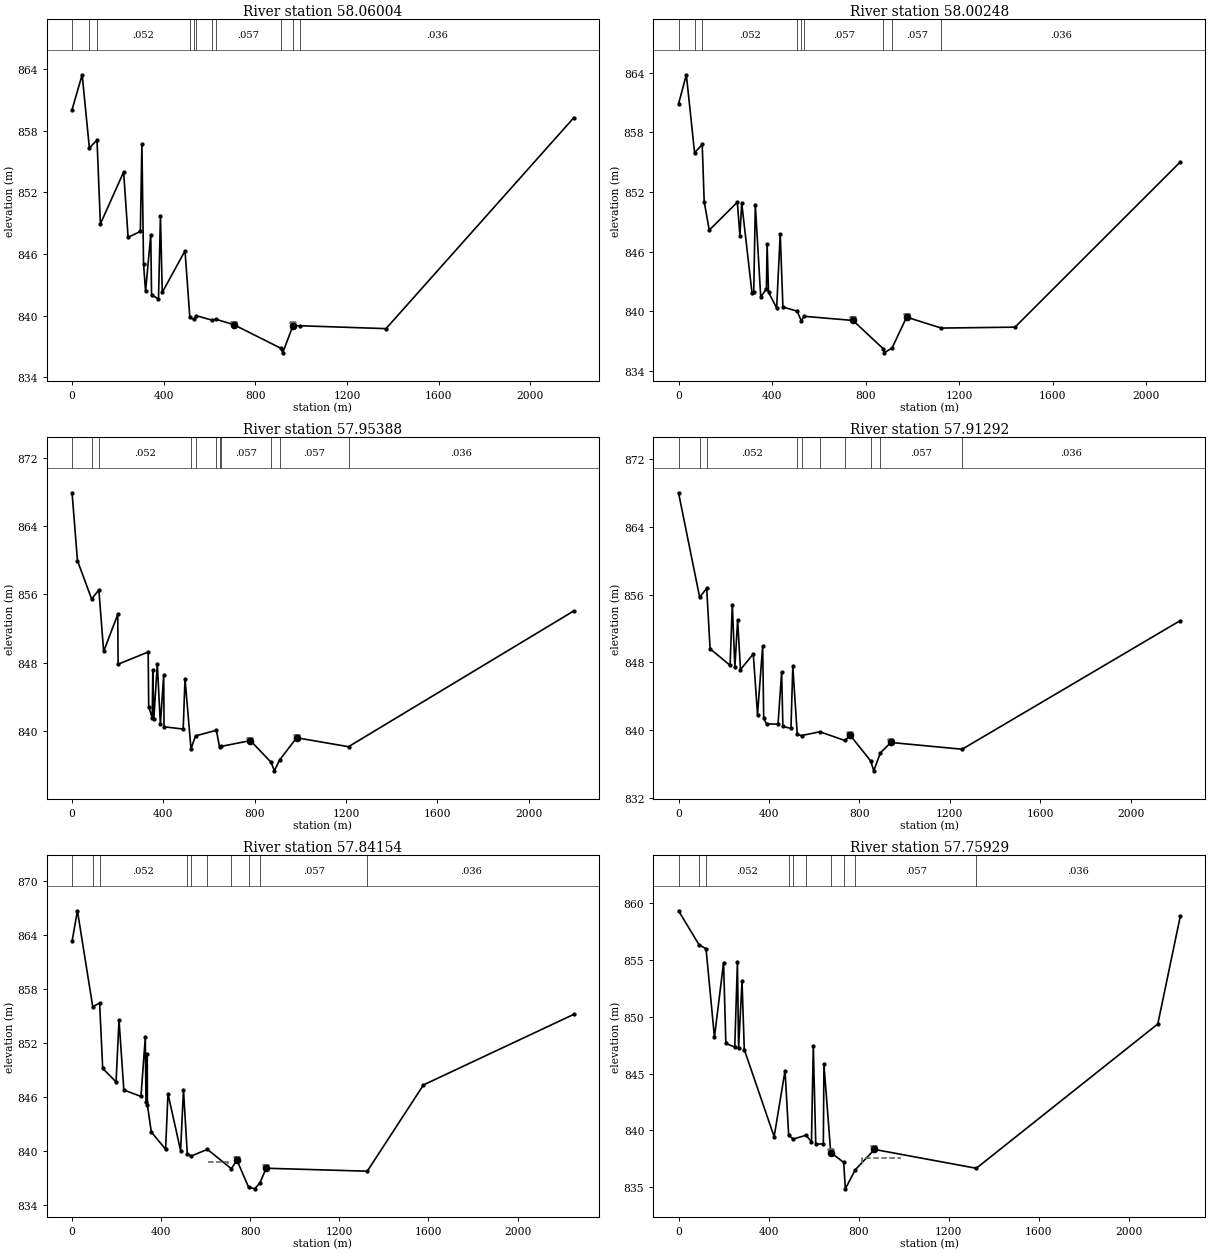
Type RM Length L Ch R = 1 ,58.06004,46.1019,92.829,122.33
BEGIN DESCRIPTION:
FEMA XS "BV"
PROJECT XS "CF"
END DESCRIPTION:
XS GIS Cut Line= 6
       569336.67      4823633.41       569352.18       4823774.9
       569656.75      4824463.83        569664.9      4824545.75
       569864.45      4824979.01        570125.8      4825665.59
#Sta/Elev= 30
       0 860.053  43.996863.4459 75.5889856.3209108.8919857.0948 123.697848.9298
 225.157853.9819244.6581847.6281298.1151848.2029304.9482856.7038312.0369845.0681
320.8362 842.384343.5331847.8539 347.109842.0429377.3781 841.614 385.875849.7321
393.8031842.2691493.1639 846.311 514.226839.8358531.7541839.6381 541.832840.0051
610.6299839.5688629.2529839.6509706.4319839.1229911.8909836.8281919.7139836.3862
964.6584839.0427 964.913839.0488995.1492 839.0221370.736838.74192190.992859.2739
#Mann= 11 ,-1 , 0
       0    .046       0 75.5889    .026       0108.8919    .052       0
 514.226    .026       0531.7541    .036       0 541.832    .057       0
610.6299    .036       0629.2529    .057       0911.8909    .037       0
 964.913    .057       0995.1492    .036       0
Levee=-1,706.4319,839.1113,-1,964.6584,839.0535,,
Bank Sta=706.4319,964.6584
XS Rating Curve= 0 ,0
Exp/Cntr=0.3,0.1

Type RM Length L Ch R = 1 ,58.00248,76.3271,78.3671,82.5051
XS GIS Cut Line= 6
       569313.18      4823643.31       569329.86      4823788.35
       569583.31      4824363.27       569550.69       4824645.6
       569677.42      4824735.98       570019.33      4825601.69
#Sta/Elev= 30
       0860.8719 33.4079863.8068 68.6379855.9488101.2411856.7958109.6341851.0422
131.2899848.1691251.2829850.9769262.4621 847.604270.0558850.8892 314.361841.7951
 321.422841.9482 328.247850.7081351.4311841.4269 375.598842.2581378.6591846.7521
384.6009 841.913419.4551840.3351  434.65847.8179 446.204 840.429 507.065840.0129
 524.868839.0352536.6659839.4951745.6292839.0769875.7822836.2109879.1489 835.817
912.8888836.3078974.8723 839.4121123.094838.3101 1438.21838.40392144.946855.0332
#Mann= 9 ,-1 , 0
       0    .046       0 68.6379    .026       0101.2411    .052       0
 507.065    .026       0 524.868    .036       0536.6659    .057       0
875.7822    .037       0912.8888    .057       01123.094    .036       0
Levee=-1,745.6292,839.0869,-1,974.8723,839.4222,,
#XS Ineff= 1 ,-1
999.02471087.197837.5904
Permanent Ineff=
       F
Bank Sta=745.6292,974.8723
XS Rating Curve= 0 ,0
Exp/Cntr=0.3,0.1

Type RM Length L Ch R = 1 ,57.95388,66.454,66.0639,65.415
BEGIN DESCRIPTION:
FEMA XS "D"
PROJECT XS "CE"
END DESCRIPTION:
XS GIS Cut Line= 6
       569221.92       4823641.9       569245.86      4823791.01
        569508.2      4824360.18        569464.6       4824658.8
       569680.97      4824852.39       569981.36      4825622.34
#Sta/Elev= 30
       0 867.918 23.5979  859.96 85.7159855.4529117.3651856.5191138.3661849.2999
 200.071853.6451201.6801 847.804 333.346849.2371335.6229 842.814 351.026841.5242
 353.707847.1691358.0851 841.377373.4099847.8341386.8031840.7482401.3201 846.496
402.8669 840.465486.7308840.1949494.7252846.1129520.8919 837.869540.6719 839.393
632.1031 840.055 646.169838.0531 652.543  838.16781.1018838.8435 871.889836.2941
885.9561835.2949 908.593836.5529983.7054839.17511210.798838.12682197.854854.0621
#Mann= 11 ,-1 , 0
       0    .046       0 85.7159    .026       0117.3651    .052       0
520.8919    .026       0540.6719    .036       0632.1031    .052       0
 646.169    .036       0 652.543    .057       0 871.889    .037       0
 908.593    .057       01210.798    .036       0
Levee=-1,781.1018,838.834,-1,983.7054,839.1845,,
#XS Ineff= 1 ,-1
   992.71048.311837.5904
Permanent Ineff=
       F
Bank Sta=781.1018,983.7054
XS Rating Curve= 0 ,0
Exp/Cntr=0.3,0.1

Type RM Length L Ch R = 1 ,57.91292,102.3189,115.105,120.788
XS GIS Cut Line= 6
       569196.23      4823636.98       569221.36      4823810.61
       569442.19      4824351.98       569420.76      4824715.38
       569605.26      4824881.24       569917.23      4825661.58
#Sta/Elev= 30
       0 868.032 93.4599855.6918124.5401856.7449139.5999849.6099228.0571847.6479
237.8808 854.832 249.238 847.451 261.508853.0099274.0951 847.149330.6269848.9911
 349.505 841.842372.1949 849.937376.8151 841.386389.3509840.7189 440.151 840.718
456.1219846.8398461.6851840.4382497.3879840.1962505.4879 847.522525.2441839.4881
544.1131839.3628625.5861839.8069 735.252838.7761760.2382 839.367850.6901836.3428
863.6038 835.192892.8702837.3109939.4272 838.5411254.724837.74282219.964852.9402
#Mann= 10 ,-1 , 0
       0    .046       0 93.4599    .026       0124.5401    .052       0
525.2441    .026       0544.1131    .036       0625.5861    .052       0
 735.252    .057       0850.6901    .037       0892.8702    .057       0
1254.724    .036       0
Levee=-1,760.2382,839.3552,-1,939.4272,838.5353,,
#XS Ineff= 2 ,-1
948.1841 1060.21837.5904 1554.481603.248840.9432
Permanent Ineff=
       T       F
Bank Sta=760.2382,939.4272
XS Rating Curve= 0 ,0
Exp/Cntr=0.3,0.1

Type RM Length L Ch R = 1 ,57.84154,150.5889,132.638,56.826
XS GIS Cut Line= 6
       569172.07      4823641.71       569357.55      4824310.19
       569275.11      4824542.19       569380.69      4824820.67
        569495.3      4824920.38       569852.67       4825698.7
#Sta/Elev= 30
       0863.2679 23.9789 866.661  92.804856.0171123.6631856.4219137.4819 849.174
197.5031 847.668 210.729 854.551232.3929 846.777309.3531846.0641328.7341852.6219
 331.784845.4759 337.342 850.733338.1671845.1141 355.726842.1149419.8641840.2001
430.5029846.3629487.1929840.0502500.0689 846.813517.1779 839.706534.7469 839.449
607.5039840.1909715.1739  838.04739.8745 839.001  792.21836.0051 819.489835.8101
843.1171 836.463871.1489838.09641325.156837.76721577.449  847.342252.517855.1731
#Mann= 10 ,-1 , 0
       0    .046       0  92.804    .026       0123.6631    .052       0
517.1779    .026       0534.7469    .036       0607.5039    .052       0
715.1739    .057       0  792.21    .037       0843.1171    .057       0
1325.156    .036       0
Levee=-1,739.8745,839.0077,-1,871.1489,838.1055,,
#XS Ineff= 3 ,-1
   609.6  701.04838.8096874.29441006.102837.5904 1584.961627.632 839.724
Permanent Ineff=
       T       T       F
Bank Sta=739.8745,871.1489
XS Rating Curve= 0 ,0
Exp/Cntr=0.3,0.1

Type RM Length L Ch R = 1 ,57.75929,303.2489,222.8131,76.2131
XS GIS Cut Line= 6
       569137.79      4823648.44       569185.28      4824310.98
       569192.26      4824493.38       569344.35      4824852.98
       569481.02      4824993.37       569818.41      4825714.42
#Sta/Elev= 30
       0859.3461  91.621856.3328 122.162855.9979159.5381848.1999200.0869854.7811
210.1721847.6589249.8129  847.33261.6199854.8619266.8149847.2501282.0729 853.126
292.1612 847.106424.7781839.4329473.1222845.2531489.3149839.5621 509.155839.2198
566.4461  839.56590.5281838.9711598.7351847.4238609.6079838.7551 643.309838.8138
645.9358845.8051676.1241 838.036676.1501838.0359733.6381837.1661741.1691834.8359
784.9109836.5108870.4692838.30881322.823836.64892129.132849.36692229.226 858.881
#Mann= 10 ,-1 , 0
       0    .046       0  91.621    .026       0 122.162    .052       0
489.3149    .026       0 509.155    .036       0566.4461    .052       0
676.1241    .036       0733.6381    .037       0784.9109    .057       0
1322.823    .036       0
Levee=-1,676.1501,838.0415,-1,870.4692,838.3067,,
#XS Ineff= 3 ,-1
  563.88  670.56838.5048813.1271988.7803837.5904 1569.72  1600.2838.5048
Permanent Ineff=
       T       T       F
Bank Sta=676.1501,870.4692
XS Rating Curve= 0 ,0
Exp/Cntr=0.5,0.3

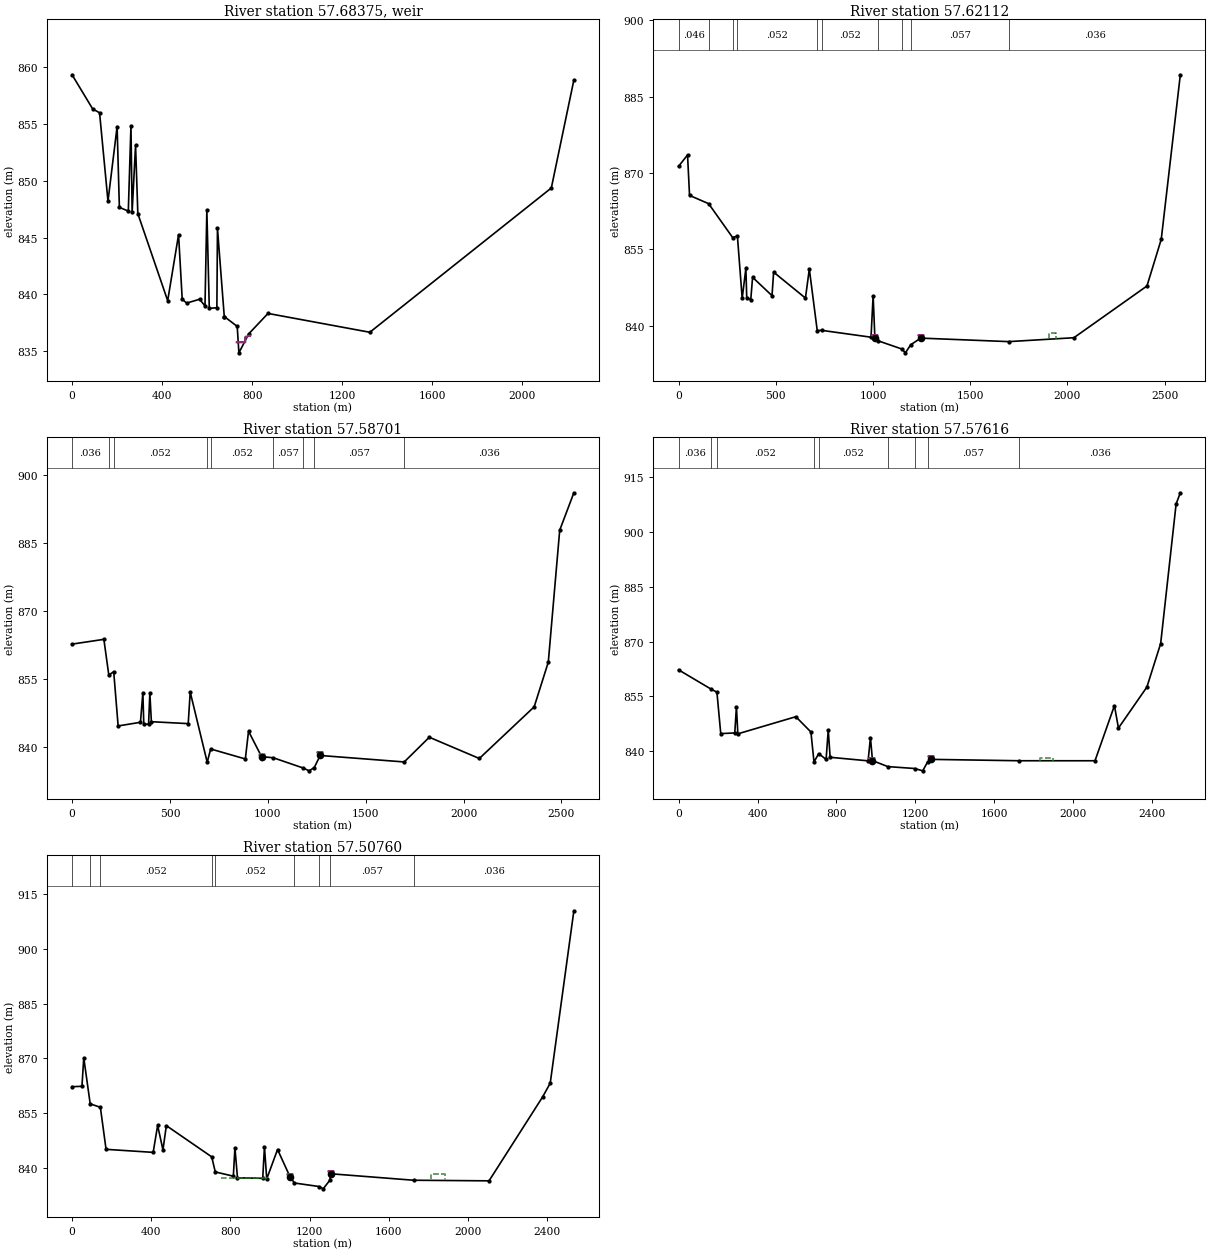
Type RM Length L Ch R = 5 ,57.68375,,,
BEGIN DESCRIPTION:
RM 57.68
END DESCRIPTION:
IW Pilot Flow=0
#Inline Weir SE= 5
  731.52835.7616756.5136835.7616  769.62835.7616  769.62836.2493 789.432836.3407
IW Dist,WD,Coef,Skew,MaxSub,Min_El,Is_Ogee,SpillHt,DesHd
118.872,6.096,1.6,0,0.98,, 0 ,,,0,0,

Type RM Length L Ch R = 1 ,57.62112,54.8631,55.0161,62.569
XS GIS Cut Line= 6
       568617.53      4823543.86       568950.73       4824482.1
       568994.57      4824559.64        569155.3      4824577.11
       569436.94      4825048.83       569760.82      4825749.23
#Sta/Elev= 30
       0871.2878  46.304873.5331 56.5819865.5908154.8451863.9598278.2041857.3131
 302.721 857.613327.3741845.3692346.3701851.2452350.7611845.5021 371.389845.0689
 380.858849.4999480.7839 845.892 489.033850.5161  652.71845.4149672.6631851.1268
713.3171839.0449736.2858839.0782989.9401 837.7331000.817845.88891009.766837.6581
1024.813837.04691147.914835.4221 1166.88834.66091194.109 836.2521246.083837.5528
1698.129836.86622033.315837.62912409.112847.79112482.606 856.9552580.742 889.283
#Mann= 10 ,-1 , 0
       0    .046       0154.8451    .036       0278.2041    .026       0
 302.721    .052       0713.3171    .026       0736.2858    .052       0
1024.813    .057       01147.914    .037       01194.109    .057       0
1698.129    .036       0
Levee=-1,1009.766,837.6666,-1,1246.083,837.566,,
#XS Ineff= 2 ,-1
  754.38   990.6837.8952    1905  1943.1838.5048
Permanent Ineff=
       T       T
Bank Sta=1009.766,1246.083
XS Rating Curve= 0 ,0
Exp/Cntr=0.5,0.3

Type RM Length L Ch R = 1 ,57.58701,18.1411,17.4919,31.0939
BEGIN DESCRIPTION:
FEMA XS "C"
PROJECT XS "CD"
END DESCRIPTION:
XS GIS Cut Line= 6
       568423.27      4823658.41       568503.23      4823872.27
       568959.15      4824600.51       569123.68      4824620.01
       569403.42      4825081.37       569721.96      4825766.43
#Sta/Elev= 30
       0862.6368162.4826863.6883187.6525855.8055212.6838856.5541 235.306844.5868
 349.374845.3951361.6324851.9304 366.387844.9367390.8261844.9907397.2955851.8621
 405.081845.5213593.2499845.0991603.4863852.0511690.2977836.5717707.9528 839.506
885.0286837.3054901.3793843.4209 967.926837.81881027.883 837.5671181.361835.2983
1210.826834.68511237.087835.41111267.523838.07451696.618836.6449 1824.77842.0956
2080.291837.40752360.498848.80792432.558858.65612490.822 887.755 2563.15896.0166
#Mann= 9 ,-1 , 0
       0    .036       0187.6525    .026       0212.6838    .052       0
690.2977    .026       0707.9528    .052       01027.883    .057       0
1181.361    .037       01237.087    .057       01696.618    .036       0
Levee=-1,967.926,837.4227,-1,1267.523,838.072,,
#XS Ineff= 2 ,-1
  731.52  982.98837.5904 1874.52 1920.24838.5048
Permanent Ineff=
       T       T
Bank Sta=967.926,1267.523
XS Rating Curve= 0 ,0
Exp/Cntr=0.3,0.1

Type RM Length L Ch R = 1 ,57.57616,83.9221,110.5619,61.918
BEGIN DESCRIPTION:
FEMA XS "BU"
PROJECT XS "CC"
END DESCRIPTION:
XS GIS Cut Line= 6
       568394.36      4823680.73       568456.15      4823788.44
       568461.42      4823881.09       568946.12      4824617.63
       569098.82       4824634.2       569603.98      4825820.58
#Sta/Elev= 30
       0862.2847164.2469857.0165194.4385856.1545213.8541 844.809284.8911844.9882
293.1987852.1608300.4793844.7465594.1073849.4386670.5347  845.25 686.192837.0317
710.0161839.3323747.4918837.7269 758.358 845.834767.8244838.3182960.1553837.3478
 972.141843.7288982.3887837.41171060.218835.76711196.122835.24591236.961834.6061
1261.293837.02281277.408837.7502 1725.53 837.3712109.533837.36852208.016852.4805
2228.286846.32482372.302857.55392442.178869.49072520.435907.73252541.759910.7945
#Mann= 9 ,-1 , 0
       0    .036       0164.2469    .026       0194.4385    .052       0
 686.192    .026       0710.0161    .052       01060.218    .057       0
1196.122    .037       01261.293    .057       0 1725.53    .036       0
Levee=-1,982.3887,837.4136,-1,1277.408,837.7703,,
#XS Ineff= 2 ,-1
  731.52  982.98837.2856  1828.8 1897.38   838.2
Permanent Ineff=
       T       T
Bank Sta=982.3887,1277.408
XS Rating Curve= 0 ,0
Exp/Cntr=0.3,0.1

Type RM Length L Ch R = 1 ,57.50760,103.362,107.8059,109.6091
XS GIS Cut Line= 6
       568345.05      4823735.97       568354.42      4823908.96
       568860.41      4824655.62       569102.77      4824782.73
        569281.5      4825098.26       569588.11      4825840.59
#Sta/Elev= 30
       0  862.22 49.9189862.3411 59.0669870.1492  91.476857.5381142.9149 856.567
171.6771845.0471409.5549844.2161432.1439851.6112458.9261844.8909  476.05 851.553
705.2012 842.982 723.192838.8502 814.386 837.683822.3799845.4351835.3669 837.246
962.7979837.0912971.4969845.7359982.9971836.92411037.647845.00011100.724837.5062
1123.051835.81011248.736834.83411267.985 834.2121300.935 836.5161308.272838.3389
 1725.12836.56812105.672836.40592376.256859.43122414.603 863.197 2533.96910.4791
#Mann= 9 ,-1 , 0
       0    .052       0  91.476    .026       0142.9149    .052       0
705.2012    .026       0 723.192    .052       01123.051    .057       0
1248.736    .037       01300.935    .057       0 1725.12    .036       0
Levee=-1,1100.724,837.5264,-1,1308.272,838.3799,,
#XS Ineff= 2 ,-1
  754.38  982.98837.2856 1813.56 1882.14   838.2
Permanent Ineff=
       T       T
Bank Sta=1100.724,1308.272
XS Rating Curve= 0 ,0
Exp/Cntr=0.3,0.1