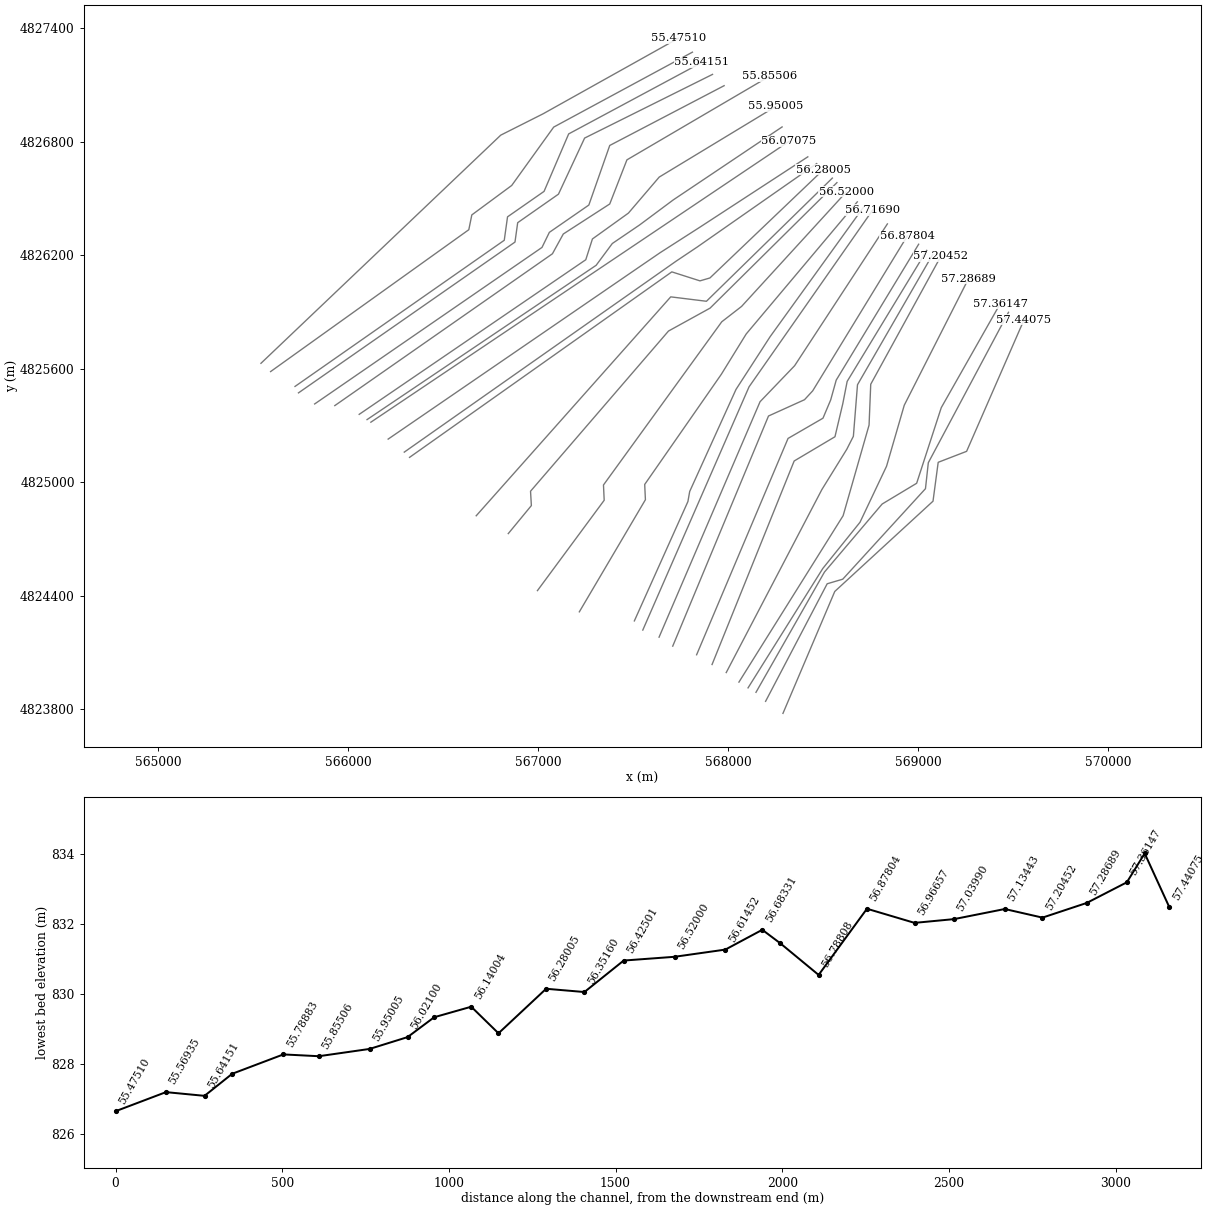
HEC-RAS study Boise2.prj: BoiseRiver_All_reaches

--- Boise2.g01 (geometry) --- (continued)

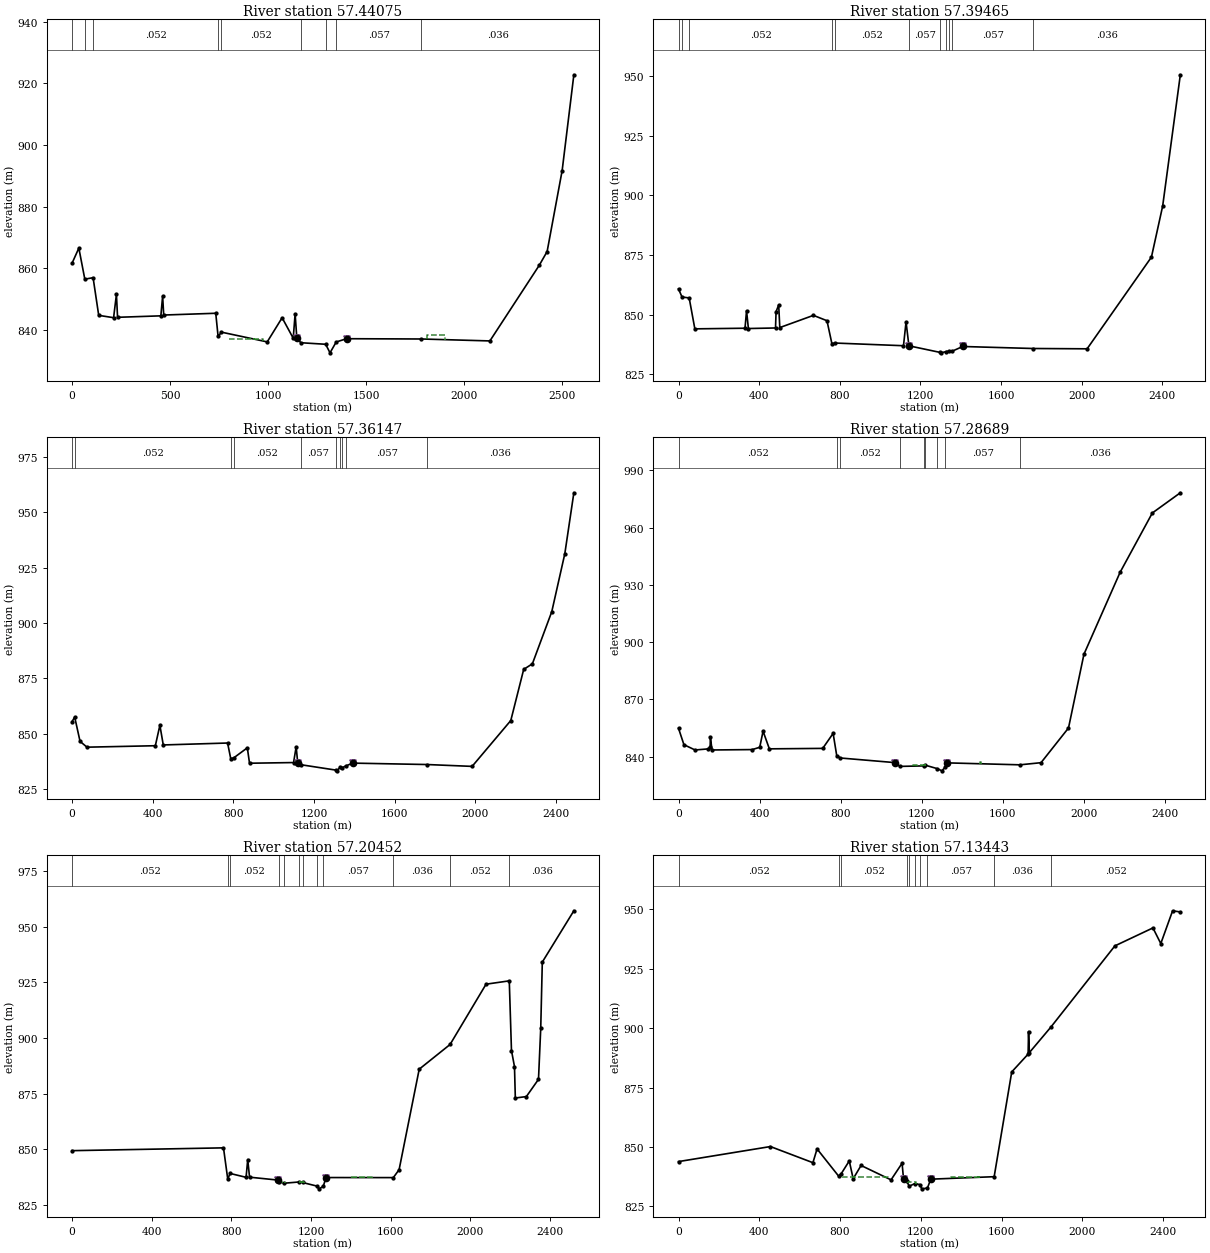
Type RM Length L Ch R = 1 ,57.44075,67.5769,74.338,80.857
XS GIS Cut Line= 6
       568289.44      4823778.39       568562.04      4824422.82
       569079.03      4824899.98       569106.28      4825105.44
       569255.83      4825163.44       569558.05      4825858.91
#Sta/Elev= 30
       0861.5879 34.5729866.5031  65.037 856.406107.2859856.8809 135.956 844.645
211.9201  843.89 226.382851.4701232.1241 844.012453.1331844.4899 462.114 850.929
467.6251 844.749733.1931845.3259745.1111837.7971 762.267 839.187995.7858836.0231
 1071.84 843.8661128.551837.21091138.204845.14391146.789837.30651167.341 835.751
1294.087835.25291316.194 832.4681347.858835.99691400.657837.05791782.122 836.968
2132.003 836.3372383.459860.86192424.112865.38392500.764891.6882 2560.52922.8101
#Mann= 9 ,-1 , 0
       0    .052       0  65.037    .026       0107.2859    .052       0
745.1111    .026       0 762.267    .052       01167.341    .057       0
1294.087    .037       01347.858    .057       01782.122    .036       0
Levee=-1,1146.789,837.313,-1,1400.657,837.0417,,
#XS Ineff= 2 ,-1
   800.1  975.36836.9808 1813.56    1905   838.2
Permanent Ineff=
       T       T
Bank Sta=1146.789,1400.657
XS Rating Curve= 0 ,0
Exp/Cntr=0.3,0.1

Type RM Length L Ch R = 1 ,57.39465,61.2371,53.504,44.9019
BEGIN DESCRIPTION:
FEMA XS "BT"
PROJECT XS "CB"
END DESCRIPTION:
XS GIS Cut Line= 6
       568198.04      4823842.07       568522.06       4824463.4
       568604.01      4824487.64       569039.29        4824966.
        569054.3      4825103.17        569476.3      4825898.35
#Sta/Elev= 30
       0860.8022 17.2074857.4277 52.8221857.0339  80.947844.0723  329.85844.3362
337.4892851.7008346.6262844.2131481.2207844.4408483.9718851.2933496.9572854.0834
502.4415844.6075669.3356849.7299736.5861847.4824 760.899837.8952777.7817838.1189
1116.225836.99691128.917847.00721143.046837.04381143.162  836.96 1298.54834.1833
1301.035834.01391327.925834.52011339.763834.74731358.802834.74181410.166836.6732
1760.073835.83292027.331835.70372346.501874.14532402.261895.57832489.888950.6209
#Mann= 11 ,-1 , 0
       0    .052       0 17.2074    .026       0 52.8221    .052       0
 760.899    .026       0777.7817    .052       01143.162    .057       0
 1298.54    .037       01327.925    .082       01339.763    .037       0
1358.802    .057       01760.073    .036       0
Levee=-1,1143.046,836.996,-1,1410.166,836.6852,,
#XS Ineff= 1 ,-1
  807.72  960.12 836.676
Permanent Ineff=
       T
Bank Sta=1143.046,1410.166
XS Rating Curve= 0 ,0
Exp/Cntr=0.3,0.1

Type RM Length L Ch R = 1 ,57.36147,71.372,120.271,176.973
BEGIN DESCRIPTION:
FEMA XS "B"
PROJECT XS "CA"
END DESCRIPTION:
XS GIS Cut Line= 6
        568147.5      4823889.74       568507.85      4824525.39
       568811.32      4824884.92       568992.92      4824994.61
       569122.45      4825394.35       569432.39      4825943.39
#Sta/Elev= 30
       0855.4191 12.9391 857.485 39.6069   846.5 73.9631 843.876 412.936844.5301
 435.455 853.771452.2229  844.88771.2308845.7499786.7711838.6981801.4509839.0318
869.0409843.5861879.9771836.62421098.405 836.9281111.201 844.0611118.759836.9512
1135.368 835.9391307.552833.52981312.593833.1879  1329.2834.77191338.904834.5811
1360.053 835.508 1391.82 836.6751760.157836.03721983.651 835.2012175.466 855.907
2239.393 878.9962282.568881.53192378.692905.0759 2443.35 931.2392488.206 958.767
#Mann= 10 ,-1 , 0
       0    .026       0 12.9391    .052       0786.7711    .026       0
801.4509    .052       01135.368    .057       01307.552    .037       0
  1329.2    .082       01338.904    .037       01360.053    .057       0
1760.157    .036       0
Levee=-1,1118.759,836.9321,-1,1391.82,836.6821,,
#XS Ineff= 1 ,-1
  822.96  960.12 836.676
Permanent Ineff=
       T
Bank Sta=1118.759,1391.82
XS Rating Curve= 0 ,0
Exp/Cntr=0.3,0.1

Type RM Length L Ch R = 1 ,57.28689,120.6779,132.8392,150.666
XS GIS Cut Line= 6
       568105.74       4823913.2       568499.09      4824544.29
       568694.76      4824788.42       568834.53      4825084.73
       568927.71      4825407.13       569265.23      4826075.03
#Sta/Elev= 30
       0854.8619 26.6151846.2991  81.491843.5261146.7539844.0991156.0259 845.194
157.0061850.3561165.1641843.5309363.4551 843.737 400.413844.9462 416.889 853.376
 447.956844.1229711.0969844.3622762.4331852.2189 780.302840.5101 797.625 839.332
1066.254836.91851091.878834.93011210.173835.18791215.618 835.6041276.986  833.72
1298.804832.59811315.599 834.6211324.798836.77321683.601835.7521 1787.76 836.869
1923.268 855.0531999.466 893.7012177.804936.64222336.745967.71412474.792978.2989
#Mann= 9 ,-1 , 0
       0    .052       0 780.302    .026       0 797.625    .052       0
1091.878    .057       01210.173    .026       01215.618    .057       0
1276.986    .037       01315.599    .057       01683.601    .036       0
Levee=-1,1066.254,836.9138,-1,1324.798,836.7583,,
#XS Ineff= 3 ,-1
  822.96   952.5836.37121158.4471224.418835.45681487.424 1493.52837.2856
Permanent Ineff=
       T       T       T
Bank Sta=1066.254,1324.798
XS Rating Curve= 0 ,0
Exp/Cntr=0.3,0.1

Type RM Length L Ch R = 1 ,57.20452,134.5969,113.0259,77.0931
BEGIN DESCRIPTION:
FEMA XS "A"
PROJECT XS "BZ"
END DESCRIPTION:
XS GIS Cut Line= 5
       568057.75      4823943.66       568606.01      4824823.31
       568742.51      4825302.21       568751.31      4825518.07
       569120.45      4826194.52
#Sta/Elev= 30
       0849.3261 760.793 850.592 782.062 836.629794.4149839.0861874.2599837.3499
882.6091845.3381891.7009837.41611034.256836.11361038.211835.31081067.204834.7131
1142.334835.27391157.966835.02611228.558833.45311241.266 832.1781261.837 833.293
1276.292837.25121614.042837.22411643.132840.78891744.158 885.9321899.184  897.03
2080.006924.1188 2196.68925.6169 2207.68 894.3132222.866 887.0892227.052872.9899
2282.462873.62512343.445881.37312354.743904.33312362.604934.05292521.153957.0979
#Mann= 12 ,-1 , 0
       0    .052       0 782.062    .026       0794.4149    .052       0
1038.211    .026       01067.204    .057       01142.334    .026       0
1157.966    .057       01228.558    .037       01261.837    .057       0
1614.042    .036       01899.184    .052       0 2196.68    .036       0
Levee=-1,1034.256,836.0389,-1,1276.292,837.2338,,
#XS Ineff= 3 ,-1
1032.1021071.183 835.1521138.0291164.354 835.1521408.176 1508.76837.2856
Permanent Ineff=
       T       T       T
Bank Sta=1034.256,1276.292
XS Rating Curve= 0 ,0
Exp/Cntr=0.5,0.3

Type RM Length L Ch R = 1 ,57.13443,181.972,152.439,99.7159
BEGIN DESCRIPTION:
East Parkcenter Upstream
END DESCRIPTION:
XS GIS Cut Line= 6
       567990.92      4823994.15       568494.04      4824961.16
       568625.11      4825174.05       568659.95      4825242.88
       568681.62      4825515.43       569077.63      4826204.48
#Sta/Elev= 30
       0  843.89455.1012850.2101665.5631 843.423686.1499849.2148 792.583 837.816
804.5199 838.623845.7039844.1689 864.949 836.662 904.066842.25111052.585836.2051
1107.249843.1929  1114.3 836.6281129.349835.64311143.019833.55791171.104834.6561
1196.454834.18091204.505832.4241 1232.74832.74291249.186836.49271563.294  837.53
 1650.37 881.6091731.484889.09491733.593 898.5941737.655889.72611843.643 900.402
2161.278934.62292349.702942.17712388.614935.59312447.154949.38492485.364948.8839
#Mann= 10 ,-1 , 0
       0    .052       0 792.583    .026       0804.5199    .052       0
1129.349    .057       01143.019    .026       01171.104    .057       0
1196.454    .037       0 1232.74    .057       01563.294    .036       0
1843.643    .052       0
Levee=-1,1114.3,836.6394,-1,1249.186,836.5053,,
#XS Ineff= 3 ,-1
  807.72 1036.32837.28561128.8541175.425 835.152 1348.74 1493.52837.2856
Permanent Ineff=
       T       T       T
Bank Sta=1114.3,1249.186
XS Rating Curve= 0 ,0
Exp/Cntr=0.5,0.3

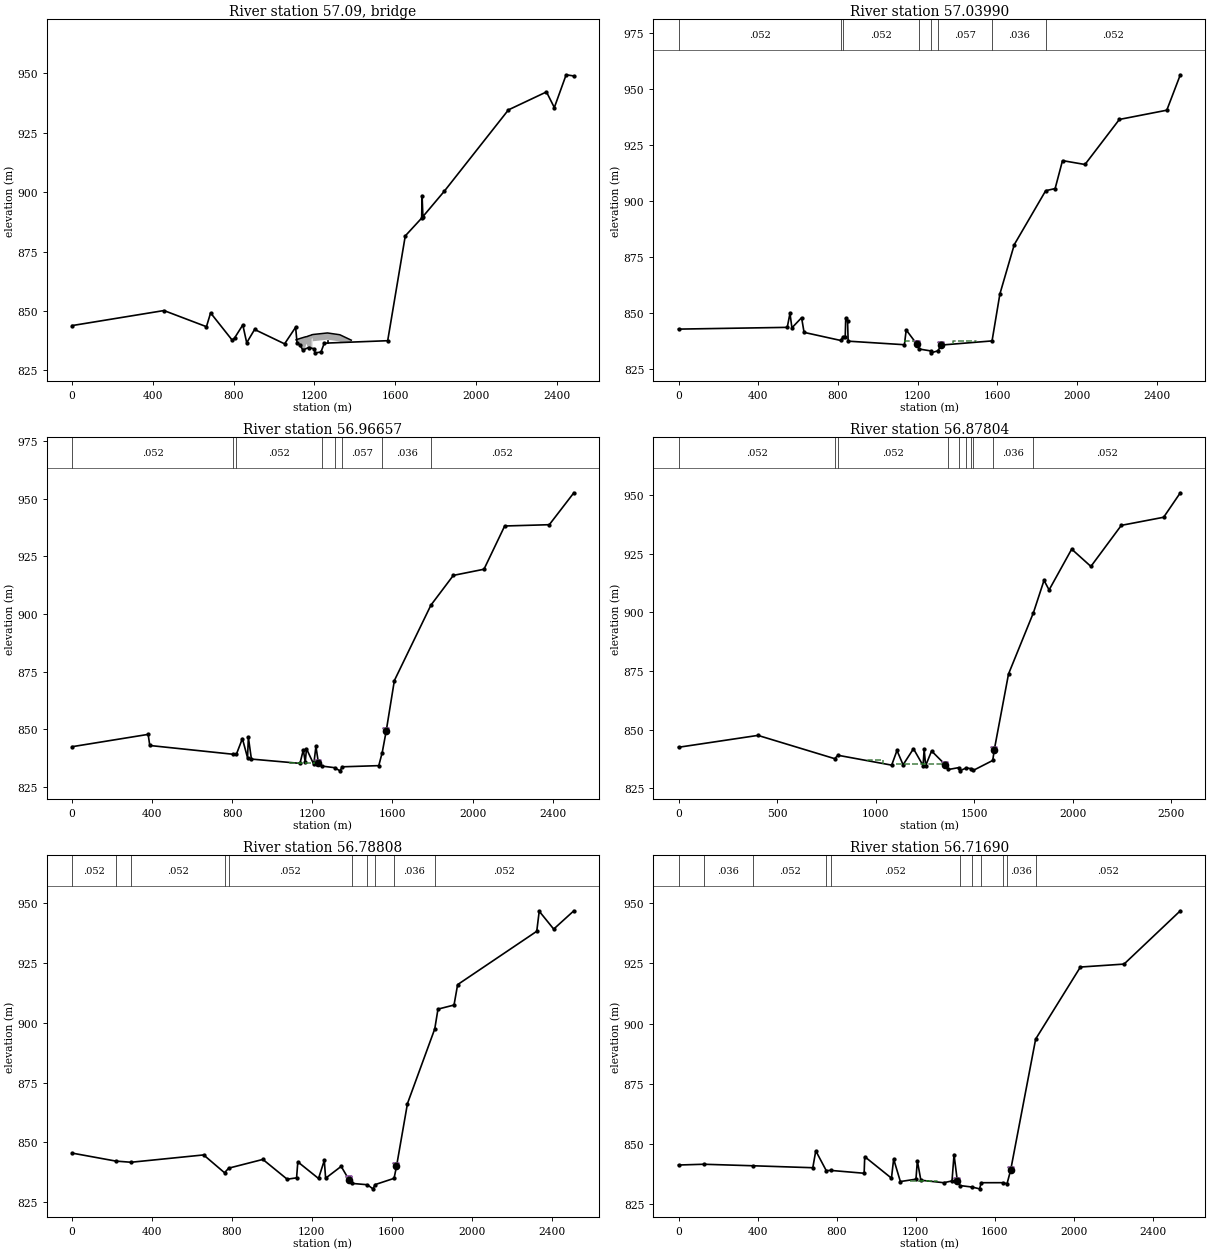
Type RM Length L Ch R = 3 ,57.09   ,,,
BEGIN DESCRIPTION:
East Parkcenter Bridge
END DESCRIPTION:
Bridge Culvert--1,0,-1,-1, 0
Deck Dist Width WeirC Skew NumUp NumDn MinLoCord MaxHiCord MaxSubmerge Is_Ogee
70.104,23.1648,1.44,0, 28, 28, , , 0.95, 0, 0,0,,
1109.4721115.5681121.664 1127.761133.8561139.9521146.0481152.1441155.4971155.802
1157.0211161.2881165.5551166.7741167.0791179.5761185.0621186.8911186.8911189.025
1191.1581191.1581192.6821192.682 1264.921326.1851326.1851382.878
837.8952838.1085838.2609838.4286838.5871838.7456838.9041839.0626839.1144839.1449
839.1754839.2363839.2973839.3583839.4192839.7636839.8978840.0288840.0288840.0593
840.0897840.0897840.1355840.1355840.7908840.0349840.0349837.7611
833.0184833.0184833.0184833.0184833.0184833.0184833.0184833.0184833.0184834.2985
 835.213 836.295 835.213834.2985833.0184833.0184833.0184833.0184   838.2838.7487
   838.2833.0184833.0184837.2856837.9561837.1942833.9328833.9328
1161.2881167.384 1173.481179.5761185.6721191.7681197.864 1203.961207.3131207.618
1208.8371213.1041217.371 1218.591218.8951231.3921236.8781238.7071238.7071240.841
1242.9741242.9741244.4981244.4981316.7361378.0011378.0011434.694
837.8952838.1085838.2609838.4286838.5871838.7456838.9041839.0626839.1144839.1449
839.1754839.2363839.2973839.3583839.4192839.7636839.8978840.0288840.0288840.0593
840.0897840.0897840.1355840.1355840.7908840.0349840.0349837.7611
833.0184833.0184833.0184833.0184833.0184833.0184833.0184833.0184833.0184834.2985
 835.213 836.295 835.213834.2985833.0184833.0184833.0184833.0184   838.2838.7487
   838.2833.0184833.0184837.2856837.9561837.1942833.9328833.9328
Pier Skew, UpSta & Num, DnSta & Num=  ,1264.92, 4 ,1316.736, 4 , 0 , 0 , 0 ,,
  3.3528  3.3528  1.2192  1.2192
833.3232834.5424834.5424   838.2
  3.3528  3.3528  1.2192  1.2192
833.3232834.5424834.5424   838.2
BR Coef=-1 , 0 , 0 ,1.25, 0 ,,,0.8,-1,2,0,
WSPro=,,,, 1 ,,,, 0 ,,,, 0 ,,,,-1 ,-1 ,-1 , 0 , 0 , 0 , 0 , 0
BC Design=,, 0 ,, 0 ,,,,,,
BC Use User HTab Curves=0
BC User HTab FreeFlow(D)= 0

Type RM Length L Ch R = 1 ,57.03990,119.025,118.2539,121.5359
BEGIN DESCRIPTION:
East Parkcenter Downstream
END DESCRIPTION:
XS GIS Cut Line= 6
       567916.33      4824036.68        568348.4      4825112.41
       568563.05      4825240.57       568604.21      4825414.98
       568627.28      4825533.09       569046.09      4826225.55
#Sta/Elev= 30
       0842.7242545.5969843.5051 559.184  849.78569.0089 843.295617.5001847.8189
629.9329841.2681813.3369837.6681827.6899 839.368836.4538 839.303 839.011847.7092
848.2529846.2059851.1531837.34411133.453835.75711142.526842.35411196.538835.9196
1208.675 833.8241266.842 832.9691268.254832.1351 1301.34833.04191319.062  835.61
1573.292837.45691612.693858.43691684.809880.43711842.474904.49921889.763905.4371
1926.873 917.9212039.538916.18922212.094936.29322450.146 940.4182518.072956.2259
#Mann= 8 ,-1 , 0
       0    .052       0813.3369    .026       0827.6899    .052       0
1208.675    .057       01266.842    .037       0 1301.34    .057       0
1573.292    .036       01842.474    .052       0
Levee=-1,1196.538,835.8896,-1,1319.062,835.597,,
#XS Ineff= 2 ,-1
 1135.38 1203.96837.2856 1379.22 1493.52837.2856
Permanent Ineff=
       F       F
Bank Sta=1196.538,1319.062
XS Rating Curve= 0 ,0
Exp/Cntr=0.5,0.3

Type RM Length L Ch R = 1 ,56.96657,148.2559,142.7729,137.406
XS GIS Cut Line= 6
       567835.09      4824088.22       568316.19      4825231.64
       568499.99      4825338.57       568540.52      4825435.01
       568569.64      4825539.83       569003.47      4826258.12
#Sta/Elev= 30
       0842.4919379.9451847.8359388.0491843.0162804.0771839.2171820.1129839.1291
850.5289846.0139 876.265 837.683  880.33846.5701 895.464 837.128 1138.06 835.266
1154.846841.15291164.342 835.6971170.497841.61321206.986834.83891217.647 842.619
1230.526835.25241249.338834.07091310.477833.40391337.804832.02811349.316833.7762
1531.545 834.2831548.769 839.9771568.309849.12871609.414871.16811791.821903.8579
1903.847916.76712056.897919.43412160.252938.18512383.022 938.7442505.693952.5851
#Mann= 8 ,-1 , 0
       0    .052       0804.0771    .026       0820.1129    .052       0
1249.338    .057       01310.477    .037       01349.316    .057       0
1548.769    .036       01791.821    .052       0
Levee=-1,1230.526,835.2465,-1,1568.309,849.1302,,
#XS Ineff= 1 ,-1
 1082.04 1234.44835.4568
Permanent Ineff=
       T
Bank Sta=1230.526,1568.309
XS Rating Curve= 0 ,0
Exp/Cntr=0.5,0.3

Type RM Length L Ch R = 1 ,56.87804,110.0511,145.0571,164.3482
XS GIS Cut Line= 5
       567709.39      4824133.79       568213.34      4825350.19
       568402.74      4825436.28       568445.72      4825482.93
       568943.25      4826300.86
#Sta/Elev= 30
       0842.4791 402.852847.5449791.6509837.6349 809.215839.06021081.285 834.863
1108.141841.10691139.162835.01211191.795 841.8471240.463834.68991245.987 841.558
1253.747834.68991283.645840.89421353.129835.04881369.481 833.0091421.409833.8021
1427.206832.43191459.337  833.671484.537833.36191495.483832.63531593.994836.8619
1601.093841.1224 1673.94 873.7121800.434899.87811854.035913.62791879.782909.5561
1994.382926.95012091.828 919.5742246.185937.08512460.833940.53692545.503950.9738
#Mann= 10 ,-1 , 0
       0    .052       0791.6509    .026       0 809.215    .052       0
1369.481    .057       01421.409    .037       01459.337    .057       0
1484.537    .037       01495.483    .057       01593.994    .036       0
1800.434    .052       0
Levee=-1,1353.129,835.0605,-1,1601.093,841.1443,,
#XS Ineff= 2 ,-1
  960.12 1036.32836.8589  1104.9 1356.36 835.152
Permanent Ineff=
       T       T
Bank Sta=1353.129,1601.093
XS Rating Curve= 0 ,0
Exp/Cntr=0.3,0.1

Type RM Length L Ch R = 1 ,56.78808,102.4158,114.791,123.024
XS GIS Cut Line= 4
       567637.43      4824181.14       568168.88      4825425.68
       568350.75      4825615.94       568838.91      4826365.46
#Sta/Elev= 30
       0 845.506219.7081842.1459295.2869 841.671 658.329844.7361762.8251837.2841
783.9169839.1948 954.725842.85311076.354834.57411123.437835.14011129.651841.8298
1233.269834.87491262.102842.42081268.812834.98191346.562839.93791386.852834.1833
1401.107832.81211477.942832.25491505.215  830.541517.363832.34121611.273834.9329
1623.429 839.9121678.336866.2541 1814.91897.51281830.993905.77021911.306 907.488
1929.302916.02892325.254938.3579 2337.59946.76212410.069939.27992510.944946.9429
#Mann= 10 ,-1 , 0
       0    .052       0219.7081    .036       0295.2869    .052       0
762.8251    .026       0783.9169    .052       01401.107    .057       0
1477.942    .037       01517.363    .057       01611.273    .036       0
 1814.91    .052       0
Levee=-1,1386.852,834.6552,-1,1623.429,839.9191,,
#XS Ineff= 2 ,-1
   914.4 1051.56836.0664 1120.14 1341.12834.8472
Permanent Ineff=
       T       T
Bank Sta=1386.852,1623.429
XS Rating Curve= 0 ,0
Exp/Cntr=0.3,0.1

Type RM Length L Ch R = 1 ,56.71690,51.6819,54.1791,56.6529
BEGIN DESCRIPTION:
FEMA XS "BS"
PROJECT XS "BY"
END DESCRIPTION:
XS GIS Cut Line= 5
       567551.86      4824218.75       567936.38      4825102.93
         568111.      4825504.43       568293.72      4825766.87
       568761.68      4826438.99
#Sta/Elev= 30
       0 841.319 127.546  841.64 378.066 841.009679.8719840.1979694.9129847.2111
747.7469 839.026771.1221839.0861939.8459837.9031 942.712844.78191078.094 835.868
1089.219843.78091123.215834.46981202.185835.44621209.171 843.075    1227 835.024
1342.741833.98181384.741834.72591394.908845.66211411.898834.5645 1424.86832.8041
1487.617832.17191524.103831.44291532.843 833.9811643.874833.99591663.184833.5201
1681.682839.21081808.262893.56082034.719923.42692255.845 924.6552540.764946.7609
#Mann= 11 ,-1 , 0
       0    .052       0 127.546    .036       0 378.066    .052       0
747.7469    .026       0771.1221    .052       0 1424.86    .057       0
1487.617    .037       01532.843    .057       01643.874    .082       0
1663.184    .036       01808.262    .052       0
Levee=-1,1411.898,834.5729,-1,1681.682,839.2424,,
#XS Ineff= 2 ,-1
     762 1097.28836.3712 1173.48 1310.64834.5424
Permanent Ineff=
       T       T
Bank Sta=1411.898,1681.682
XS Rating Curve= 0 ,0
Exp/Cntr=0.3,0.1

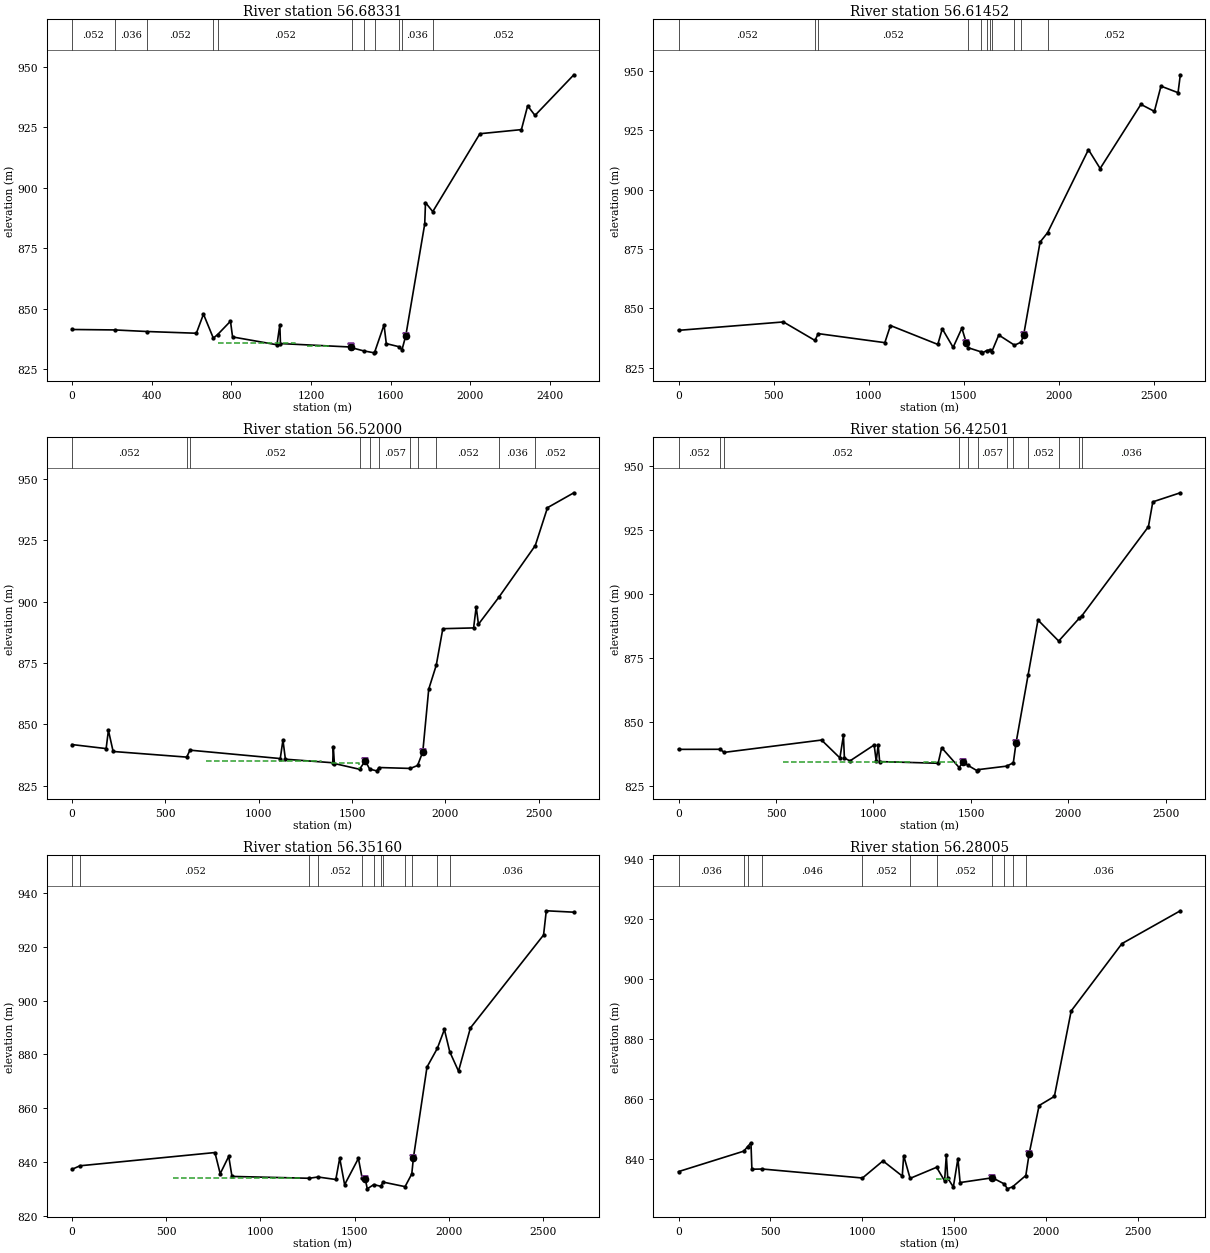
Type RM Length L Ch R = 1 ,56.68331,109.7451,110.921,112.7489
XS GIS Cut Line= 6
       567507.42      4824267.13       567789.29      4824898.14
       567798.61      4824951.25       568042.39      4825490.86
       568221.64      4825769.18       568718.72      4826461.73
#Sta/Elev= 30
       0841.4711214.5091841.2861 378.101 840.632624.3069 839.923660.0859847.8101
709.5701 837.915 730.996 839.357795.7328844.8879806.2509838.39811029.192 835.159
1043.712843.4581  1046.8835.65891399.197834.23491407.041 833.892 1464.26 832.645
1518.706  831.831519.463 831.994 1567.09843.3871 1578.43 835.6371643.228834.3409
1657.092 833.0411676.379838.91551771.526 885.0231775.403 893.8691811.862890.1401
2048.576 922.3082257.207924.00612288.482933.83592325.425929.86282520.676 946.649
#Mann= 11 ,-1 , 0
       0    .052       0214.5091    .036       0 378.101    .052       0
709.5701    .026       0 730.996    .052       01407.041    .057       0
 1464.26    .037       01519.463    .057       01643.228    .082       0
1657.092    .036       01811.862    .052       0
Levee=-1,1399.197,834.5302,-1,1676.379,838.9194,,
#XS Ineff= 2 ,-1
  731.52 1120.14835.7616  1181.1  1295.4834.8472
Permanent Ineff=
       T       T
Bank Sta=1399.197,1676.379
XS Rating Curve= 0 ,0
Exp/Cntr=0.3,0.1

Type RM Length L Ch R = 1 ,56.61452,154.6561,152.439,145.713
XS GIS Cut Line= 6
       567217.92      4824315.09       567565.59      4824907.71
       567561.86      4824988.46       567965.19      4825570.82
       568096.05      4825783.83       568680.54      4826481.95
#Sta/Elev= 30
       0840.7411551.0991844.2789716.8491 836.498734.5201839.35391084.303835.5541
1113.789842.76811362.723  834.811386.251841.37821443.263833.57011489.248 841.657
1513.219  835.271521.789833.43111587.988  831.731597.399831.26391618.845   832.2
1637.571 832.5271646.802831.77511683.149838.7709 1765.75834.49211799.507835.7049
1813.557838.6321 1900.34 877.9211939.819881.88212154.499916.85392216.004908.9091
2430.219935.92412501.072  932.982535.679943.60692625.433 940.8492637.415 948.391
#Mann= 11 ,-1 , 0
       0    .052       0716.8491    .026       0734.5201    .052       0
1521.789    .057       01587.988    .037       01618.845    .082       0
1637.571    .037       01646.802    .057       0 1765.75    .082       0
1799.507    .036       01939.819    .052       0
Levee=-1,1513.219,835.6,-1,1813.557,838.6359,,
#XS Ineff= 2 ,-1
  746.76 1287.78835.4568 1348.74 1501.14834.2376
Permanent Ineff=
       T       T
Bank Sta=1513.219,1813.557
XS Rating Curve= 0 ,0
Exp/Cntr=0.3,0.1

Type RM Length L Ch R = 1 ,56.52000,172.2278,152.439,107.563
XS GIS Cut Line= 6
       566997.47      4824427.27       567348.67      4824904.82
       567344.94      4824985.58       567967.25      4825848.06
       568071.61      4825929.36       568622.97      4826534.63
#Sta/Elev= 30
       0 841.768182.5091 840.127 194.695847.5961219.9839838.9528 614.265836.6531
  631.47839.48811115.374 836.0671129.736843.62791142.794835.79911396.508834.3531
1399.557840.97191405.286 834.0381540.099831.69591570.735835.14431594.133831.7849
1631.127 831.0581646.285832.4061 1812.15832.0391 1851.13833.24211878.931838.8173
1910.766864.37591950.864 874.0571986.263889.01382151.229 889.325 2165.09897.9692
2177.027 890.8172286.896 901.8772481.525922.90522546.939 938.3422688.251 944.421
#Mann= 11 ,-1 , 0
       0    .052       0 614.265    .026       0  631.47    .052       0
1540.099    .057       01594.133    .037       01646.285    .057       0
 1812.15    .082       0 1851.13    .036       01950.864    .052       0
2286.896    .036       02481.525    .052       0
Levee=-1,1570.735,835.1855,-1,1878.931,838.8157,,
#XS Ineff= 2 ,-1
  716.28  1333.5 835.152 1386.84 1539.24834.2376
Permanent Ineff=
       T       T
Bank Sta=1570.735,1878.931
XS Rating Curve= 0 ,0
Exp/Cntr=0.3,0.1

Type RM Length L Ch R = 1 ,56.42501,143.9561,117.8061,61.9
XS GIS Cut Line= 6
       566843.95      4824728.65       566965.49       4824876.7
        566961.1      4824952.61       567687.06      4825799.25
       567905.78      4825920.33        568573.4      4826583.71
#Sta/Elev= 30
       0839.3302213.3859839.3658233.9779838.1561733.5991842.9719827.7469835.9951
845.8889 844.769850.8419835.9521 879.452834.83011003.557841.06091014.069834.6171
1024.093841.1468 1031.66834.56011331.627833.90911349.857839.96911439.388832.2469
1460.961 834.5631483.661833.14521532.454830.95091534.626 831.4021683.147 832.788
1717.381834.10021730.941841.70321793.572 868.5491843.832889.82791950.072 881.616
2054.577 890.4392069.506891.53082410.334  926.262432.894 935.9542574.012939.4951
#Mann= 12 ,-1 , 0
       0    .052       0213.3859    .026       0233.9779    .052       0
1439.388    .057       01483.661    .037       01534.626    .057       0
1683.147    .082       01717.381    .036       01793.572    .052       0
1950.072    .036       02054.577    .052       02069.506    .036       0
Levee=-1,1460.961,834.579,-1,1730.941,841.7052,,
#XS Ineff= 2 ,-1
   533.4 1196.34834.5424  1257.3 1424.94834.2376
Permanent Ineff=
       T       T
Bank Sta=1460.961,1730.941
XS Rating Curve= 0 ,0
Exp/Cntr=0.3,0.1

Type RM Length L Ch R = 1 ,56.35160,126.3859,114.82,104.5979
BEGIN DESCRIPTION:
FEMA XS "BR"
PROJECT XS "BX"
END DESCRIPTION:
XS GIS Cut Line= 6
       566675.24      4824822.83       567686.92      4825966.46
       567698.82      4825979.91       567886.72      4825956.62
       567946.77      4826015.63       568549.32      4826607.79
#Sta/Elev= 30
       0837.3079 41.8119838.6191758.2321843.5419786.1819 835.679 831.474842.1401
848.6879834.66611258.359 833.9771304.699834.45221399.868 833.5241420.502841.4629
1446.499 831.5911519.732 841.3581539.593 833.9981555.775833.85161566.745830.0508
1601.112831.62791639.729830.97321649.849832.57311767.296 830.8641802.982  835.59
1811.777841.66091883.735 875.3171938.539882.25791976.031889.28382004.586880.9869
2051.038873.77812114.065889.84282502.398924.39892516.845933.40092663.194 932.877
#Mann= 12 ,-1 , 0
       0    .026       0 41.8119    .052       01258.359    .036       0
1304.699    .052       01539.593    .057       01601.112    .037       0
1639.729    .082       01649.849    .057       01767.296    .082       0
1802.982    .036       01938.539    .052       02004.586    .036       0
Levee=-1,1555.775,833.8414,-1,1811.777,841.6625,,
#XS Ineff= 2 ,-1
   533.4  1219.2834.2376 1310.64 1440.18833.9328
Permanent Ineff=
       T       T
Bank Sta=1555.775,1811.777
XS Rating Curve= 0 ,0
Exp/Cntr=0.3,0.1

Type RM Length L Ch R = 1 ,56.28005,82.065,142.9649,175.9489
XS GIS Cut Line= 5
       566324.43      4825131.52       567704.52      4826111.99
       567852.67      4826064.47       567905.09      4826079.84
       568502.26      4826652.35
#Sta/Elev= 30
       0835.8829 355.498842.6909376.2491 844.221  394.09845.4351399.1179 836.669
456.5221836.73691000.963833.74811112.308 839.4421217.406834.39491225.005 841.205
1260.078833.62591404.243837.31091447.757832.79621456.991841.33481464.843833.7091
1495.319 830.7441520.263840.22911532.019832.23411708.124833.82411708.136 833.824
1773.119831.75991789.243830.14421817.898830.82811889.707834.57411907.679841.7937
1962.029857.86512045.101860.89812136.479889.32712412.727911.73792730.396922.6589
#Mann= 11 ,-1 , 0
       0    .036       0 355.498    .046       0376.2491    .036       0
456.5221    .046       01000.963    .052       01260.078    .036       0
1404.243    .052       01708.136    .057       01773.119    .037       0
1817.898    .082       01889.707    .036       0
Levee=-1,1708.124,833.8048,-1,1907.679,841.7997,,
#XS Ineff= 3 ,-1
   533.4 1135.38833.9328 1203.96 1234.44834.8472 1402.08 1470.66833.3232
Permanent Ineff=
       T       T       T
Bank Sta=1708.124,1907.679
XS Rating Curve= 0 ,0
Exp/Cntr=0.3,0.1

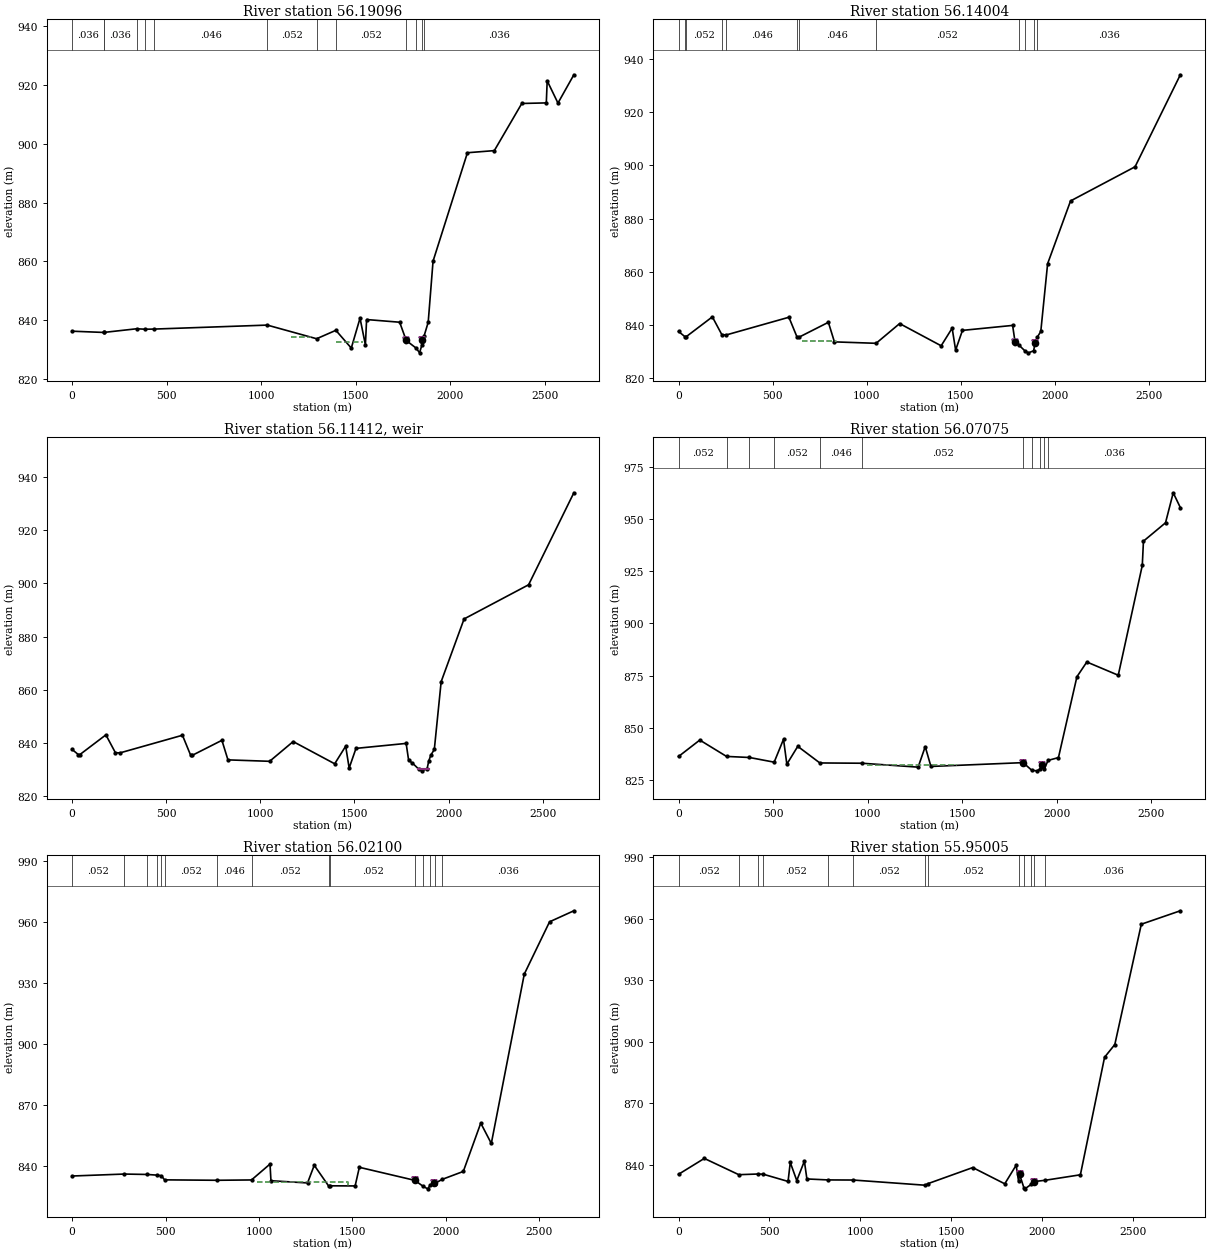
Type RM Length L Ch R = 1 ,56.19096,84.3601,81.726,81.7111
XS GIS Cut Line= 4
       566296.68      4825159.27       567726.36      4826168.03
       567839.58       4826244.2       568466.97      4826684.29
#Sta/Elev= 30
       0836.2349166.5799835.8131166.8451835.8061 341.383 837.061 386.476 836.908
 432.895836.9552 1031.84 838.311 1292.85833.66831394.443836.53391475.991 830.484
1522.244840.66611550.602831.57481556.963840.20011731.686839.28811766.538833.0708
 1766.86 833.062 1818.85 830.4631837.059 828.8711849.089831.52391851.761833.2526
1861.556834.76491882.541839.26711908.198860.06392089.958896.96212232.064 897.682
2377.385913.72392506.892913.91692511.554921.43382568.506 913.8592652.545 923.487
#Mann= 13 ,-1 , 0
       0    .036       0166.5799    .052       0166.8451    .036       0
 341.383    .046       0 386.476    .036       0 432.895    .046       0
 1031.84    .052       0 1292.85    .036       01394.443    .052       0
 1766.86    .057       0 1818.85    .037       01849.089    .082       0
1861.556    .036       0
Levee=-1,1766.538,833.0489,-1,1851.761,833.2988,,
#XS Ineff= 4 ,-1
  563.88 1097.28833.9328 1158.24 1264.92834.2376 1394.46 1463.04832.7136
  1485.9 1539.24832.7136
Permanent Ineff=
       T       T       T       T
Bank Sta=1766.538,1851.761
XS Rating Curve= 0 ,0
Exp/Cntr=0.3,0.1

Type RM Length L Ch R = 1 ,56.14004,110.6561,111.192,112.3441
XS GIS Cut Line= 4
       566211.83       4825228.1       567642.69      4826213.23
       567852.87       4826348.6       568420.21      4826720.08
#Sta/Elev= 30
       0837.6752 33.0501835.7479 42.1121 835.768179.6461843.1421230.0179836.4651
253.4729836.3529586.2941842.9979 629.818835.4891 639.147835.4809 795.894841.0971
827.9511833.74991049.341833.21111174.422 840.6251394.969832.27891453.333 838.895
1471.784830.67691508.107838.06711774.525839.93181787.725833.58161807.895832.5481
1842.278830.21391858.499829.63091885.723 830.3881894.582833.33051905.446 835.508
1924.152837.65991960.458863.11712082.237 886.6832424.897899.51692665.332934.0721
#Mann= 12 ,-1 , 0
       0    .052       0 33.0501    .036       0 42.1121    .052       0
230.0179    .036       0253.4729    .046       0 629.818    .052       0
 639.147    .046       01049.341    .052       01807.895    .057       0
1842.278    .037       01885.723    .082       01905.446    .036       0
Levee=-1,1787.725,833.3872,-1,1894.582,833.4177,,
#XS Ineff= 4 ,-1
  655.32   838.2833.9328 1082.04 1310.64 833.628 1386.84 1463.04832.4088
 1493.52 1569.72832.4088
Permanent Ineff=
       T       T       T       T
Bank Sta=1787.725,1894.582
XS Rating Curve= 0 ,0
Exp/Cntr=0.5,0.3

Type RM Length L Ch R = 5 ,56.11412,,,
BEGIN DESCRIPTION:
RM 56.11
END DESCRIPTION:
IW Pilot Flow=0
#Inline Weir SE= 3
 1836.42830.42761856.232830.42761894.332830.4276
IW Dist,WD,Coef,Skew,MaxSub,Min_El,Is_Ogee,SpillHt,DesHd
42.672,4.572,1.27,0,0.98,, 0 ,,,1,1,

Type RM Length L Ch R = 1 ,56.07075,77.6719,79.828,81.9251
BEGIN DESCRIPTION:
FEMA XS "BQ"
PROJECT XS "BW"
END DESCRIPTION:
XS GIS Cut Line= 4
       566120.89       4825317.5       567520.24      4826261.51
       567781.12       4826437.5       568321.35      4826801.94
#Sta/Elev= 30
       0836.2029  112.42844.0781253.7561836.2402375.3249 835.726 505.918 833.485
 555.334 844.467 572.949832.5209630.6979  841.07747.4641 833.108 969.367832.9778
1267.343831.10091304.928840.92611335.063831.43591820.049833.25231824.332833.1321
1868.925829.57291895.524  829.331912.988830.08811922.142832.05861934.222830.1219
1954.926834.34612009.659835.66992107.359874.41912159.728 881.499 2326.02875.1439
2453.134927.78592459.265   939.42576.023 948.2092616.727962.59312654.346955.5151
#Mann= 11 ,-1 , 0
       0    .052       0253.7561    .036       0375.3249    .046       0
 505.918    .052       0747.4641    .046       0 969.367    .052       0
1824.332    .057       01868.925    .037       01912.988    .082       0
1934.222    .057       01954.926    .036       0
Levee=-1,1820.049,833.2501,-1,1922.142,832.0887,,
#XS Ineff= 2 ,-1
  998.22 1470.66 832.104 1516.38 1584.96 832.104
Permanent Ineff=
       T       T
Bank Sta=1820.049,1922.142
XS Rating Curve= 0 ,0
Exp/Cntr=0.5,0.3

Type RM Length L Ch R = 1 ,56.02100,106.669,113.858,127.019
XS GIS Cut Line= 6
       566100.76      4825331.13       567306.35      4826146.73
       567391.42      4826261.95       567534.87      4826359.91
       567711.91      4826492.22       568284.91      4826878.06
#Sta/Elev= 30
       0835.0609 278.899836.0258402.6451 835.822455.2569 835.487478.3422835.1648
 494.716833.1778776.2991832.9659959.9051833.13091058.918840.93711063.925 832.745
1259.633 831.6591295.519840.33781371.945 830.2171381.877830.25081514.231830.1832
1536.763 839.3431833.912832.92211834.049832.8966 1878.74  829.95 1902.17828.7618
1917.394830.71691933.493831.71691939.674 831.3561980.207833.42412092.933837.3148
2186.257861.05082242.698851.05282419.128934.27692554.345  959.962684.298 965.379
#Mann= 15 ,-1 , 0
       0    .052       0 278.899    .036       0402.6451    .046       0
455.2569    .052       0478.3422    .046       0 494.716    .052       0
776.2991    .046       0959.9051    .052       01371.945    .026       0
1381.877    .052       01833.912    .057       0 1878.74    .037       0
1917.394    .082       01939.674    .057       01980.207    .036       0
Levee=-1,1834.049,832.9208,-1,1933.493,831.7535,,
#XS Ineff= 2 ,-1
   990.6 1478.28 832.104    1524 1615.44 832.104
Permanent Ineff=
       T       T
Bank Sta=1834.049,1933.493
XS Rating Curve= 0 ,0
Exp/Cntr=0.3,0.1

Type RM Length L Ch R = 1 ,55.95005,140.6649,152.439,172.037
XS GIS Cut Line= 6
       566059.47      4825358.91       567251.78      4826176.12
       567286.77      4826285.96       567476.22      4826422.68
       567638.27      4826613.04       568251.49      4826986.18
#Sta/Elev= 30
       0 835.501141.9271843.2298331.7419 835.312 436.153835.6351466.2611835.5461
602.9301832.0229615.0129841.2709 650.855 832.467692.7671841.8951706.5862833.2369
 822.863832.7639961.5261  832.71 1358.18830.18011372.543830.93691619.624838.7791
1795.763830.86991858.335839.90111871.675832.19391877.245835.47611900.678829.0481
1906.489828.42411941.006830.57091955.277831.9351 1955.37 831.9442018.624 832.599
2212.054835.26112345.181892.46812401.592 898.6682547.443957.22292762.212963.7639
#Mann= 13 ,-1 , 0
       0    .052       0331.7419    .036       0 436.153    .046       0
466.2611    .052       0 822.863    .046       0961.5261    .052       0
 1358.18    .026       01372.543    .052       01871.675    .057       0
1900.678    .037       01941.006    .082       0 1955.37    .057       0
2018.624    .036       0
Levee=-1,1877.245,835.4751,-1,1955.277,831.9272,,
#XS Ineff= 2 ,-1
  982.98 1478.28831.7992    1524 1661.16831.7992
Permanent Ineff=
       T       T
Bank Sta=1877.245,1955.277
XS Rating Curve= 0 ,0
Exp/Cntr=0.3,0.1

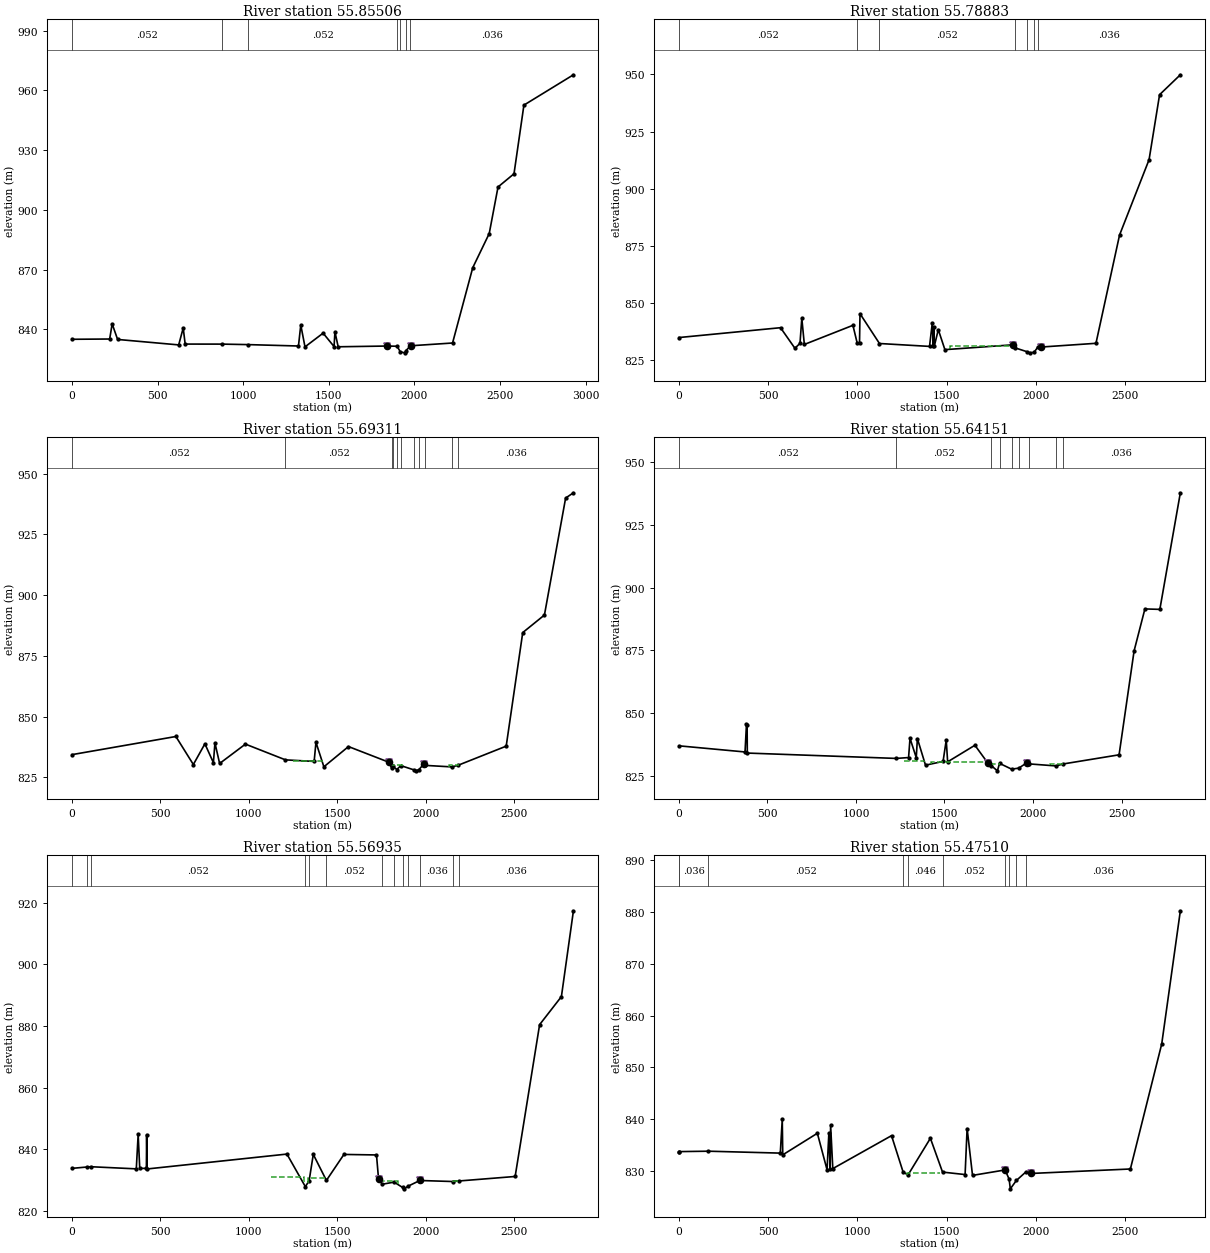
Type RM Length L Ch R = 1 ,55.85506,105.7001,106.2911,109.482
XS GIS Cut Line= 6
       565931.13      4825405.15       567076.33      4826207.68
        567133.4      4826312.13       567377.94      4826470.94
       567468.29      4826704.04       568217.77      4827145.42
#Sta/Elev= 30
       0835.0219 219.801835.1569234.2781842.7562266.1681 834.938622.9801832.2021
649.3911840.6982660.7619832.6152876.2939832.59991029.177 832.3461322.609831.6459
1336.093842.18711360.725 831.2131466.545   838.1 1530.55831.37181535.688838.7471
1554.539831.25791838.633831.63181898.734831.53191917.771 828.6921944.193828.2159
1950.281829.30681975.176831.58891981.182831.78222222.725833.15192340.633870.9639
2436.884888.10312488.341911.50592581.696918.12892639.533952.6021 2928.79967.8409
#Mann= 7 ,-1 , 0
       0    .052       0876.2939    .046       01029.177    .052       0
1898.734    .057       01917.771    .037       01950.281    .082       0
1975.176    .036       0
Levee=-1,1838.633,831.6864,-1,1981.182,831.79,,
#XS Ineff= 2 ,-1
 1051.56 1432.56831.7992 1463.04 1844.04831.4944
Permanent Ineff=
       T       T
Bank Sta=1838.633,1981.182
XS Rating Curve= 0 ,0
Exp/Cntr=0.3,0.1

Type RM Length L Ch R = 1 ,55.78883,165.8551,153.614,147.0709
XS GIS Cut Line= 6
       565825.16      4825413.89       567021.41      4826241.23
       567060.13      4826320.88        567267.9      4826465.17
       567377.85      4826780.11       567979.78      4827096.09
#Sta/Elev= 30
       0834.9539569.0491839.2531649.6782830.2651 678.166832.4188688.3021 843.384
702.5305831.9302974.7479840.2949998.7448832.49291011.719832.74191014.383 845.375
1123.483832.3451 1403.98831.07981419.369 841.2161425.352831.05491428.392839.6591
1431.117831.3091 1453.11838.40391490.084829.65891873.584831.78831882.024830.4739
1950.854828.74691967.036828.26721989.624 828.4722010.133830.70712026.905830.7899
2336.566832.43192468.852879.77592634.156912.68212693.066 941.092 2809.41 949.794
#Mann= 7 ,-1 , 0
       0    .052       0998.7448    .046       01123.483    .052       0
1882.024    .057       01950.854    .037       01989.624    .082       0
2010.133    .036       0
Levee=-1,1873.584,831.5798,-1,2026.905,830.7933,,
#XS Ineff= 2 ,-1
    1143 1478.28 832.104 1516.38 1874.52831.1896
Permanent Ineff=
       T       T
Bank Sta=1873.584,2026.905
XS Rating Curve= 0 ,0
Exp/Cntr=0.3,0.1

Type RM Length L Ch R = 1 ,55.69311,79.6241,82.8011,83.5149
BEGIN DESCRIPTION:
FEMA XS "BP"
PROJECT XS "BV"
END DESCRIPTION:
XS GIS Cut Line= 6
       565739.97      4825472.42       566879.28      4826269.53
       566893.49      4826371.99       567108.06      4826522.75
       567245.66      4826819.19       567918.75      4827155.83
#Sta/Elev= 30
       0834.3851587.1701841.8448 686.067 830.316751.2951838.8318799.4191831.0789
808.1431  839.19 834.686830.7369980.6019  838.711207.098 832.2281369.176 831.591
1379.464839.44391424.239 829.3771563.403837.70281793.803831.19931807.102828.7579
1815.042829.60411836.592 828.262 1859.56829.85221934.419828.09411945.538827.7131
 1961.64828.22081987.857830.37491998.219 829.9542148.787829.32792182.247829.9759
2455.349837.87382548.837884.60392671.589891.83422791.406939.9709 2835.56942.1411
#Mann= 11 ,-1 , 0
       0    .052       01207.098    .052       01807.102    .026       0
1815.042    .057       01836.592    .026       0 1859.56    .057       0
1934.419    .037       0 1961.64    .082       01998.219    .036       0
2148.787    .026       02182.247    .036       0
Levee=-1,1793.803,831.1926,-1,1987.857,830.4093,,
#XS Ineff= 4 ,-1
1794.4641871.396830.27522133.3622189.238829.9704 1249.68 1417.32831.7992
 1455.42 1783.08830.8848
Permanent Ineff=
       T       T       T       T
Bank Sta=1793.803,1987.857
XS Rating Curve= 0 ,0
Exp/Cntr=0.3,0.1

Type RM Length L Ch R = 1 ,55.64151,140.6521,115.796,100.5419
XS GIS Cut Line= 6
       565721.71      4825506.45       566822.82      4826279.02
       566840.05      4826402.86       567032.25      4826537.43
       567161.77       4826841.2       567863.65      4827219.48
#Sta/Elev= 30
       0837.0359 373.234 834.593381.2679845.5881384.8859 845.464386.1231834.1572
1226.956832.02591297.087832.36881305.145840.02091340.457  832.361346.886839.9139
1392.745 829.3381491.947830.83391509.801839.31591517.784830.66811671.797837.2621
1744.105830.25641764.529829.13711798.864827.08311810.979 830.0611878.954 827.757
1919.456828.15891964.887830.28391978.085829.84482131.596829.0301    2167829.7811
  2486.2  833.462571.078874.84222632.058891.51592716.501891.34312832.309 937.741
#Mann= 9 ,-1 , 0
       0    .052       01226.956    .052       01764.529    .026       0
1810.979    .057       01878.954    .037       01919.456    .082       0
1978.085    .036       02131.596    .026       0    2167    .036       0
Levee=-1,1744.105,830.3361,-1,1964.887,830.3178,,
#XS Ineff= 4 ,-1
1754.7281812.554829.97042094.4152178.198829.9704 1272.54 1386.84831.1896
 1424.94 1737.36  830.58
Permanent Ineff=
       T       T       T       T
Bank Sta=1744.105,1964.887
XS Rating Curve= 0 ,0
Exp/Cntr=0.3,0.1

Type RM Length L Ch R = 1 ,55.56935,181.2801,151.254,107.036
XS GIS Cut Line= 6
       565593.22      4825584.96       566636.29      4826334.82
       566652.09      4826413.07       566862.12       4826568.8
       567082.94      4826877.19         567813.      4827273.34
#Sta/Elev= 30
       0 833.834 84.2251834.2699  105.21834.3659363.4021 833.671373.9189844.8458
382.8809 833.845420.3841 833.809421.9429844.7709424.4331833.63591215.316 838.467
1319.804827.88011341.073829.86581364.467  838.361438.626829.9161 1537.77838.3491
1721.967 838.1831733.739830.2812 1755.39 828.6971821.749829.36691869.675827.6338
1880.036827.18911899.735828.02791967.146829.89651967.228 829.897 2157.23829.5532
2189.842 829.7462506.202831.20092644.581880.45292767.858 889.5532835.848917.3959
#Mann= 13 ,-1 , 0
       0    .052       0 84.2251    .036       0  105.21    .052       0
1319.804    .057       01341.073    .046       01438.626    .052       0
 1755.39    .026       01821.749    .057       01869.675    .037       0
1899.735    .082       01967.228    .036       0 2157.23    .026       0
2189.842    .036       0
Levee=-1,1733.739,830.2935,-1,1967.146,829.9095,,
#XS Ineff= 5 ,-1
1744.4771840.992829.66562152.0132192.082829.6656 1127.76 1310.64831.1896
 1493.52 1722.12  830.58  1333.5 1432.56  830.58
Permanent Ineff=
       T       T       T       T       T
Bank Sta=1733.739,1967.146
XS Rating Curve= 0 ,0
Exp/Cntr=0.3,0.1

Type RM Length L Ch R = 1 ,55.47510,150.4599,152.439,155.2301
XS GIS Cut Line= 4
       565542.49      4825628.63       566804.33      4826834.68
       567027.37       4826947.6       567738.04      4827346.38
#Sta/Elev= 30
       0833.7801  2.2479833.8082165.2519833.8871567.9869833.5189 579.017840.0221
581.7971 833.187775.7458837.3381830.1179830.3011840.3431 837.423847.5189830.5389
849.9698838.9462 862.309 830.5371191.422836.87811256.253 829.8971283.514829.2959
1409.341836.37481477.432829.86581603.857  829.391615.176  838.251645.496 829.231
1827.648830.2767 1827.89830.30381850.655828.50181857.331826.64291891.405828.2571
 1943.96829.87591972.745829.60142530.349 830.4632706.019854.53092810.409880.1578
#Mann= 10 ,-1 , 0
       0    .052       0  2.2479    .036       0165.2519    .052       0
1256.253    .057       01283.514    .046       01477.432    .052       0
 1827.89    .082       01850.655    .037       01891.405    .082       0
 1943.96    .036       0
Levee=-1,1827.648,830.3148,-1,1972.745,829.6108,,
#XS Ineff= 3 ,-1
  883.92  1219.2830.8848 1508.76 1813.56829.6656 1280.16 1463.04829.6656
Permanent Ineff=
       T       T       T
Bank Sta=1827.648,1972.745
XS Rating Curve= 0 ,0
Exp/Cntr=0.3,0.1