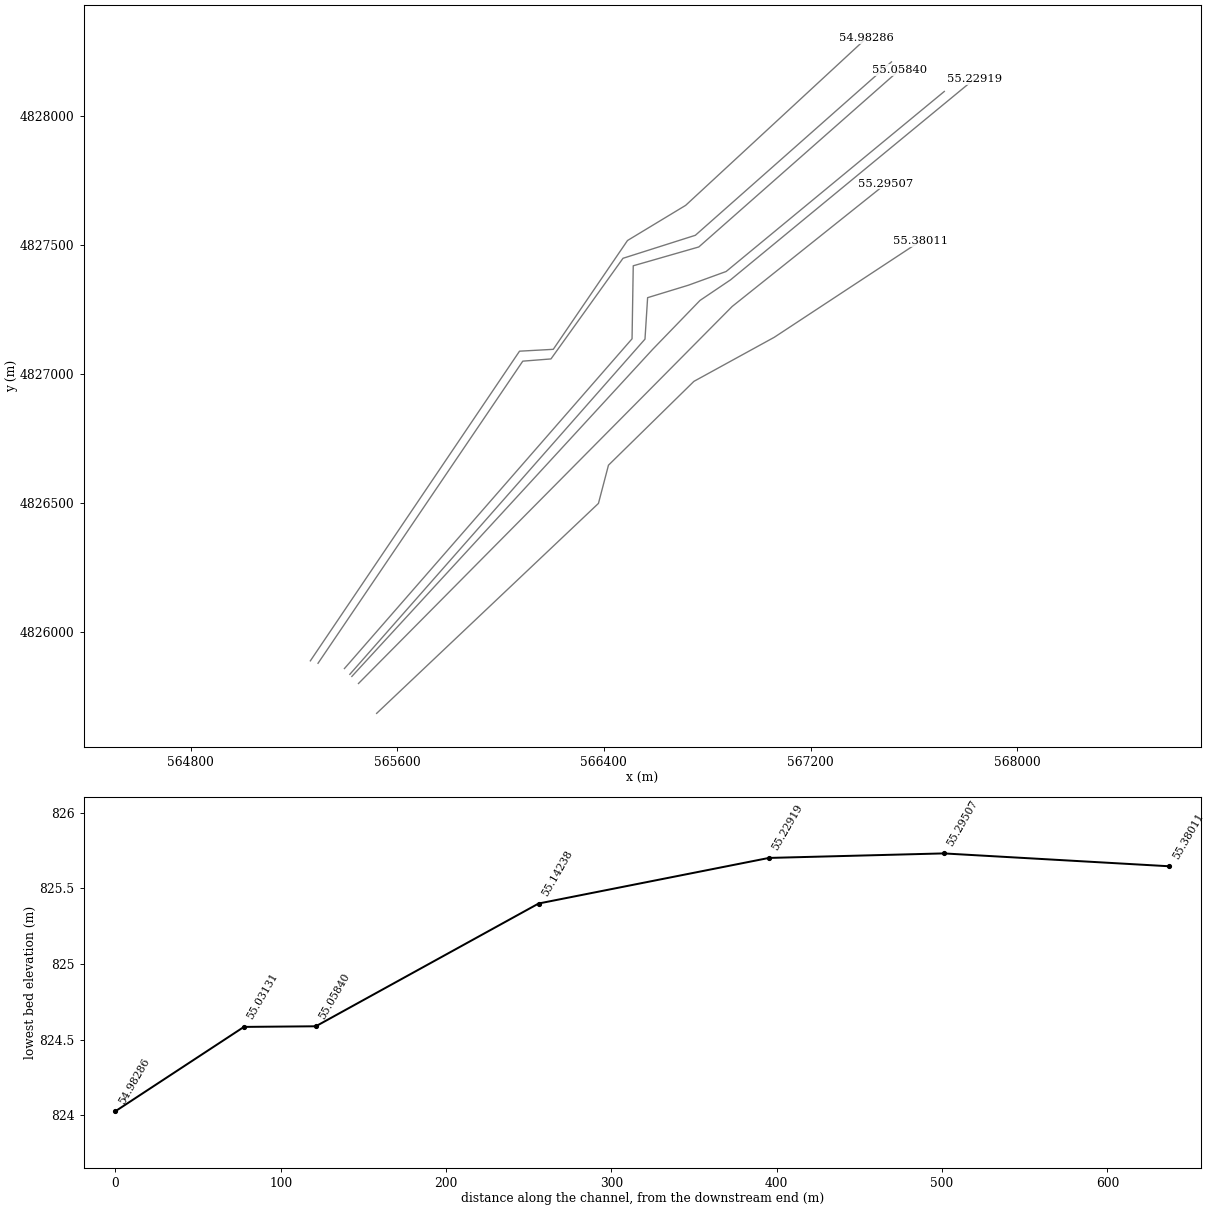
HEC-RAS study Boise2.prj: BoiseRiver_All_reaches

--- Boise2.g01 (geometry) --- (continued)

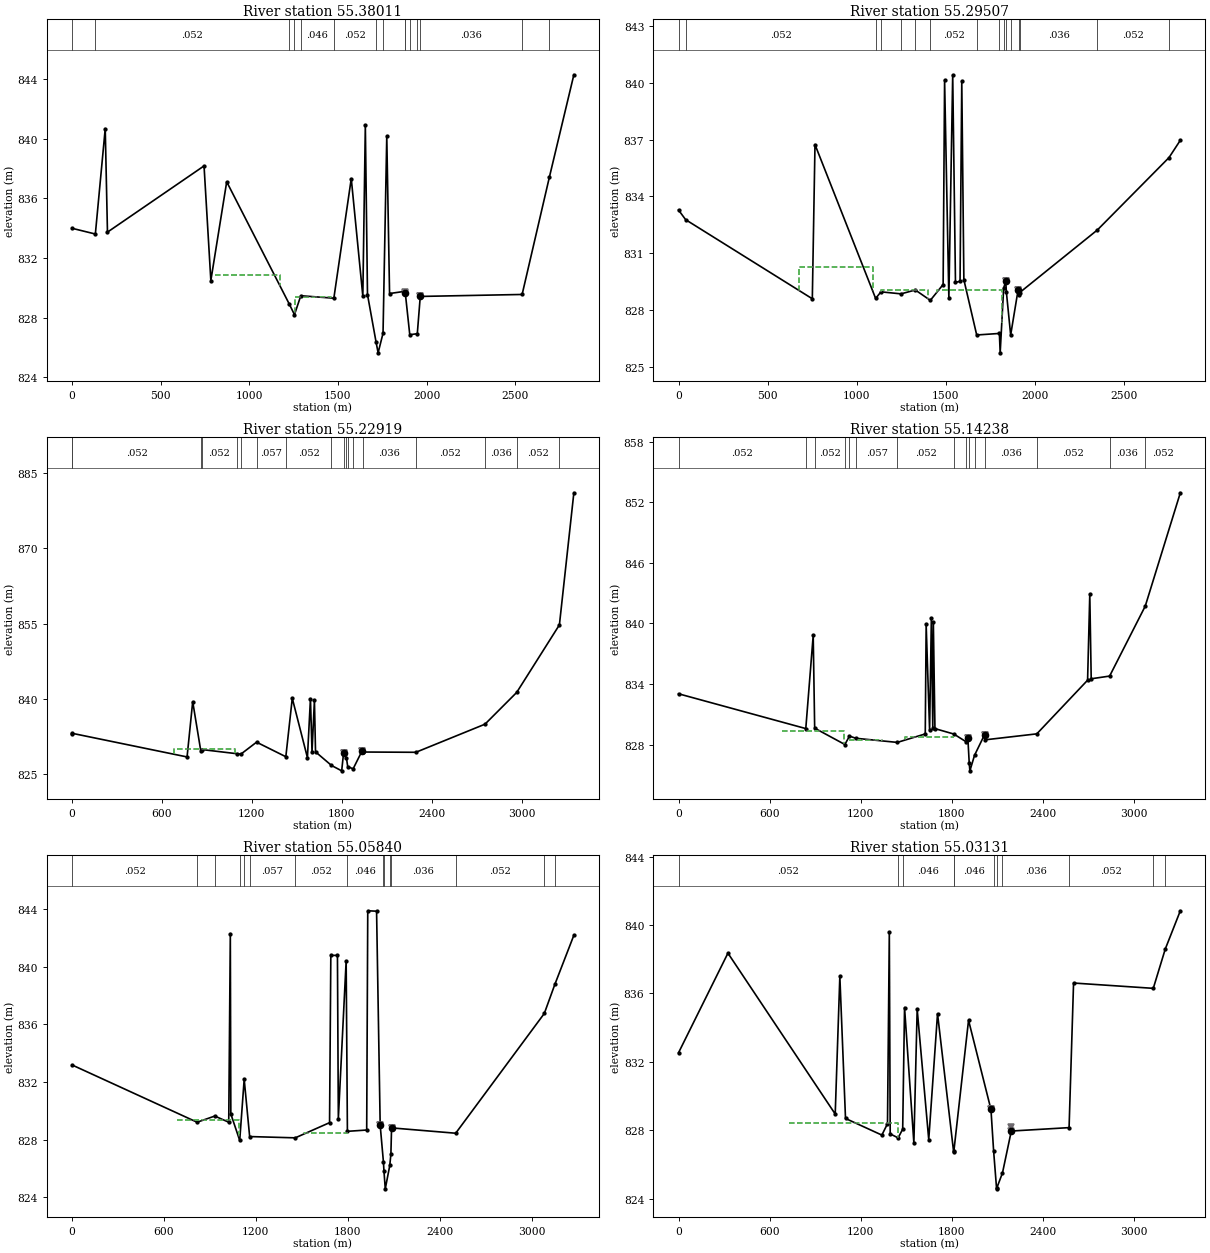
Type RM Length L Ch R = 1 ,55.38011,124.9299,136.483,149.4182
XS GIS Cut Line= 6
       565520.29      4825686.54       566378.87      4826499.26
       566417.64      4826647.14       566748.27      4826971.58
       567059.54      4827142.34       567625.67      4827514.85
#Sta/Elev= 30
       0833.9871131.3709833.6021187.1161840.6661199.7101833.7289 744.602 838.165
 782.972830.4901872.4458837.10091226.421828.89111254.732 828.2011290.403 829.469
1476.971 829.3051575.207 837.3131640.467829.44091654.586 840.892 1666.77829.5471
1714.781 826.3891726.742 825.6451754.416826.95721775.512 840.1471791.292829.6171
1879.266 829.7681879.833829.75011880.217829.63571905.312826.85681947.778826.9279
1964.482 829.4231964.512829.4227 2539.19829.55492693.483 837.4382831.073844.2689
#Mann= 15 ,-1 , 0
       0    .036       0131.3709    .052       01226.421    .057       0
1254.732    .052       01290.403    .046       01476.971    .052       0
1714.781    .026       01754.416    .052       01879.266    .057       0
1879.833    .082       01905.312    .037       01947.778    .082       0
1964.482    .036       0 2539.19    .052       02693.483    .036       0
Levee=-1,1880.217,829.7449,-1,1964.512,829.4218,,
#XS Ineff= 3 ,-1
  807.72 1173.48830.8848 1501.14 1874.52829.3608  1257.3 1463.04829.3608
Permanent Ineff=
       T       T       T
Bank Sta=1880.217,1964.512
XS Rating Curve= 0 ,0
Exp/Cntr=0.3,0.1

Type RM Length L Ch R = 1 ,55.29507,104.5141,105.7242,104.7019
BEGIN DESCRIPTION:
FEMA XS "BO"
PROJECT XS "BU"
END DESCRIPTION:
XS GIS Cut Line= 5
       565450.07      4825802.19       566722.71      4827086.18
       566896.63      4827261.66       567233.09      4827530.31
       567490.98      4827736.23
#Sta/Elev= 30
       0 833.282   39.98832.7718750.6011828.5891765.6548 836.7441105.915828.6071
1135.758828.95611248.095828.84911328.618 829.053  1412.8828.50621484.593829.3441
1492.805840.15591516.733828.62711538.334840.4351 1553.84829.45811579.514829.5101
1589.189 840.0881600.979829.59611672.949 826.6741800.208 826.756 1804.67  825.73
 1824.14829.13711835.786829.53971839.343828.95781863.556 826.6731905.427829.0696
1909.448828.79511914.234 828.9182350.068 832.2282752.117836.05792815.465836.9711
#Mann= 16 ,-1 , 0
       0    .036       0   39.98    .052       01105.915    .057       0
1135.758    .052       01248.095    .057       01328.618    .046       0
  1412.8    .052       01672.949    .026       01800.208    .052       0
 1824.14    .057       01839.343    .082       01863.556    .037       0
1909.448    .082       01914.234    .036       02350.068    .052       0
2752.117    .036       0
Levee=-1,1835.786,829.5528,-1,1905.427,829.0712,,
#XS Ineff= 3 ,-1
  678.18 1089.66830.2752  1447.8 1813.56 829.056 1135.38 1402.08 829.056
Permanent Ineff=
       T       T       T
Bank Sta=1835.786,1905.427
XS Rating Curve= 0 ,0
Exp/Cntr=0.3,0.1

Type RM Length L Ch R = 1 ,55.22919,158.158,139.304,98.647
XS GIS Cut Line= 5
       565424.38      4825829.52       566588.63      4827095.47
       566771.84      4827284.82       566890.54      4827364.87
       567834.01      4828141.91
#Sta/Elev= 30
       0833.1041  2.6789833.1602767.4748828.4659805.0981 839.475858.9721829.6821
865.3351829.94121097.743829.11911126.878829.03311231.361831.40911426.597828.5101
1469.598 840.1481570.679828.33211590.917 840.0661601.373 829.4771617.432839.7512
1624.781829.4791 1731.34  826.77 1799.29825.7001 1811.89829.23571812.046829.1511
1831.469 828.2021839.506  826.551875.674   826.1  1935.3829.66351940.306829.4479
2294.276829.39312755.743 834.9922967.389841.31593252.374854.76593348.819 881.068
#Mann= 18 ,-1 , 0
       0    .036       0  2.6789    .052       0858.9721    .036       0
865.3351    .052       01097.743    .057       01126.878    .052       0
1231.361    .057       01426.597    .052       0 1731.34    .026       0
1812.046    .057       01831.469    .082       01839.506    .037       0
1875.674    .082       01940.306    .036       02294.276    .052       0
2755.743    .036       02967.389    .052       03252.374    .036       0
Levee=-1,1811.89,829.2846,-1,1935.3,829.6625,,
#XS Ineff= 3 ,-1
  678.18 1089.66829.9704 1478.28 1811.25828.7512 1127.76  1371.6828.7512
Permanent Ineff=
       T       T       T
Bank Sta=1811.89,1935.3
XS Rating Curve= 0 ,0
Exp/Cntr=0.3,0.1

Type RM Length L Ch R = 1 ,55.14238,134.4421,134.771,132.4191
XS GIS Cut Line= 6
       565416.63      4825837.76       566559.01      4827135.14
       566569.18      4827295.62       566727.06      4827343.85
       566873.17      4827396.95       567717.57      4828093.84
#Sta/Elev= 30
       0833.0278838.1061829.5839886.9439838.8099896.6009829.62511095.552828.0059
1125.957828.84021167.598828.62291440.907828.2142 1624.92 829.0531630.884839.8901
1653.501829.43091665.168840.49211674.536829.60191678.196840.15281688.731 829.579
1813.032829.04321894.661828.26991905.521828.6305 1914.49826.16591918.865 825.399
1949.521826.93882015.371828.97742018.258828.46812359.651829.06092694.072 834.372
2708.527 842.8932717.886 834.5142839.183834.78113073.826 841.7073304.833852.9288
#Mann= 15 ,-1 , 0
       0    .052       0838.1061    .036       0896.6009    .052       0
1095.552    .057       01125.957    .052       01167.598    .057       0
1440.907    .052       01813.032    .046       01894.661    .057       0
 1914.49    .037       01949.521    .082       02018.258    .036       0
2359.651    .052       02839.183    .036       03073.826    .052       0
Levee=-1,1905.521,828.6445,-1,2015.371,828.9798,,
#XS Ineff= 3 ,-1
  678.18 1089.66829.3608 1493.52 1813.56828.7512 1120.14 1341.12828.4464
Permanent Ineff=
       T       T       T
Bank Sta=1905.521,2015.371
XS Rating Curve= 0 ,0
Exp/Cntr=0.3,0.1

Type RM Length L Ch R = 1 ,55.05840,40.8371,43.4739,43.5401
BEGIN DESCRIPTION:
FEMA XS "G"
PROJECT XS "BT"
END DESCRIPTION:
XS GIS Cut Line= 5
       565395.69      4825860.05       566508.93      4827136.39
       566513.58      4827419.02       566767.36      4827491.91
       567543.96      4828176.71
#Sta/Elev= 30
       0833.1821 816.312 829.209931.6182829.63781022.736829.20991033.095 842.295
1036.381 829.7831094.422827.94591123.576832.18991159.281 828.2151457.045 828.126
1680.921829.17911689.186840.78471732.395840.78471738.269829.46111789.249840.4098
1797.394828.57811923.351 828.6681930.254 843.8791987.839 843.8512011.384 828.997
2032.591826.45092036.195 825.8012044.572 824.5882074.193 826.218  2081.4827.0209
2085.652828.81652504.297828.4461 3082.79836.7541 3151.58  838.773275.731842.1801
#Mann= 15 ,-1 , 0
       0    .052       0 816.312    .036       0931.6182    .052       0
1094.422    .057       01123.576    .052       01159.281    .057       0
1457.045    .052       01797.394    .046       02032.591    .082       0
2036.195    .037       02074.193    .082       0  2081.4    .036       0
2504.297    .052       0 3082.79    .036       0 3151.58    .052       0
Levee=-1,2011.384,829.0103,-1,2085.652,828.8243,,
#XS Ineff= 3 ,-1
   685.8 1089.66829.3608 1516.38 1798.32828.4464 1120.14  1295.4828.1416
Permanent Ineff=
       T       T       T
Bank Sta=2011.384,2085.652
XS Rating Curve= 0 ,0
Exp/Cntr=0.3,0.1

Type RM Length L Ch R = 1 ,55.03131,66.2111,77.7429,91.1111
BEGIN DESCRIPTION:
FEMA XS "BN"
PROJECT XS "BS"
END DESCRIPTION:
XS GIS Cut Line= 6
       565293.46      4825880.46       566085.98      4827049.87
        566195.1      4827058.48       566473.96      4827448.03
       566753.99      4827537.06       567513.08      4828208.34
#Sta/Elev= 30
       0832.5371 325.677838.35791032.966828.9551 1063.53837.00211100.859828.6978
1340.441827.72581377.719 828.3871389.696839.59021395.532 827.7951447.882827.5618
1477.844828.07091490.122 835.1811551.609827.26891573.385835.0761 1649.66  827.46
1707.582834.82011812.981 826.7981814.304826.70821912.065 834.4362059.835829.2226
2077.319826.80412097.015824.58392097.831824.61692135.877825.51612193.963827.9619
2574.896828.16112604.462 836.612 3130.04836.30113209.108 838.599 3308.36840.8341
#Mann= 11 ,-1 , 0
       0    .052       01447.882    .057       01477.844    .046       0
1812.981    .052       01814.304    .046       02077.319    .083       0
2097.831    .037       02135.877    .036       02574.896    .052       0
 3130.04    .036       03209.108    .052       0
Levee=-1,2059.835,829.2236,-1,2193.963,828.2,,
#XS Ineff= 3 ,-1
  731.52  1447.8828.4464 1478.28 1783.08827.8368  1866.92059.838827.8368
Permanent Ineff=
       T       T       T
Bank Sta=2059.835,2193.963
XS Rating Curve= 0 ,0
Exp/Cntr=0.3,0.1

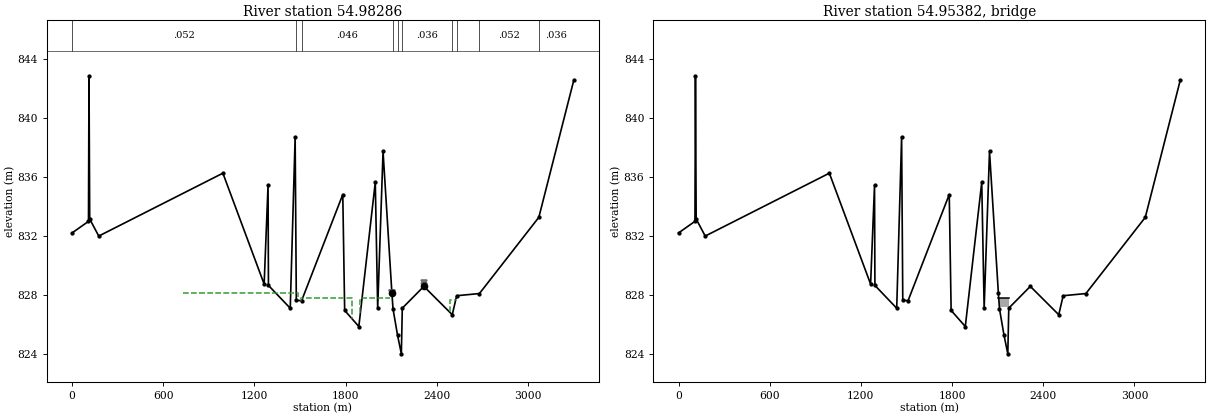
Type RM Length L Ch R = 1 ,54.98286,101.93,104.1151,105.8461
BEGIN DESCRIPTION:
FEMA XS "F"
PROJECT XS "BR"
END DESCRIPTION:
XS GIS Cut Line= 6
       565263.78      4825889.93       566073.33      4827088.47
       566203.98      4827095.65       566491.33      4827516.85
        566716.4      4827652.91       567415.34       4828299.4
#Sta/Elev= 30
       0832.2241 108.079 833.009111.3651 842.879116.0471833.1672175.5999 832.012
992.4769836.27521263.982828.75481289.711 835.4541292.342828.66581435.799 827.119
1468.011838.73031475.693827.64691510.743 827.6361781.468834.82891793.895  826.97
1887.159  825.881995.357 835.6572011.187827.12512046.442837.74582104.754828.1423
2112.068827.07792141.788 825.2952166.927824.02682173.159827.12292314.949 828.601
2502.055826.68012531.114827.96782680.702828.1138 3071.68 833.283 3302.17 842.598
#Mann= 10 ,-1 , 0
       0    .052       01475.693    .057       01510.743    .046       0
2112.068    .082       02141.788    .037       02173.159    .036       0
2502.055    .026       02531.114    .036       02680.702    .052       0
 3071.68    .036       0
Levee=-1,2104.754,828.163,-1,2314.949,828.8,,
#XS Ineff= 4 ,-1
2484.4192530.977827.6844  731.52  1485.9828.1416 1508.76 1844.04827.8368
 1897.38  2095.5827.8368
Permanent Ineff=
       T       T       T       T
Bank Sta=2104.754,2314.949
XS Rating Curve= 0 ,0
Exp/Cntr=0.3,0.1

Type RM Length L Ch R = 3 ,54.95382,,,
BEGIN DESCRIPTION:
Greenbelt Pathway Baybrook Court Bridge (RM 54.96)
END DESCRIPTION:
Bridge Culvert--1,0,-1,-1, 0
Deck Dist Width WeirC Skew NumUp NumDn MinLoCord MaxHiCord MaxSubmerge Is_Ogee
48.768,6.096,1.44,0, 2, 4, , , 0.95, 0, 0,0,,
 2103.122173.833
827.8368827.8368
827.2272827.2272
2060.4482110.4352110.4352152.193
827.8368827.8368827.8368827.8368
827.2272827.2272 826.008 826.008
BR Coef=-1 , 0 , 0 ,1.25, 0 ,,,0.8,-1,2,0,
WSPro=,,,, 1 ,,,, 0 ,,,, 0 ,,,,-1 ,-1 ,-1 , 0 , 0 , 0 , 0 , 0
BC Design=,, 0 ,, 0 ,,,,,,
BC Use User HTab Curves=0
BC User HTab FreeFlow(D)= 0