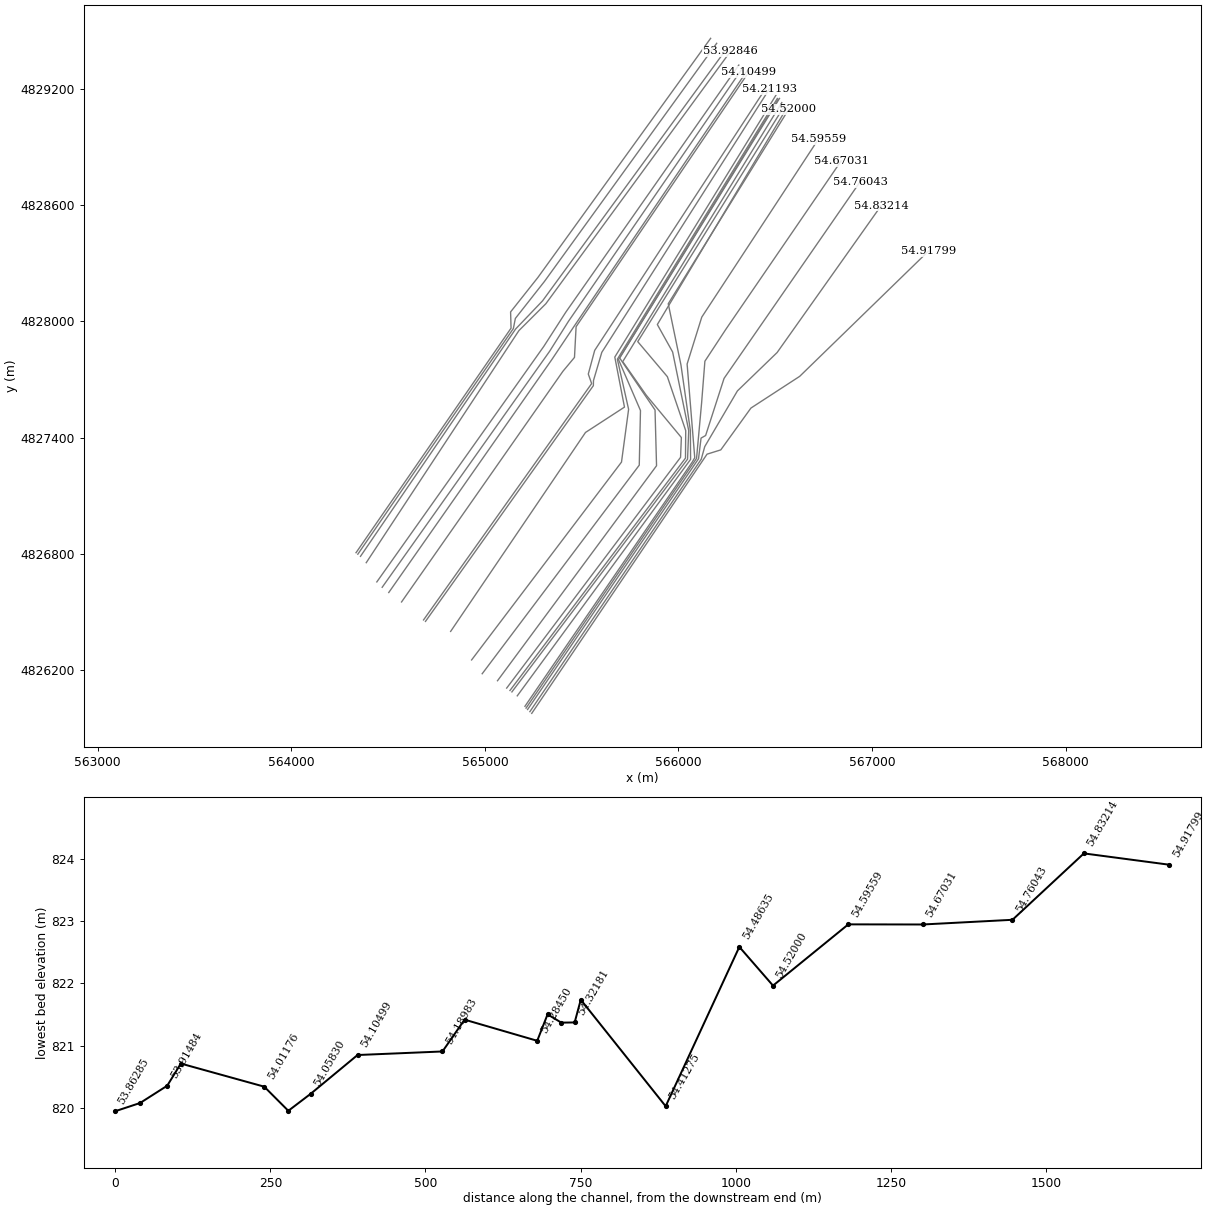
HEC-RAS study Boise2.prj: BoiseRiver_All_reaches

--- Boise2.g01 (geometry) --- (continued)

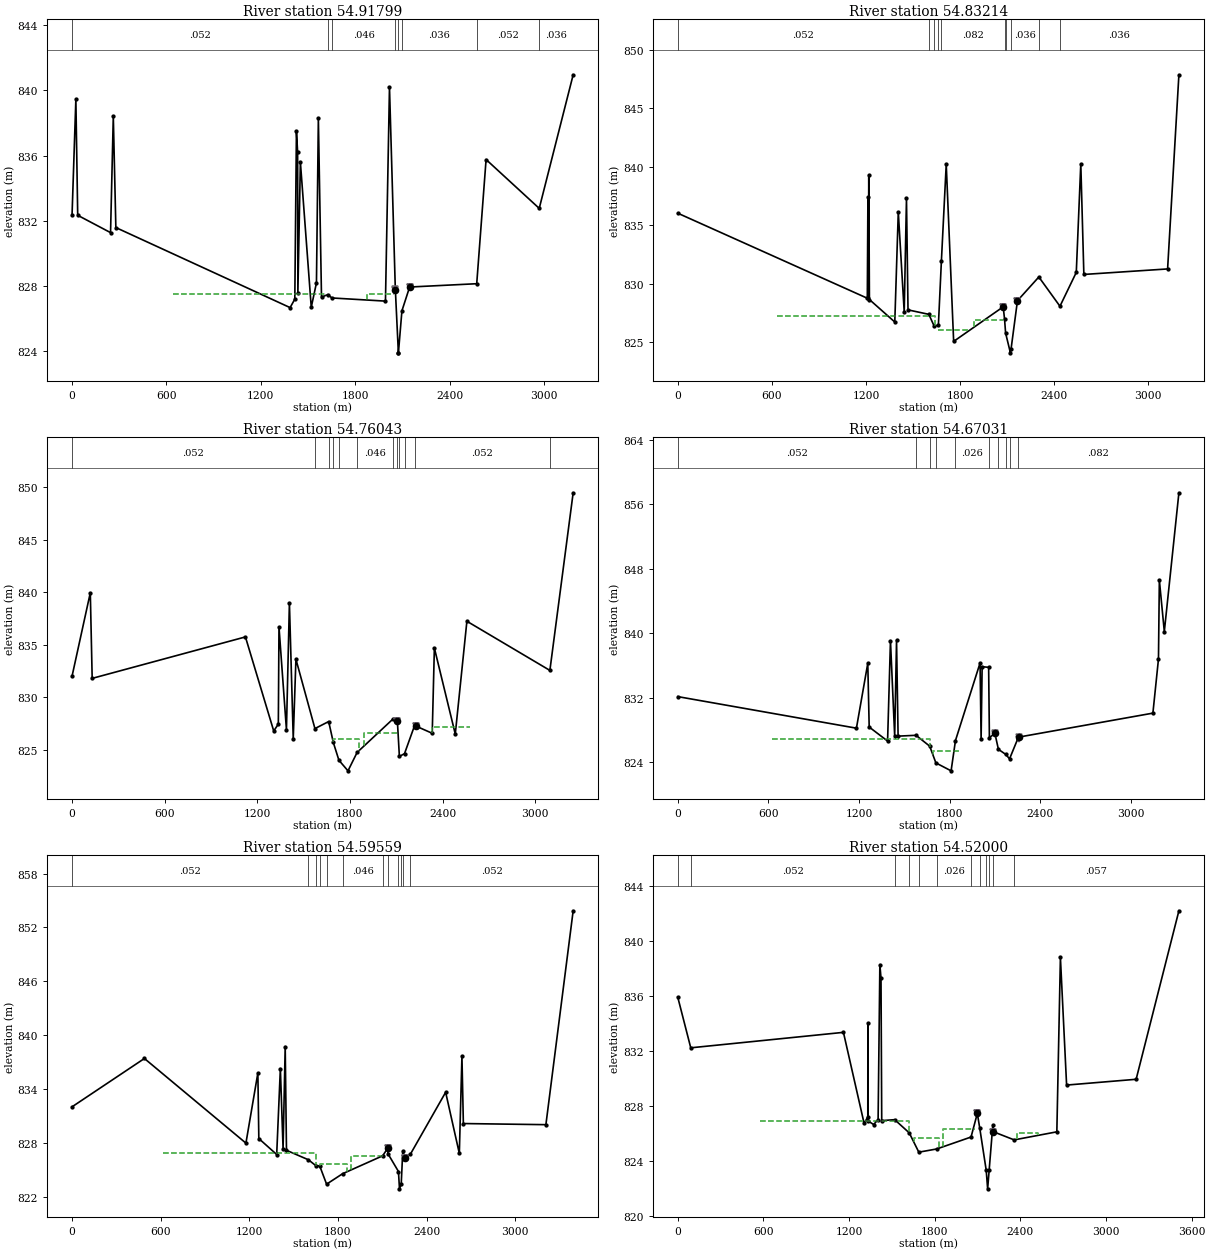
Type RM Length L Ch R = 1 ,54.91799,131.6239,137.7669,149.509
BEGIN DESCRIPTION:
FEMA XS "E"
PROJECT XS "BQ"
END DESCRIPTION:
XS GIS Cut Line= 6
       565242.11      4825975.22       566147.58      4827314.15
        566218.6      4827336.31       566374.24      4827552.23
       566626.04      4827716.03       567291.71      4828363.52
#Sta/Elev= 30
       0832.3262 24.3649839.4509 36.0459832.3356244.8782831.2722262.3675838.4036
278.6032831.58281386.506826.6746  1416.4827.19521426.704837.48921434.276836.2136
1435.912827.57531451.829835.59361520.956 826.6991554.033828.19251566.127838.2786
1586.117827.31741626.692827.47411652.025827.2668 1992.77827.07292018.316840.1934
 2055.38827.8204 2055.69 827.7682074.849823.90192075.283823.91892097.413826.4777
2146.396827.93682572.975828.14012632.515 835.7542970.437832.75843186.178840.9502
#Mann= 8 ,-1 , 0
       0    .052       01626.692    .057       01652.025    .046       0
 2055.38    .082       02075.283    .037       02097.413    .036       0
2572.975    .052       02970.437    .036       0
Levee=-1,2055.69,827.8246,-1,2146.396,827.9465,,
#XS Ineff= 3 ,-1
  640.08 1615.44 827.532 1645.92 1844.04826.6176 1874.52 2049.78 827.532
Permanent Ineff=
       T       T       T
Bank Sta=2055.69,2146.396
XS Rating Curve= 0 ,0
Exp/Cntr=0.3,0.1

Type RM Length L Ch R = 1 ,54.83214,109.5421,115.0809,125.8489
XS GIS Cut Line= 6
       565232.48      4825984.12       566117.81      4827288.46
       566135.71      4827353.11       566304.59      4827641.02
       566509.53      4827839.14       567045.97      4828596.43
#Sta/Elev= 30
       0836.03441208.983 828.7571212.824837.37951214.956828.77621218.321839.2881
1222.419828.64481384.255826.72131406.531836.13981444.313827.59421458.823837.3005
1468.602827.76031601.401827.37841634.899826.38651662.336826.44181681.581 831.951
1712.386 840.2261759.675825.06162075.715828.02082084.306826.97782091.144 825.773
2121.724824.0835 2125.53824.37122166.668828.54612303.043830.57482437.729828.0715
2541.942830.9686 2570.69840.26652590.253830.79193124.395831.26393196.492847.8799
#Mann= 10 ,-1 , 0
       0    .052       01601.401    .046       01634.899    .057       0
1662.336    .046       01681.581    .082       02084.306    .037       0
2091.144    .052       0 2125.53    .036       02303.043    .052       0
2437.729    .036       0
Levee=-1,2075.715,828.038,-1,2166.668,828.547,,
#XS Ineff= 3 ,-1
  632.46  1638.3827.2272 1661.16 1851.66 826.008 1889.76 2072.64826.9224
Permanent Ineff=
       T       T       T
Bank Sta=2075.715,2166.668
XS Rating Curve= 0 ,0
Exp/Cntr=0.3,0.1

Type RM Length L Ch R = 1 ,54.76043,138.1009,144.6209,142.7952
XS GIS Cut Line= 6
       565220.57      4825995.12        566103.6      4827290.23
       566116.69      4827397.16       566140.27      4827410.53
       566235.48      4827705.54       566937.45      4828720.07
#Sta/Elev= 30
       0832.0156 118.358839.9623130.4996831.81451123.212835.75741306.523826.8099
1336.367827.46561340.546836.71011388.899826.93581408.095838.99711432.926826.0909
1450.304833.63321573.433827.03941662.513827.70811692.352825.72361728.817824.0262
1787.569823.01951846.688824.77082076.777827.91882107.567827.73582107.609827.7356
2120.469 824.3922153.648824.65312218.928827.3229 2224.97827.29442333.252826.5905
2347.174834.69932482.559826.51672557.772 837.249 3095.39832.57183246.221849.4673
#Mann= 12 ,-1 , 0
       0    .052       01573.433    .046       01662.513    .057       0
1692.352    .046       01728.817    .026       01846.688    .046       0
2076.777    .036       02107.609    .082       02120.469    .037       0
2153.648    .082       02218.928    .052       0 3095.39    .036       0
Levee=-1,2107.567,827.7301,-1,2224.97,827.2973,,
#XS Ineff= 4 ,-1
  624.841664.208826.9224 2331.72 2575.56827.2272 1691.64 1859.28 826.008
 1889.76 2103.12826.6176
Permanent Ineff=
       T       T       T       T
Bank Sta=2107.567,2224.97
XS Rating Curve= 0 ,0
Exp/Cntr=0.3,0.1

Type RM Length L Ch R = 1 ,54.67031,103.8841,119.9059,136.4949
BEGIN DESCRIPTION:
FEMA XS "D"
PROJECT XS "BP"
END DESCRIPTION:
XS GIS Cut Line= 6
       565212.59      4826002.47       566093.38      4827292.45
       566119.65      4827580.63       566136.48      4827794.26
       566243.73      4827957.57       566840.17      4828828.53
#Sta/Elev= 30
       0832.1537 1182.36 828.2371257.567836.28861266.819828.37851388.615826.6387
1407.664839.09521435.567827.25891447.889839.1367 1458.15827.25041576.902 827.354
1667.474826.00491708.218823.92961808.958822.94421837.939826.70472000.638836.3261
2007.572826.89192014.392835.86832057.453835.78632062.421827.0693 2098.92827.5828
2122.069825.61392170.982 824.9792195.765824.42972249.966826.90992257.349827.1334
3144.515830.10363181.444836.81623187.242846.61223220.114840.22913316.663857.4454
#Mann= 10 ,-1 , 0
       0    .052       01576.902    .046       01667.474    .057       0
1708.218    .046       01837.939    .026       02062.421    .046       0
2122.069    .036       02170.982    .082       02195.765    .037       0
2249.966    .082       0
Levee=-1,2098.92,827.5656,-1,2257.349,826.895,,
#XS Ineff= 4 ,-1
  624.841670.304826.9224 2263.14 2606.04826.92241688.287 1859.28825.3984
 1889.76 2103.12826.9224
Permanent Ineff=
       T       T       T       T
Bank Sta=2098.92,2257.349
XS Rating Curve= 0 ,0
Exp/Cntr=0.3,0.1

Type RM Length L Ch R = 1 ,54.59559,87.869,121.3159,140.1699
BEGIN DESCRIPTION:
FEMA XS "BM"
PROJECT XS "BO"
END DESCRIPTION:
XS GIS Cut Line= 6
       565206.92      4826011.74       566072.07      4827274.69
       566084.06      4827296.01       566044.66      4827779.82
       566120.32        4828022.        566722.4      4828940.78
#Sta/Elev= 30
       0832.0634490.0187837.43711177.388828.02791258.187835.82711264.707828.5354
1385.682826.76361410.537836.3203 1428.82 827.4211443.267838.7676 1451.91827.2302
1600.519826.17661652.947825.49321676.425825.5142  1723.5823.46561831.947824.6279
 2103.12826.61762136.237827.43542139.459826.83462210.068824.87352217.005822.9463
2228.749823.46322239.175 827.1292255.459826.36682291.562826.81672529.569833.6829
2622.205826.88492639.886837.66972649.547830.20543208.307830.07953392.954853.8585
#Mann= 12 ,-1 , 0
       0    .052       01600.519    .046       01652.947    .057       0
1676.425    .046       0  1723.5    .026       01831.947    .046       0
 2103.12    .036       02139.459    .082       02210.068    .037       0
2228.749    .082       02239.175    .057       02291.562    .052       0
Levee=-1,2136.237,827.4558,-1,2255.459,826.3707,,
#XS Ineff= 4 ,-1
  617.22 1653.54826.92242291.486 2644.14826.3128  1676.4 1859.28825.7032
 1889.76 2110.74826.6176
Permanent Ineff=
       T       T       T       T
Bank Sta=2136.237,2255.459
XS Rating Curve= 0 ,0
Exp/Cntr=0.3,0.1

Type RM Length L Ch R = 1 ,54.52000,37.228,54.2721,69.2859
XS GIS Cut Line= 6
       565167.32      4826065.79       566062.54      4827287.12
       566061.44      4827436.03       566012.89      4827774.64
        565947.2      4828091.21       566569.85      4829096.17
#Sta/Elev= 30
       0835.9249 90.9381832.23941160.564833.3655 1305.48826.73131331.336 827.208
1331.697834.05631332.619 826.9131372.098826.6505 1403.53827.01391415.791838.3018
1423.748837.33071428.859826.93521519.596827.00411621.539826.04461688.664824.6358
1814.208824.86962054.581825.73912098.612827.46152115.596826.38682160.903823.3151
2170.855821.96452181.595823.34192207.153826.61062209.748826.12972356.699825.5313
2655.657 826.1182680.674838.82122724.029829.52483211.156829.94673510.812842.2236
#Mann= 12 ,-1 , 0
       0    .046       0 90.9381    .052       01519.596    .046       0
1621.539    .057       01688.664    .046       01814.208    .026       0
2054.581    .046       02115.596    .036       02160.903    .082       0
2181.595    .037       02207.153    .082       02356.699    .057       0
Levee=-1,2098.612,827.4772,-1,2209.748,826.1299,,
#XS Ineff= 4 ,-1
  579.12 1623.06826.9224 2377.44 2522.22 826.008 1653.54  1828.8825.7032
 1859.28 2080.26826.3128
Permanent Ineff=
       T       T       T       T
Bank Sta=2098.612,2209.748
XS Rating Curve= 0 ,0
Exp/Cntr=0.3,0.1

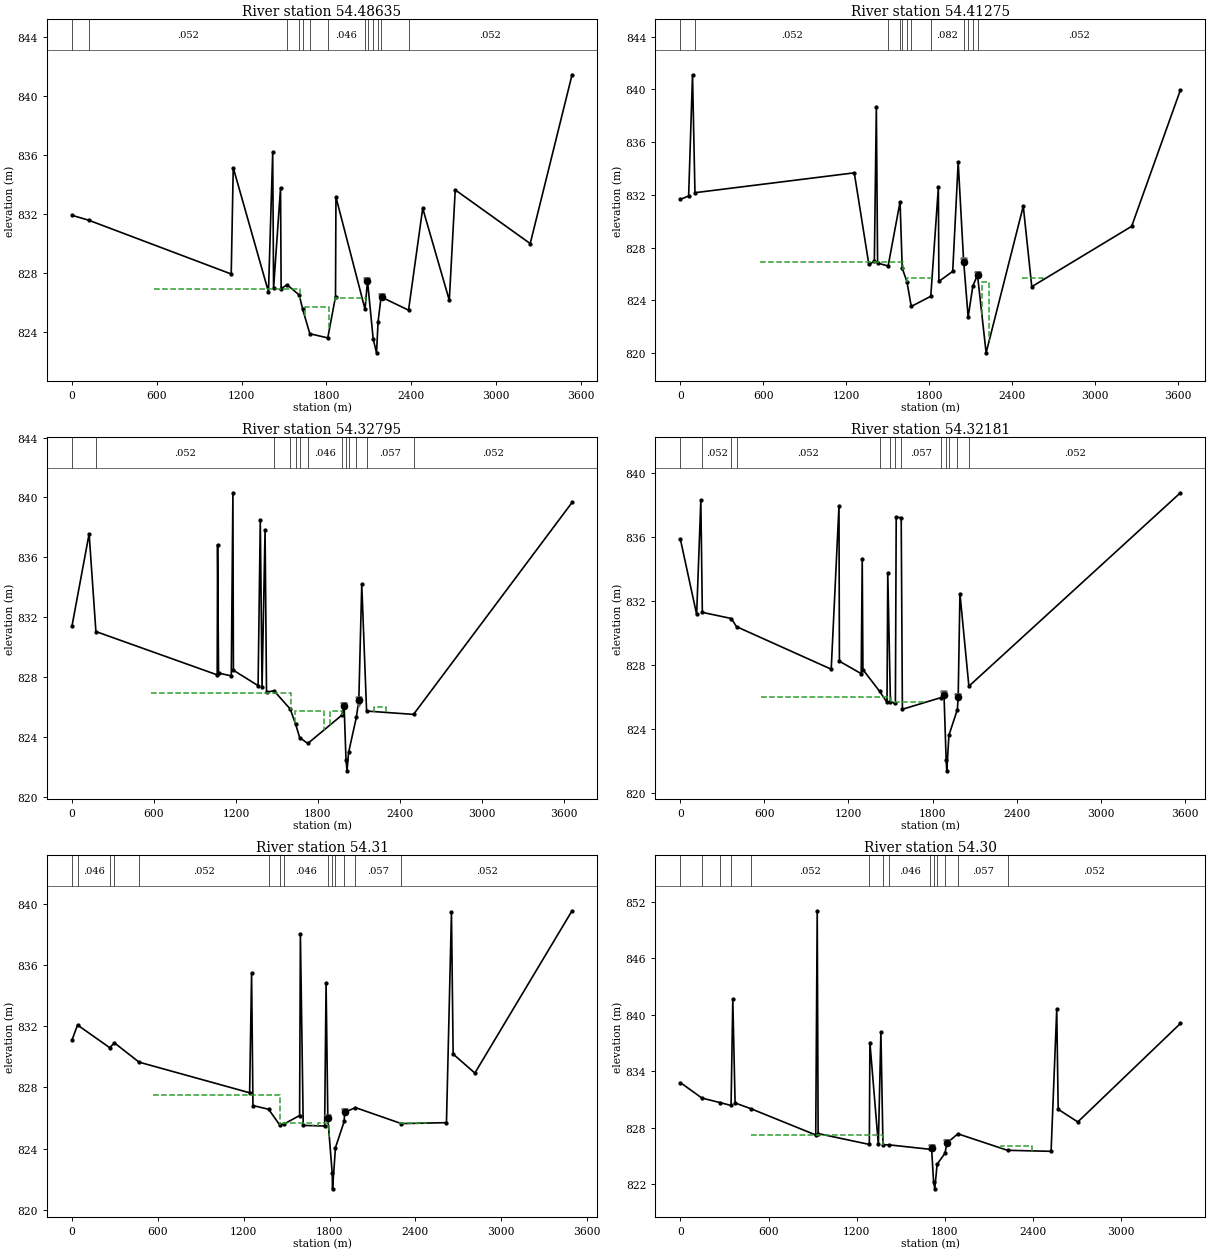
Type RM Length L Ch R = 1 ,54.48635,109.7091,118.7041,129.6351
XS GIS Cut Line= 6
       565139.62       4826086.1       566046.92      4827288.27
       566052.92      4827436.16       565969.82      4827841.88
       565890.85      4827983.75       566560.91      4829104.49
#Sta/Elev= 30
       0831.9071 118.193831.57371126.949827.92741141.294835.13281390.654826.7155
1420.557836.17551426.758826.95961476.029833.77341480.214826.94431522.787827.1934
1608.161826.5076 1632.94825.53251683.243823.87991810.308823.59771865.082826.3963
1868.171833.14122074.078825.53742091.071827.44052091.471827.46742131.725823.5284
2155.326822.58512166.266824.67572187.303826.37072194.459826.34042381.914 825.478
2482.198832.3823 2670.36826.1461 2712.38833.62743243.121829.98993539.115841.4302
#Mann= 13 ,-1 , 0
       0    .046       0 118.193    .052       01522.787    .046       0
1608.161    .057       0 1632.94    .046       01683.243    .026       0
1810.308    .046       02074.078    .036       02091.471    .082       0
2131.725    .037       02166.266    .082       02187.303    .057       0
2381.914    .052       0
Levee=-1,2091.071,827.4711,-1,2194.459,826.3403,,
#XS Ineff= 4 ,-1
  579.12 1615.44826.9224  2400.3 2545.08 826.008 1645.92 1821.18825.7032
 1859.282078.736826.3128
Permanent Ineff=
       T       T       T       T
Bank Sta=2091.071,2194.459
XS Rating Curve= 0 ,0
Exp/Cntr=0.3,0.1

Type RM Length L Ch R = 1 ,54.41275,136.7311,136.7671,132.716
XS GIS Cut Line= 6
        565129.6      4826093.45       566036.23      4827293.67
       566037.42      4827435.79       565942.67      4827714.42
       565789.62      4827895.42       566548.96      4829115.63
#Sta/Elev= 30
       0 831.666 59.9229831.9205  87.995841.1108105.6157832.17161257.282833.6771
  1362.5826.74191402.287826.9583  1416.8838.69811425.849826.83981501.962826.6127
1588.268  831.481603.852826.4573 1637.97825.41611669.252823.54821810.276824.3176
1865.147832.57791868.868825.44591968.828826.20762008.418834.47992047.969826.9581
2048.165826.94232080.445822.74052114.424825.10392148.057825.9216 2148.12825.9214
2210.304820.0312 2478.88831.15092540.333 825.0463262.338 829.6223614.822839.9559
#Mann= 12 ,-1 , 0
       0    .046       0105.6157    .052       01501.962    .046       0
1588.268    .057       01603.852    .046       0 1637.97    .026       0
1669.252    .046       01810.276    .082       02047.969    .037       0
2080.445    .082       02114.424    .057       0 2148.12    .052       0
Levee=-1,2048.165,826.9559,-1,2148.057,825.9227,,
#XS Ineff= 5 ,-1
2179.969 2231.77825.3984  579.12 1607.82826.9224 2468.88 2621.28825.7032
  1638.3 1821.18825.7032 1859.28 2042.16 826.008
Permanent Ineff=
       T       T       T       T       T
Bank Sta=2048.165,2148.057
XS Rating Curve= 0 ,0
Exp/Cntr=0.3,0.1

Type RM Length L Ch R = 1 ,54.32795,10.2949,9.9011,11.056
BEGIN DESCRIPTION:
FEMA XS "C"
PROJECT XS "BN"
END DESCRIPTION:
XS GIS Cut Line= 6
        565112.7      4826105.84       566010.77      4827297.75
       566014.95      4827400.19       565833.32      4827619.01
       565712.04      4827792.13       566533.58      4829129.97
#Sta/Elev= 30
       0831.4078125.4603837.5745175.0762831.0421 1062.97828.14921065.822836.8412
1072.918828.26811166.099828.08091178.048840.31161181.666828.45861362.331 827.428
1378.411  838.461391.393827.32421413.409837.8235 1424.07826.98731478.627827.0909
1597.271 825.8691636.874824.86351666.896823.9606  1726.2 823.5661976.253825.4633
1992.078826.06362005.976822.44892013.346821.7383 2024.91  822.972082.137825.3356
2099.734826.47282121.255834.20342156.606825.73192500.228825.50873660.614839.6639
#Mann= 13 ,-1 , 0
       0    .046       0175.0762    .052       01478.627    .046       0
1597.271    .057       01636.874    .046       01666.896    .026       0
  1726.2    .046       01976.253    .057       02005.976    .037       0
 2024.91    .082       02082.137    .046       02156.606    .057       0
2500.228    .052       0
Levee=-1,1992.078,826.0903,-1,2099.734,826.2153,,
#XS Ineff= 5 ,-1
  579.12  1600.2826.92242211.2872301.841 826.008  2514.6 2659.38825.3984
1635.252 1844.04825.7032 1889.76 1973.58825.7032
Permanent Ineff=
       T       T       T       T       T
Bank Sta=1992.078,2099.734
XS Rating Curve= 0 ,0
Exp/Cntr=0.3,0.1

Type RM Length L Ch R = 1 ,54.32181,25.7739,21.4366,7.8273
BEGIN DESCRIPTION:
FEMA XS "B"
PROJECT XS "BM"
END DESCRIPTION:
XS GIS Cut Line= 5
       565065.25      4826143.82       565886.73      4827254.41
       565878.97      4827542.22       565696.31      4827811.02
        566521.8      4829151.66
#Sta/Elev= 30
       0835.8899 116.354831.1749146.1891 838.325 157.022831.3008363.6499830.9159
400.7642830.40591076.635827.73991132.162 837.9761135.111 828.2411290.722 827.461
1297.966834.66981303.013827.71521422.481826.35091474.812825.65991480.259833.7661
1499.158 825.7121534.704 825.598 1540.47837.27091576.147837.2271 1584.63 825.231
1862.144825.96691881.701826.1221 1896.76822.07611901.468821.37411916.745823.6071
1977.056825.21621982.739826.00321995.263832.48192059.136826.67493568.693 838.791
#Mann= 13 ,-1 , 0
       0    .046       0 157.022    .052       0363.6499    .036       0
400.7642    .052       01422.481    .046       01499.158    .057       0
1534.704    .046       01576.147    .057       01862.144    .037       0
 1896.76    .082       01916.745    .046       01977.056    .057       0
2059.136    .052       0
Levee=-1,1881.701,826.2122,-1,1982.739,826.0172,,
#XS Ineff= 4 ,-1
  579.12 1501.14 826.008 2377.44 2567.94825.7032 1531.62 1737.36825.7032
 1775.46 1859.28825.3984
Permanent Ineff=
       T       T       T       T
Bank Sta=1881.701,1982.739
XS Rating Curve= 0 ,0
Exp/Cntr=0.3,0.1

Type RM Length L Ch R = 1 ,54.31   ,26.35,22.1894,8.5679
XS GIS Cut Line= 5
        564986.2      4826180.01       565797.46      4827257.34
       565803.74      4827539.64       565690.18      4827802.88
       566514.98      4829147.31
#Sta/Elev= 30
       0 831.093 38.8499832.0793263.4202830.5977296.4982830.9116468.7812829.6519
1241.583827.64941255.234 835.4721264.846826.81331374.237826.5731 1450.74825.5621
1480.708825.60231590.822826.16251596.333838.01781616.215825.51641765.813825.4774
1775.898834.8427 1788.11825.98461788.188825.98181818.568 822.4011820.983821.3711
1841.659824.07131902.414825.78091905.006826.36741980.929826.68162302.248 825.634
2617.291825.6968 2652.16839.45612663.916830.18042815.775 828.9393494.956839.5454
#Mann= 14 ,-1 , 0
       0    .052       0 38.8499    .046       0263.4202    .052       0
296.4982    .036       0468.7812    .052       01374.237    .046       0
 1450.74    .057       01480.708    .046       0 1788.11    .057       0
1818.568    .037       01841.659    .082       01902.414    .046       0
1980.929    .057       02302.248    .052       0
Levee=-1,1788.188,825.9866,-1,1905.006,826.3737,,
#XS Ineff= 4 ,-1
  563.881450.848 827.532    2286 2484.12825.7032 1478.28 1684.02825.7032
 1722.12 1798.32825.7032
Permanent Ineff=
       T       T       T       T
Bank Sta=1788.188,1905.006
XS Rating Curve= 0 ,0
Exp/Cntr=0.3,0.1

Type RM Length L Ch R = 1 ,54.30   ,17.2944,16.6634,14.8285
XS GIS Cut Line= 5
       564931.47      4826251.26        565705.7      4827273.18
       565742.44      4827545.81       565684.34      4827804.63
       566510.56      4829151.28
#Sta/Elev= 30
       0832.7895146.7494831.1445 271.567830.6568  345.14830.3608356.8388841.6506
372.5186830.6254481.9266830.0024921.1382827.2247931.2201851.0385937.4511827.3735
1285.842826.22021289.714837.04081347.261826.2131 1364.49838.17321378.664826.1876
1422.743826.17021700.364825.70071709.239825.86891722.768822.25781731.101821.5034
1747.043824.11521800.608825.28861813.459826.36271888.183 827.3472225.971825.5956
2522.427 825.4892560.933840.56412570.669829.95272704.091828.6083 3402.36839.0687
#Mann= 14 ,-1 , 0
       0    .052       0146.7494    .046       0 271.567    .036       0
  345.14    .046       0481.9266    .052       01285.842    .046       0
1378.664    .057       01422.743    .046       01700.364    .057       0
1722.768    .037       01747.043    .082       01800.608    .046       0
1888.183    .057       02225.971    .052       0
Levee=-1,1709.239,825.8831,-1,1813.459,826.3676,,
#XS Ineff= 3 ,-1
  480.06 1379.22827.2272 2179.32 2392.68 826.0081404.518  1600.2825.7032
Permanent Ineff=
       T       T       T
Bank Sta=1709.239,1813.459
XS Rating Curve= 0 ,0
Exp/Cntr=0.3,0.1

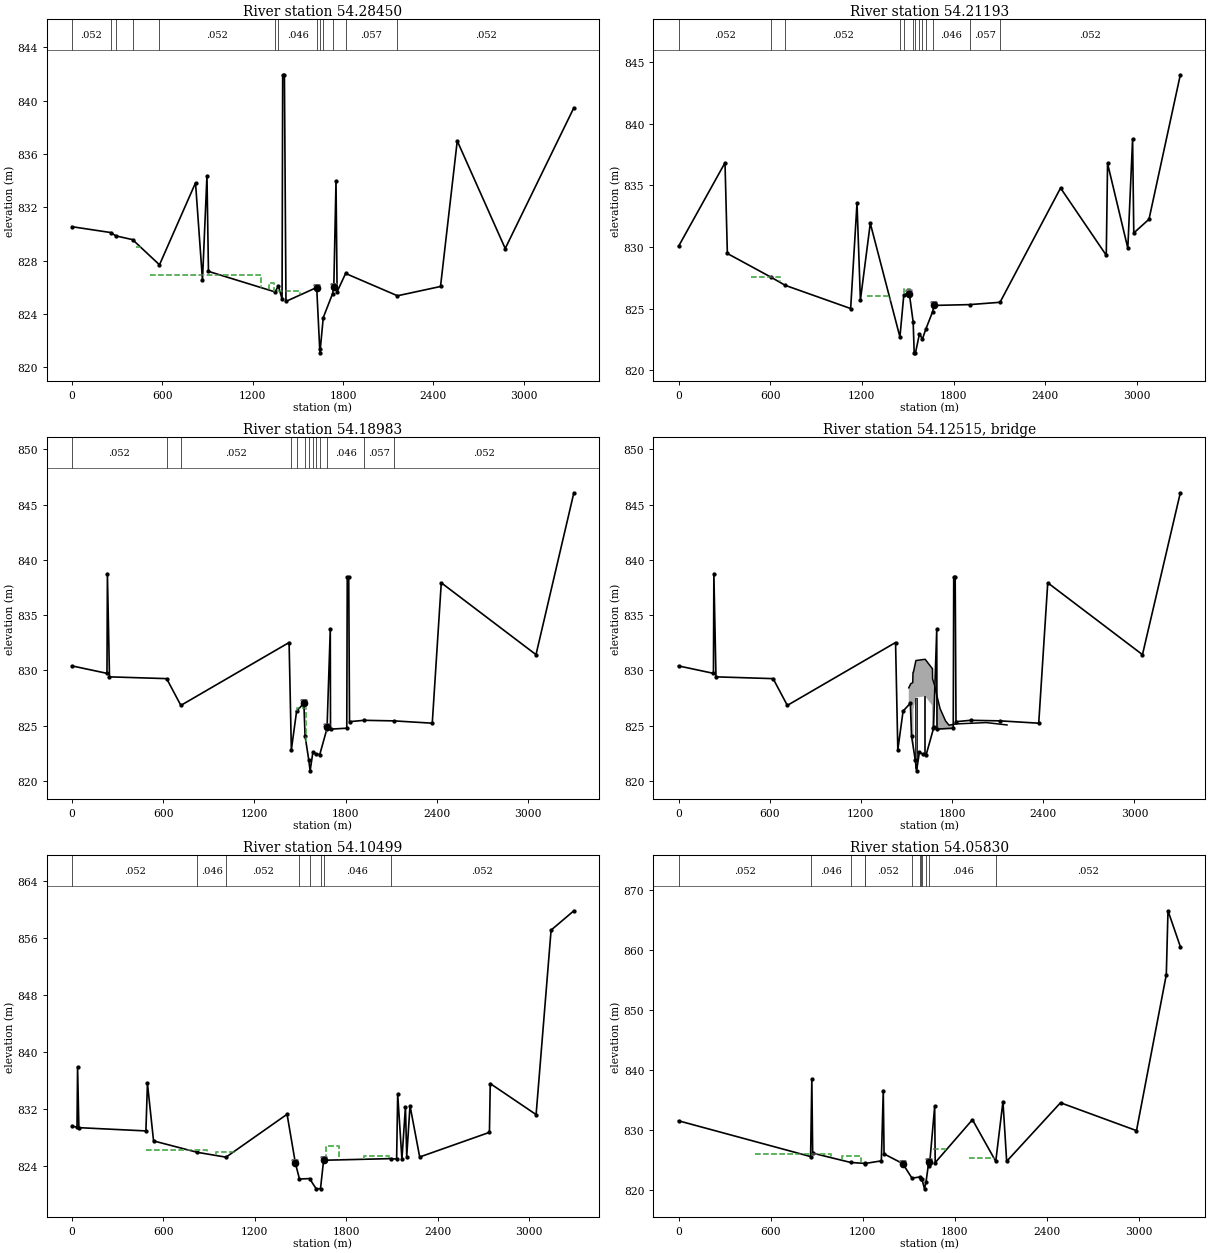
Type RM Length L Ch R = 1 ,54.28450,127.8599,117.0481,79.134
BEGIN DESCRIPTION:
FEMA XS "A"
PROJECT XS "BL"
END DESCRIPTION:
XS GIS Cut Line= 5
       564823.15      4826398.58       565519.73      4827426.27
       565721.09      4827557.23       565671.13      4827815.76
       566503.46       4829168.3
#Sta/Elev= 30
       0830.5458256.6541830.1091 291.319829.8561  401.98829.5769 580.637827.6859
  820.03833.8389 866.266826.5411896.0489834.3809905.9851 827.1941348.032825.6542
1370.959826.09791394.849  825.111399.035  841.95 1410.45841.94291420.833  824.94
1623.789825.97991625.584825.83611644.917821.38291646.497  821.081668.582823.7299
1730.246 825.5131738.625826.02841753.213 833.967 1760.49825.66111816.908827.0379
2161.557 825.363 2447.42826.06012558.576836.98692877.214  828.913333.165839.4741
#Mann= 13 ,-1 , 0
       0    .052       0256.6541    .046       0 291.319    .052       0
  401.98    .046       0 580.637    .052       01348.032    .057       0
1370.959    .046       01625.584    .057       01644.917    .037       0
1668.582    .082       01730.246    .046       01816.908    .057       0
2161.557    .052       0
Levee=-1,1623.789,825.9744,-1,1738.625,826.0324,,
#XS Ineff= 4 ,-1
  426.72   457.2 829.056  518.16  1257.3826.9224 1310.64 1341.12826.3128
 1363.98 1516.38825.7032
Permanent Ineff=
       T       T       T       T
Bank Sta=1623.789,1738.625
XS Rating Curve= 0 ,0
Exp/Cntr=0.3,0.1

Type RM Length L Ch R = 1 ,54.21193,34.7649,35.6381,40.849
XS GIS Cut Line= 5
       564693.24      4826450.31       565560.43      4827668.08
       565560.97      4827694.39       565603.95       4827840.1
        566468.9      4829199.25
#Sta/Elev= 30
       0830.0491304.0919836.8198 319.612829.4699  604.96827.5509698.2331826.8901
 1126.48825.00891168.078 833.5541190.371825.68921255.036831.91691449.014822.7021
1474.631826.14611510.439826.22191535.718 823.9151542.342821.41891550.826821.4202
1577.099822.96611596.148822.53391619.138823.36211663.147824.7532 1671.31825.2617
1904.868825.32712104.222825.51512500.409834.77712799.553829.32512807.993 836.765
2940.608829.90312971.882838.75112979.597831.13293079.163 832.2433284.257843.9522
#Mann= 13 ,-1 , 0
       0    .052       0  604.96    .046       0698.2331    .052       0
1449.014    .082       01474.631    .046       01535.718    .057       0
1550.826    .037       01577.099    .082       01596.148    .037       0
1619.138    .082       01663.147    .046       01904.868    .057       0
2104.222    .052       0
Levee=-1,1510.439,826.2488,-1,1671.31,825.3192,,
#XS Ineff= 4 ,-1
  472.44  662.94 827.532  731.52 1203.96 826.008 1234.44 1386.84 826.008
1475.0281513.131826.6176
Permanent Ineff=
       T       T       T       T
Bank Sta=1510.439,1671.31
XS Rating Curve= 0 ,0
Exp/Cntr=0.5,0.3

Type RM Length L Ch R = 1 ,54.18983,112.808,136.8281,121.941
BEGIN DESCRIPTION:
West Parkcenter Upstream
END DESCRIPTION:
XS GIS Cut Line= 5
       564683.16      4826457.87       565551.51      4827678.77
       565534.22      4827728.04       565567.24      4827850.16
       566455.57      4829211.19
#Sta/Elev= 30
       0830.4059229.7409829.7339232.5161 838.766246.3071829.4169622.4681829.2551
 715.921826.83181428.195 832.5251443.069 822.8111477.742 826.3211525.555 827.025
1533.219 824.0781557.986821.86791566.539 820.9091584.734822.58121606.529  822.44
1629.974822.37991677.856824.74491678.098824.83731699.222833.70511700.802 824.684
 1807.81824.7681 1810.99838.43161820.592838.43161825.924825.3591 1921.56825.4828
2118.702 825.4312370.387825.22192429.713837.93083053.057831.42713302.215846.0791
#Mann= 13 ,-1 , 0
       0    .052       0622.4681    .046       0 715.921    .052       0
1443.069    .082       01477.742    .046       01533.219    .057       0
1557.986    .037       01584.734    .082       01606.529    .037       0
1629.974    .082       01677.856    .046       0 1921.56    .057       0
2118.702    .052       0
Levee=-1,1525.555,827.0443,-1,1678.098,824.737,,
#XS Ineff= 4 ,-1
  472.44  678.18 827.532  746.76 1196.34 826.008 1226.82  1371.6825.7032
 1478.28 1539.24826.6176
Permanent Ineff=
       T       T       T       T
Bank Sta=1525.555,1678.098
XS Rating Curve= 0 ,0
Exp/Cntr=0.5,0.3

Type RM Length L Ch R = 3 ,54.12515,,,
BEGIN DESCRIPTION:
West Parkcenter Bridge
END DESCRIPTION:
Bridge Culvert--1,0,-1,-1, 0
Deck Dist Width WeirC Skew NumUp NumDn MinLoCord MaxHiCord MaxSubmerge Is_Ogee
54.864,30.48,1.44,0, 20, 20, , , 0.95, 0, 0,0,,
1515.1611527.4171541.4011542.9251545.9731545.9731562.1271623.0871667.8931667.893
1670.9411671.8551686.2631696.5291721.5531757.4861779.9441823.3412024.5092161.669
 828.425828.7787828.9036 829.818829.8546829.8546 830.894831.0098 830.202 830.202
830.1746829.2389828.5988827.9161826.5292825.4197825.0418825.1545825.2765825.0631
  807.72  807.72  807.72822.5028822.5028826.5018827.5411827.6569826.8492822.8076
822.8076  807.72  807.72  807.72  807.72  807.72  807.72  807.72  807.72  807.72
1515.1611527.4171541.4011542.9251545.9731545.9731562.1271623.0871667.8931667.893
1670.9411671.8551686.2631696.5291721.5531757.4861779.9441823.3412024.5092161.669
 828.425828.7787828.9036 829.818829.8546829.8546 830.894831.0098 830.202 830.202
830.1746829.2389828.5988827.9161826.5292825.4197825.0418825.1545825.2765825.0631
  807.72  807.72  807.72822.5028822.5028826.5018827.5411827.6569826.8492822.8076
822.8076  807.72  807.72  807.72  807.72  807.72  807.72  807.72  807.72  807.72
Pier Skew, UpSta & Num, DnSta & Num=  ,1563.956, 4 ,1563.956, 4 , 0 , 0 , 0 ,,
  9.4488  9.4488   1.524   1.524
820.7288822.5576822.5576828.1416
  9.4488  9.4488   1.524   1.524
820.7288822.5576822.5576828.1416
Pier Skew, UpSta & Num, DnSta & Num=  ,1620.344, 4 ,1620.344, 4 , 0 , 0 , 0 ,,
  9.4488  9.4488   1.524   1.524
820.5764822.4053822.4053828.1416
  9.4488  9.4488   1.524   1.524
820.5764822.4053822.4053828.1416
BR Coef=-1 , 0 , 0 ,1.25, 0 ,,,0.8,-1,2,0,
WSPro=,,,, 1 ,,,, 0 ,,,, 0 ,,,,-1 ,-1 ,-1 , 0 , 0 , 0 , 0 , 0
BC Design=,, 0 ,, 0 ,,,,,,
BC Use User HTab Curves=0
BC User HTab FreeFlow(D)= 0

Type RM Length L Ch R = 1 ,54.10499,90.1449,75.3121,38.4981
BEGIN DESCRIPTION:
West Parkcenter Downstream
END DESCRIPTION:
XS GIS Cut Line= 5
        564569.6      4826550.73       565403.44      4827742.69
       565462.85      4827813.86       565471.23      4827972.61
       566363.15      4829287.85
#Sta/Elev= 30
       0829.6199 32.4249829.5032  36.167837.9589 44.7331829.4251484.9051828.9679
495.0351835.6171535.1779827.5679821.5662 825.9721011.057 825.2891412.015831.3021
1466.725824.44671493.517822.22521559.427  822.291603.553 820.8521631.598820.8831
 1652.03824.8659 1652.08824.85752094.286825.08692131.509 825.0252138.479834.1181
2166.323825.00012189.396 832.3462197.823825.38292219.436832.50792282.988 825.314
2741.096828.76792746.345835.60313047.573831.25913145.951 857.1083295.492859.8171
#Mann= 8 ,-1 , 0
       0    .052       0821.5662    .046       01011.057    .052       0
1493.517    .082       01559.427    .037       01631.598    .082       0
 1652.03    .046       02094.286    .052       0
Levee=-1,1466.725,824.4444,-1,1652.08,824.8741,,
#XS Ineff= 5 ,-1
  487.68  883.92826.3128  944.88 1074.42 826.008  1104.9 1249.68825.3984
 1668.78  1752.6826.9224 1920.24 2080.26825.3984
Permanent Ineff=
       T       T       T       T       T
Bank Sta=1466.725,1652.08
XS Rating Curve= 0 ,0
Exp/Cntr=0.5,0.3

Type RM Length L Ch R = 1 ,54.05830,34.625,36.234,37.213
XS GIS Cut Line= 4
       564503.56       4826599.5       565344.56      4827800.85
       565461.97      4827976.26        566354.5      4829294.77
#Sta/Elev= 30
       0 831.563860.5939 825.606 868.577 838.496874.0421826.17811121.846824.6239
1212.745824.47091213.726824.44981321.489824.88911334.103 836.5871339.219826.0491
1460.559824.43851521.081822.01781573.069822.20411579.282821.86211585.821821.8582
1602.737820.2321 1612.96 821.426 1630.72824.72271634.867 824.0141669.064 833.963
1672.396824.59411915.115 831.7482067.126 824.8082113.994 834.767 2138.12 824.808
2488.933834.56712984.111829.92593178.384855.89213189.348866.53613269.736 860.572
#Mann= 12 ,-1 , 0
       0    .052       0860.5939    .046       01121.846    .052       0
1212.745    .046       01213.726    .052       01521.081    .082       0
1573.069    .037       01579.282    .057       01585.821    .037       0
 1612.96    .082       01634.867    .046       02067.126    .052       0
Levee=-1,1460.559,824.4291,-1,1630.72,824.737,,
#XS Ineff= 4 ,-1
   495.3   990.6 826.008  1066.8 1188.72825.7032 1661.16 1737.36826.9224
 1889.76  2057.4825.3984
Permanent Ineff=
       T       T       T       T
Bank Sta=1460.559,1630.72
XS Rating Curve= 0 ,0
Exp/Cntr=0.5,0.3

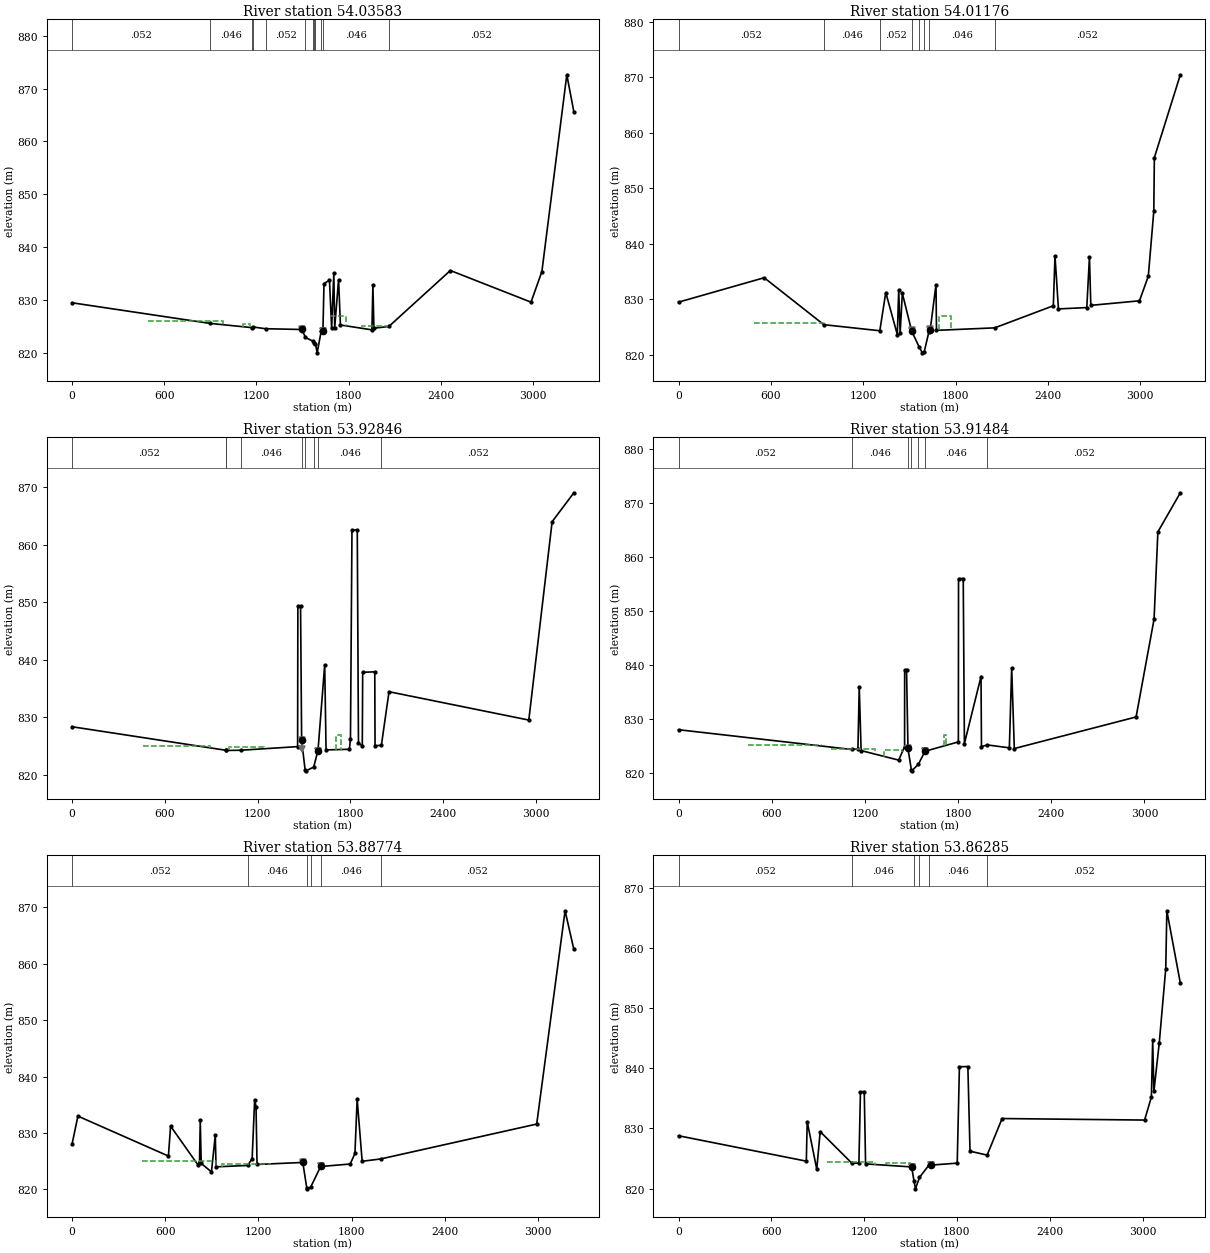
Type RM Length L Ch R = 1 ,54.03583,38.7239,38.8199,37.6651
XS GIS Cut Line= 4
       564469.59      4826626.53       565334.48      4827845.65
       565431.62      4828000.09       566332.52      4829310.19
#Sta/Elev= 30
       0829.4401896.8381825.54021168.666824.74011181.081824.84461260.473824.5261
1496.678824.3793 1519.56822.87011571.181822.12911575.755 821.8921584.903821.6982
1595.813 819.9581621.822824.01491633.091824.03561633.257824.03591640.347  833.08
1675.964833.71611690.093824.6239 1704.23835.07311709.982824.74491735.285833.8401
1747.164 825.2361952.421 824.313 1958.67832.75511965.272  824.632062.563824.9488
2463.024835.5541 2988.16 829.5623058.955835.34893221.257872.63213267.166865.6259
#Mann= 12 ,-1 , 0
       0    .052       0896.8381    .046       01168.666    .052       0
1181.081    .046       01260.473    .052       0 1519.56    .082       0
1571.181    .037       01575.755    .057       01584.903    .037       0
1621.822    .082       01633.257    .046       02062.563    .052       0
Levee=-1,1496.678,824.3773,-1,1633.091,824.0634,,
#XS Ineff= 4 ,-1
   495.3  982.98 826.008 1112.52 1158.24825.3984 1889.76 2049.78825.0936
  1676.4 1783.08826.9224
Permanent Ineff=
       T       T       T       F
Bank Sta=1496.678,1633.091
XS Rating Curve= 0 ,0
Exp/Cntr=0.3,0.1

Type RM Length L Ch R = 1 ,54.01176,140.618,134.3531,120.2119
XS GIS Cut Line= 4
       564441.88      4826654.24       565304.69      4827871.31
        565417.9      4828047.42       566311.69       4829323.9
#Sta/Elev= 30
       0 829.476 556.392833.8749943.6331825.41791307.396 824.3241346.219831.2051
1421.135823.63511430.254831.69591439.434823.85611453.824831.07011514.271824.2872
1514.375824.25691563.594821.37291583.884820.34481595.212 820.4291625.525824.0512
1635.032824.53921672.467832.62791675.635824.39812053.501824.84492434.597 828.825
2445.404837.79892467.735828.25982651.988828.49792669.163 837.6012678.104   828.9
2994.119829.71683051.466 834.1413087.155845.84113090.843855.51293259.525870.4368
#Mann= 8 ,-1 , 0
       0    .052       0943.6331    .046       01307.396    .052       0
1514.375    .082       01563.594    .037       01595.212    .082       0
1625.525    .046       02053.501    .052       0
Levee=-1,1514.271,824.4078,-1,1635.032,824.551,,
#XS Ineff= 3 ,-1
  487.68   952.5825.7032 1691.64 1767.84826.9224 1158.24  1409.7824.1792
Permanent Ineff=
       T       F       T
Bank Sta=1514.271,1635.032
XS Rating Curve= 0 ,0
Exp/Cntr=0.3,0.1

Type RM Length L Ch R = 1 ,53.92846,19.4139,21.9691,21.671
BEGIN DESCRIPTION:
FEMA XS "BK"
PROJECT XS "BK"
END DESCRIPTION:
XS GIS Cut Line= 6
       564387.23      4826753.64       564992.29      4827673.39
       565175.92      4827952.52        565314.9      4828091.12
       565450.39       4828276.3       566268.26      4829394.12
#Sta/Elev= 30
       0828.3839994.2061 824.296998.7501 824.2561091.582 824.2991458.934 824.929
1460.608849.4105 1477.96849.32821484.967826.03191484.979825.9921  1507.7820.8209
1512.805820.71511563.205 821.3681589.206824.14061590.145824.02011634.179839.1558
1642.922824.35381793.769 824.463 1800.79826.21891810.573862.60531844.814862.6053
1852.592825.51791877.271825.07011879.854837.8556 1958.07 837.933 1959.81825.0991
2000.746 825.139 2050.18834.47692954.402829.5449 3105.29864.04713245.858869.0759
#Mann= 9 ,-1 , 0
       0    .052       0994.2061    .046       0998.7501    .052       0
1091.582    .046       01484.979    .082       0  1507.7    .037       0
1563.205    .082       01590.145    .046       02000.746    .052       0
Levee=-1,1484.967,824.4901,-1,1589.206,824.1548,,
#XS Ineff= 4 ,-1
   457.2  891.54825.0936 1013.46 1242.06824.7888 1706.88 1737.36826.9224
 1310.64 1440.18824.1792
Permanent Ineff=
       T       T       F       T
Bank Sta=1484.967,1589.206
XS Rating Curve= 0 ,0
Exp/Cntr=0.3,0.1

Type RM Length L Ch R = 1 ,53.91484,41.322,43.7141,50.6599
XS GIS Cut Line= 4
       564357.44      4826786.32       565158.76      4827960.57
       565297.83      4828105.93       566246.17      4829404.83
#Sta/Elev= 30
       0  827.981115.352824.31881155.088824.43011163.561835.92491175.689824.1109
1417.848822.3461 1455.58  824.84 1455.99839.05351468.024839.10831477.385824.5129
1477.423824.50741499.199 820.5241502.462  820.361544.433 821.5821587.083 823.985
1587.173823.98521801.793825.72211802.928 855.9651833.169     8561840.766 825.417
1947.653 837.8341950.687824.8531  1988.7825.16092130.161 824.6222145.112839.4119
2162.022 824.4912946.216 830.3453061.966848.47613086.545 864.6493231.032 871.892
#Mann= 7 ,-1 , 0
       0    .052       01115.352    .046       01477.385    .082       0
1499.199    .037       01544.433    .082       01587.083    .046       0
  1988.7    .052       0
Levee=-1,1477.423,824.4657,-1,1587.173,823.9902,,
#XS Ineff= 4 ,-1
  449.58   914.4825.0936  982.98 1264.92 824.484 1706.88 1722.12826.9224
 1325.88 1440.18824.1792
Permanent Ineff=
       T       T       F       T
Bank Sta=1477.423,1587.173
XS Rating Curve= 0 ,0
Exp/Cntr=0.3,0.1

Type RM Length L Ch R = 1 ,53.88774,40.2659,40.1409,39.82
XS GIS Cut Line= 5
       564343.77      4826797.51       565147.11       4827962.9
       565157.45      4828015.23       565307.83      4828206.49
        566197.4      4829436.41
#Sta/Elev= 30
       0828.0231  37.655832.9839620.1711825.8962 634.183831.2079808.7889824.3889
820.3228 824.815825.1811 832.211831.3209824.5989897.1529823.0789921.8389829.5891
 926.728 823.9861129.854824.2332 1159.15825.41791175.262 835.8991184.109 834.664
1190.667824.40811485.205824.76451510.994820.18821512.864 820.0831535.865  820.39
1600.407824.04721600.464 824.0461790.186824.48491820.848826.35311835.033836.0131
1867.295824.97111986.449 825.3842990.796831.57313173.499869.40693229.999 862.541
#Mann= 6 ,-1 , 0
       0    .052       01129.854    .046       01510.994    .037       0
1535.865    .082       01600.464    .046       01986.449    .052       0
Levee=-1,1485.205,824.7278,-1,1600.407,824.0482,,
#XS Ineff= 3 ,-1
  449.58  929.64825.0936  967.74 1280.16 824.484 1341.12 1463.04824.1792
Permanent Ineff=
       T       T       T
Bank Sta=1485.205,1600.407
XS Rating Curve= 0 ,0
Exp/Cntr=0.3,0.1

Type RM Length L Ch R = 1 ,53.86285,31.509,62.473,120.0309
XS GIS Cut Line= 5
       564334.46      4826805.13       565135.24      4827965.05
       565132.85      4828048.86       565274.02      4828227.07
       566166.11      4829462.08
#Sta/Elev= 30
       0828.7881826.1909824.5571 831.808831.1368893.6989 823.213915.7521829.4751
1120.869824.21181166.079 824.2281176.211836.12731200.659836.12731209.301 824.103
1507.172823.59951521.852821.32511531.786 819.9511557.862 821.863  1620.8823.9548
1630.717823.90131801.758 824.2281815.959840.27261870.561840.30921884.546 826.218
 1995.18825.5652 2091.94831.65413012.991831.39993057.202835.22823065.514 844.806
3073.204836.18593107.649844.15093149.965856.61393157.018866.23883244.194 854.202
#Mann= 6 ,-1 , 0
       0    .052       01120.869    .046       01521.852    .037       0
1557.862    .082       0  1620.8    .046       0 1995.18    .052       0
Levee=-1,1507.172,823.6122,-1,1630.717,823.908,,
#XS Ineff= 3 ,-1
  449.58  929.64825.0936  960.12 1272.54 824.484 1341.12 1493.52824.1792
Permanent Ineff=
       T       T       T
Bank Sta=1507.172,1630.717
XS Rating Curve= 0 ,0
Exp/Cntr=0.5,0.3