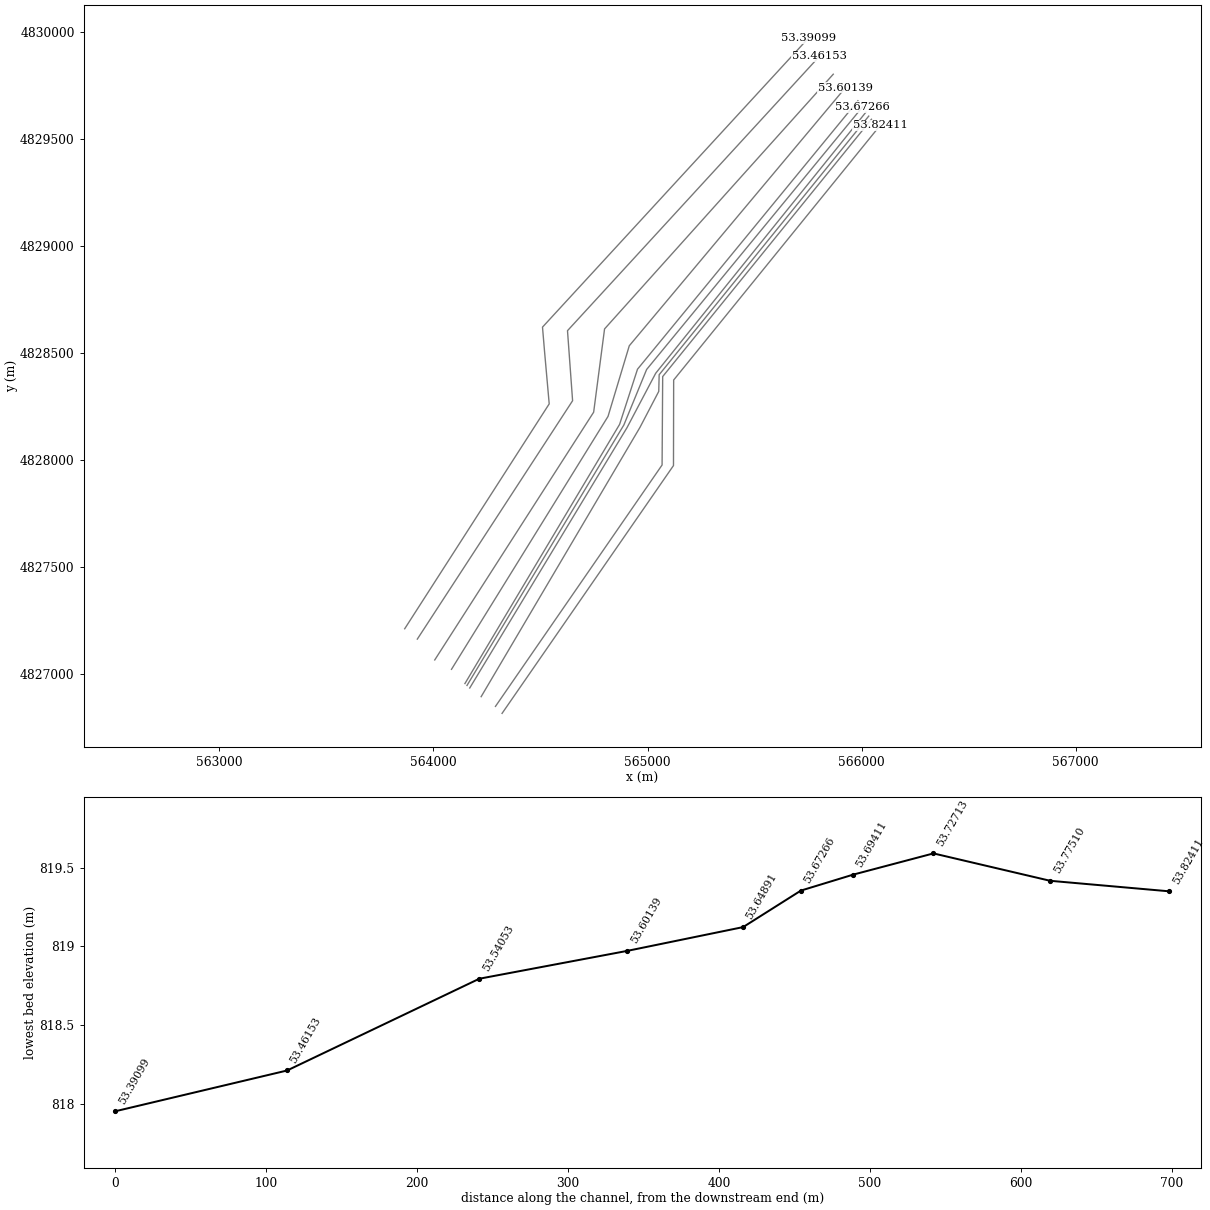
HEC-RAS study Boise2.prj: BoiseRiver_All_reaches

--- Boise2.g01 (geometry) --- (continued)

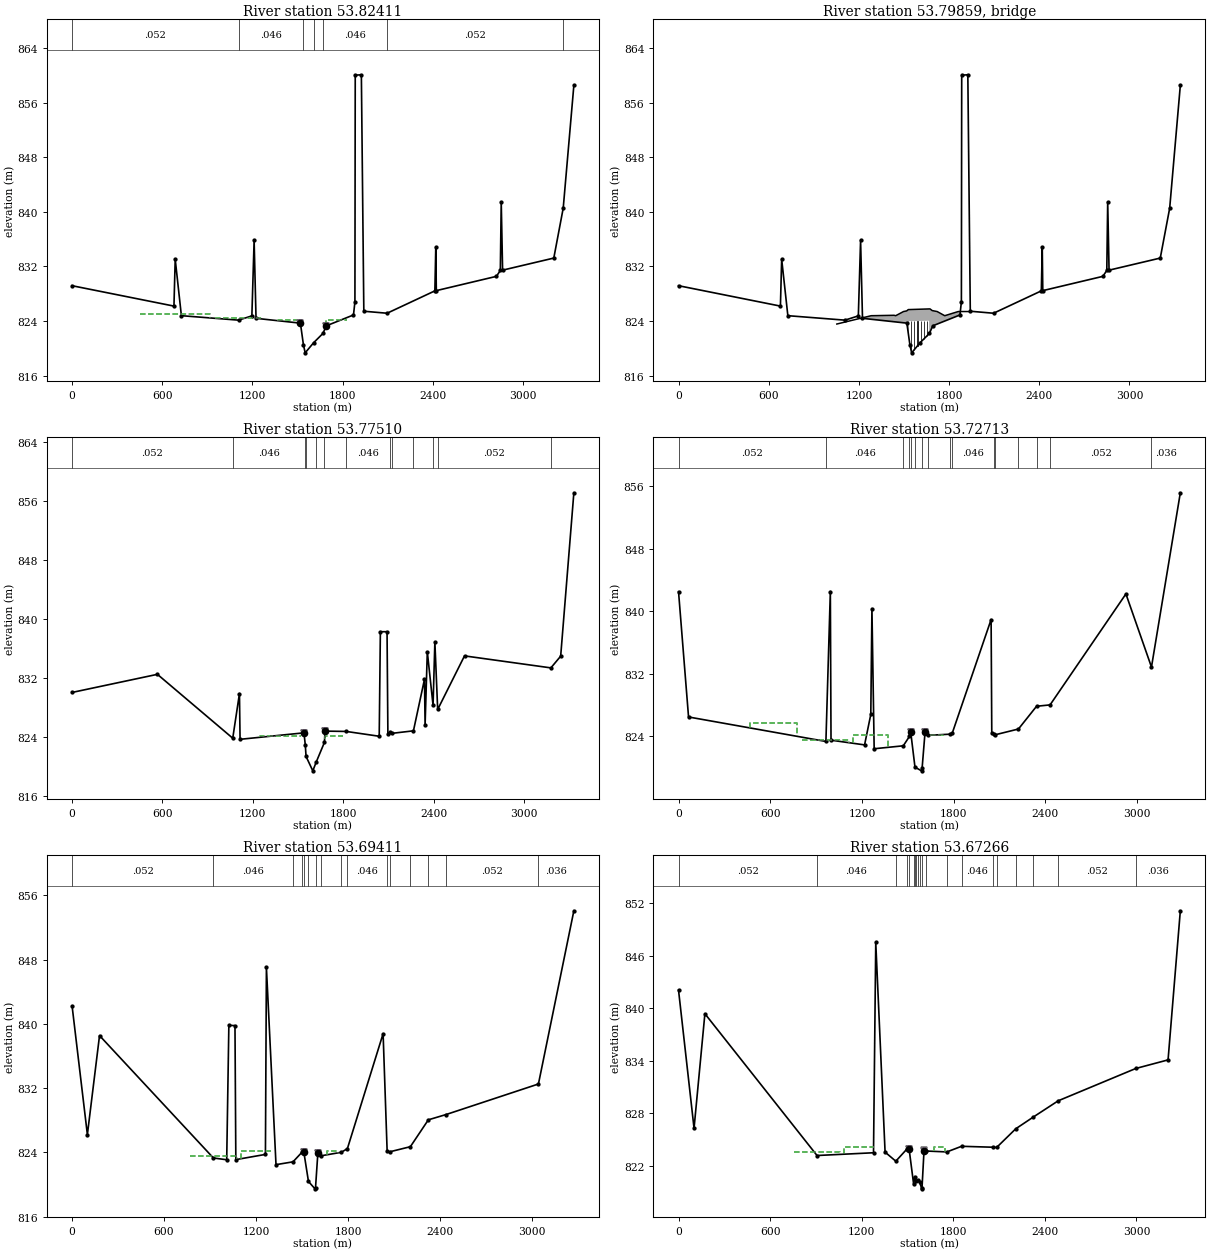
Type RM Length L Ch R = 1 ,53.82411,76.7529,79.0471,67.9061
BEGIN DESCRIPTION:
Broadway Avenue Bridge Upstream and FEMA XS "BJ"
PROJECT XS "BJ"
END DESCRIPTION:
XS GIS Cut Line= 4
       564320.41      4826816.62       565121.09      4827974.17
       565121.87      4828373.66       566086.48      4829563.02
#Sta/Elev= 30
       0829.1819677.8069826.1951686.1788833.0562 727.257824.79191107.324824.1371
1196.196824.76291211.163835.83291223.856824.40421519.056823.69861538.971 820.564
 1550.74819.34911607.225 820.8351668.832822.18881691.631823.30871872.286824.8979
1881.767826.82921883.911860.02371924.629860.0786 1941.02825.44382095.804  825.15
2413.628 828.4262419.733834.84422423.293828.46112822.933830.55192849.166 831.413
 2855.16841.45712864.202 831.4593204.874833.23113267.557840.54613338.331858.5329
#Mann= 7 ,-1 , 0
       0    .052       01107.324    .046       01538.971    .037       0
1607.225    .082       01668.832    .046       02095.804    .052       0
3267.557    .036       0
Levee=-1,1519.056,823.6884,-1,1691.631,823.3074,,
#XS Ineff= 4 ,-1
  449.58   914.4825.0936   952.5 1264.92 824.484 1691.64  1828.8824.1792
  1371.6 1508.76824.1792
Permanent Ineff=
       T       T       T       T
Bank Sta=1519.056,1691.631
XS Rating Curve= 0 ,0
Exp/Cntr=0.5,0.3

Type RM Length L Ch R = 3 ,53.79859,,,
BEGIN DESCRIPTION:
Broadway Avenue Bridge
END DESCRIPTION:
Bridge Culvert--1,0,-1,-1, 0
Deck Dist Width WeirC Skew NumUp NumDn MinLoCord MaxHiCord MaxSubmerge Is_Ogee
21.336,20.7264,1.44,0, 17, 17, , , 0.95, 0, 0,0,,
1053.0841281.6841434.0841444.7521496.5681517.9041528.5721533.1441533.1441667.256
1667.2561673.3521687.4641720.5961770.8881860.804 1927.86
823.5696824.7888824.8497824.7888825.3984825.4929825.6879825.6879825.6879825.7825
825.7825825.7825825.5416825.3984824.7888825.3984825.3984
 813.816 813.816 813.816 813.816 813.816 813.816819.3024819.3024823.9811824.0543
819.3024819.3024 813.816 813.816 813.816 813.816 813.816
1063.7521292.3521444.752 1455.421507.2361528.572 1539.241543.8121543.8121677.924
1677.924 1684.021698.1321731.2641781.5561871.4721938.528
823.5696824.7888824.8497824.7888825.3984825.4929825.6879825.6879825.6879825.7825
825.7825825.7825825.5416825.3984824.7888825.3984825.3984
 813.816 813.816 813.816 813.816 813.816 813.816819.3024819.3024823.9811824.0543
819.3024819.3024 813.816 813.816 813.816 813.816 813.816
Pier Skew, UpSta & Num, DnSta & Num=  ,1546.86, 4 ,1557.528, 4 , 3 , 3 , 0 ,,
    .762    .762   .9144   .9144
 818.388823.1124823.1124 824.484
    .762    .762   .9144   .9144
 818.388823.1124823.1124 824.484
Pier Skew, UpSta & Num, DnSta & Num=  ,1568.196, 4 ,1578.864, 4 , 3 , 3 , 0 ,,
    .762    .762   .9144   .9144
 818.388823.1124823.1124 824.484
    .762    .762   .9144   .9144
 818.388823.1124823.1124 824.484
Pier Skew, UpSta & Num, DnSta & Num=  ,1589.532, 4 ,1600.2, 4 , 3 , 3 , 0 ,,
    .762    .762   .9144   .9144
 818.388823.1124823.1124 824.484
    .762    .762   .9144   .9144
 818.388823.1124823.1124 824.484
Pier Skew, UpSta & Num, DnSta & Num=  ,1610.868, 4 ,1621.536, 4 , 3 , 3 , 0 ,,
    .762    .762   .9144   .9144
 818.388823.1124823.1124 824.484
    .762    .762   .9144   .9144
 818.388823.1124823.1124 824.484
Pier Skew, UpSta & Num, DnSta & Num=  ,1632.204, 4 ,1642.872, 4 , 3 , 3 , 0 ,,
    .762    .762   .9144   .9144
 818.388823.1124823.1124 824.484
    .762    .762   .9144   .9144
 818.388823.1124823.1124 824.484
Pier Skew, UpSta & Num, DnSta & Num=  ,1653.54, 4 ,1664.208, 4 , 3 , 3 , 0 ,,
    .762    .762   .9144   .9144
 818.388823.1124823.1124 824.484
    .762    .762   .9144   .9144
 818.388823.1124823.1124 824.484
BR Coef=-1 , 0 , 0 ,1.25, 0 ,,,0.8,-1,2,0,
WSPro=,,,, 1 ,,,, 0 ,,,, 0 ,,,,-1 ,-1 ,-1 , 0 , 0 , 0 , 0 , 0
BC Design=,, 0 ,, 0 ,,,,,,
BC Use User HTab Curves=0
BC User HTab FreeFlow(D)= 0

Type RM Length L Ch R = 1 ,53.77510,101.823,77.364,39.7441
BEGIN DESCRIPTION:
Broadway Avenue Bridge Downstream
END DESCRIPTION:
XS GIS Cut Line= 4
       564289.58      4826849.26       565067.83      4827976.83
       565070.62      4828389.85       566045.77       4829591.7
#Sta/Elev= 30
       0830.0508 566.447832.50791066.518 823.8431111.076829.90211115.123823.6931
1539.216824.57091548.149 822.9281553.146821.36621597.992819.4161 1620.76 820.613
1675.385 823.2871678.683824.80461819.608 824.7612038.774824.1069 2046.43838.2884
2090.751838.28842096.373 824.4272109.387824.64592121.377 824.4982265.934 824.843
2339.335831.84092343.273825.60692358.002835.57422396.167828.30622408.203836.9141
2426.811827.73722604.884835.00993178.235833.38293243.258  834.973330.787 857.136
#Mann= 13 ,-1 , 0
       0    .052       01066.518    .046       01548.149    .082       0
1553.146    .037       0 1620.76    .082       01675.385    .057       0
1819.608    .046       02109.387    .052       02121.377    .036       0
2265.934    .052       02396.167    .036       02426.811    .052       0
3178.235    .036       0
Levee=-1,1539.216,824.5693,-1,1678.683,824.8497,,
#XS Ineff= 4 ,-1
  449.58  868.68825.7032  906.78  1219.2823.8744  1676.4 1798.32824.1792
 1249.68 1516.38824.1792
Permanent Ineff=
       T       T       F       F
Bank Sta=1539.216,1678.683
XS Rating Curve= 0 ,0
Exp/Cntr=0.5,0.3

Type RM Length L Ch R = 1 ,53.72713,53.1849,53.2641,52.785
XS GIS Cut Line= 5
       564222.71       4826894.6       564964.73      4828152.85
       565052.26      4828320.58       565054.18      4828398.48
       566033.08      4829606.41
#Sta/Elev= 30
       0842.5142 65.4771826.4819964.1129823.3489993.1024842.5342997.5031823.5129
1217.021  822.911257.771826.81211265.213840.34611279.799822.41721470.297822.7939
1510.345823.98991518.349824.58311518.551 824.5981546.782820.06021589.613819.5901
1593.396819.9111 1612.49824.50431632.787 824.1321773.613 824.2781790.354824.3941
2044.833838.95282049.192824.41082064.455824.26792072.333 824.2092223.663824.9415
2342.167827.8538 2430.47828.02792926.711 842.2273093.891832.87093282.644  855.17
#Mann= 16 ,-1 , 0
       0    .052       0964.1129    .046       01470.297    .036       0
1510.345    .046       01518.551    .082       01546.782    .037       0
1593.396    .082       01632.787    .057       01773.613    .046       0
1790.354    .046       02064.455    .052       02072.333    .036       0
2223.663    .052       02342.167    .036       0 2430.47    .052       0
3093.891    .036       0
Levee=-1,1518.349,824.5938,-1,1612.49,824.5115,,
#XS Ineff= 4 ,-1
  464.82  777.24825.7032  807.72 1112.52823.5696 1645.92  1752.6824.1792
    1143  1371.6824.1792
Permanent Ineff=
       T       T       F       F
Bank Sta=1518.349,1612.49
XS Rating Curve= 0 ,0
Exp/Cntr=0.5,0.3

Type RM Length L Ch R = 1 ,53.69411,28.376,34.5921,38.2911
XS GIS Cut Line= 4
       564169.46      4826935.26       564903.84      4828150.94
       565038.02      4828405.32       566020.21      4829625.07
#Sta/Elev= 30
       0842.2429    99.9 826.211179.1319 838.538921.9359 823.2981008.972823.0749
1022.973839.81541062.871839.77891068.447823.09321261.578823.74091267.941847.0309
1330.564822.46591441.508822.81791500.438824.02191511.967824.00681512.225 824.032
1542.345820.3741 1585.02819.45511588.507819.61511603.608823.90671624.193823.5681
1756.787 824.0061796.401824.46512029.358838.77912055.696 824.1462071.411  824.06
2207.278824.70312324.485 828.0492438.417 828.6963042.783  832.513273.921854.0779
#Mann= 16 ,-1 , 0
       0    .052       0921.9359    .046       01441.508    .036       0
1500.438    .046       01512.225    .082       01542.345    .037       0
1588.507    .082       01624.193    .057       01756.787    .046       0
1796.401    .046       02055.696    .052       02071.411    .036       0
2207.278    .052       02324.485    .036       02438.417    .052       0
3042.783    .036       0
Levee=-1,1511.967,823.9963,-1,1603.608,823.8988,,
#XS Ineff= 4 ,-1
  472.44  731.52825.3984  769.62 1074.42823.5696 1661.16 1737.36824.1792
  1104.9  1295.4824.1792
Permanent Ineff=
       T       T       F       F
Bank Sta=1511.967,1603.608
XS Rating Curve= 0 ,0
Exp/Cntr=0.3,0.1

Type RM Length L Ch R = 1 ,53.67266,27.8441,38.3079,35.917
XS GIS Cut Line= 4
       564156.56      4826946.98       564889.35       4828163.8
       564995.57      4828422.84       566003.74      4829648.95
#Sta/Elev= 30
       0 842.077 101.631 826.282172.7091 839.386907.4249823.16611277.508823.4809
1292.179 847.5431353.304823.55411423.605 822.5151496.594 823.9111510.165823.9503
1510.398823.9509 1540.65819.85411547.554820.75691558.075820.26011567.938820.3088
1579.117820.12511594.128819.35391595.227 819.4421608.414823.7196 1620.21823.6821
1757.971 823.5761854.303  824.222060.446 824.1142084.118824.08592209.382826.2219
2325.441 827.5782487.857829.42692995.817833.12083207.416834.10413287.771851.1601
#Mann= 20 ,-1 , 0
       0    .052       0907.4249    .046       01423.605    .036       0
1496.594    .046       01510.398    .082       0 1540.65    .037       0
1547.554    .082       01558.075    .037       01567.938    .082       0
1579.117    .037       01595.227    .082       0 1620.21    .057       0
1757.971    .046       01854.303    .046       02060.446    .052       0
2084.118    .036       02209.382    .052       02325.441    .036       0
2487.857    .052       02995.817    .036       0
Levee=-1,1510.165,823.9628,-1,1608.414,823.7525,,
#XS Ineff= 4 ,-1
  472.44  716.28825.3984  754.38 1059.18823.5696  1676.4 1744.98824.1792
 1082.04 1280.16824.1792
Permanent Ineff=
       T       T       F       F
Bank Sta=1510.165,1608.414
XS Rating Curve= 0 ,0
Exp/Cntr=0.3,0.1

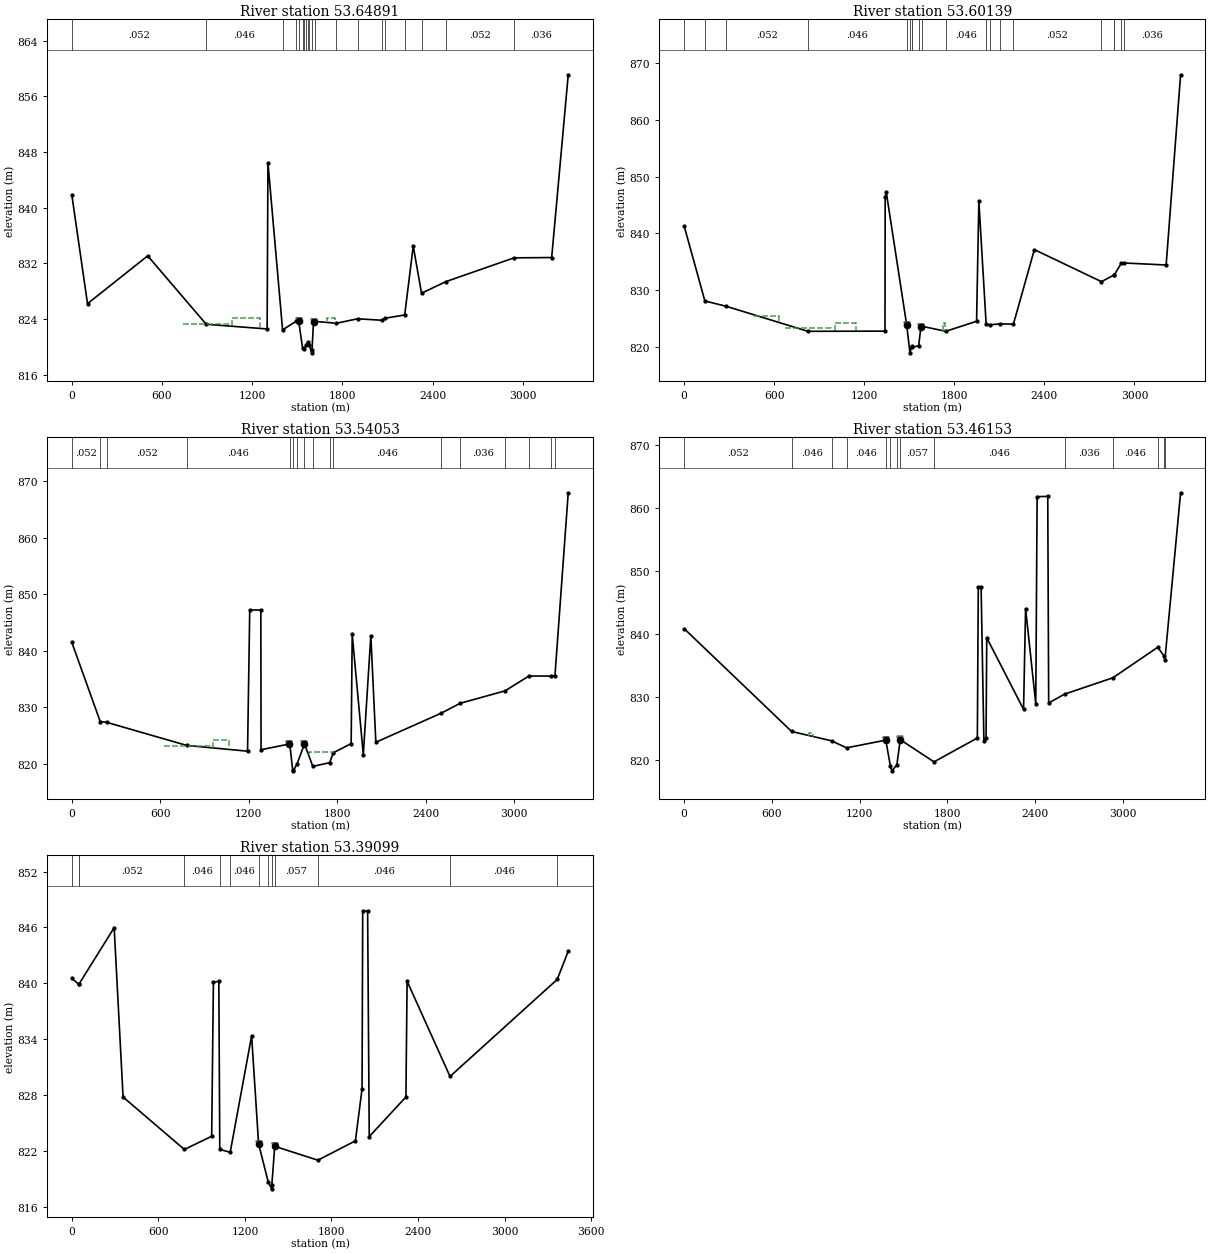
Type RM Length L Ch R = 1 ,53.64891,67.0651,76.641,67.1999
BEGIN DESCRIPTION:
FEMA XS "BI"
PROJECT XS "BI"
END DESCRIPTION:
XS GIS Cut Line= 6
       564146.96      4826955.93       564567.19      4827660.15
       564869.48      4828166.73       564952.99      4828424.17
       565383.66       4828948.7       565982.48      4829678.03
#Sta/Elev= 30
       0 841.846104.5031826.1851504.9101 833.059 894.449 823.2271299.735822.5549
1304.963846.45891402.449822.42111493.942823.68081508.805 823.7391508.964823.7349
 1535.89  819.78 1547.12 819.684 1558.68820.2089 1569.58820.6539 1579.82820.2311
1596.198819.12191597.986 819.4671608.405 823.6041618.134823.64311760.493823.3739
1901.531 824.0172060.735823.80712084.186 824.0932214.984 824.5692271.702 834.457
2326.956827.68992488.472829.35192941.972832.77183192.935832.8182 3302.99859.0831
#Mann= 20 ,-1 , 0
       0    .052       0 894.449    .046       01402.449    .036       0
1493.942    .046       01508.805    .082       0 1535.89    .037       0
 1547.12    .082       0 1558.68    .037       0 1569.58    .082       0
 1579.82    .037       01597.986    .082       01618.134    .057       0
1760.493    .046       01901.531    .046       02060.735    .052       0
2084.186    .036       02214.984    .052       02326.956    .036       0
2488.472    .052       02941.972    .036       0
Levee=-1,1508.964,823.7372,-1,1608.405,823.6153,,
#XS Ineff= 4 ,-1
  472.44  708.66825.3984  739.14 1051.56823.2648 1699.26  1752.6824.1792
  1066.8 1249.68824.1792
Permanent Ineff=
       T       T       F       F
Bank Sta=1508.964,1608.405
XS Rating Curve= 0 ,0
Exp/Cntr=0.3,0.1

Type RM Length L Ch R = 1 ,53.60139,87.869,98.152,101.2661
XS GIS Cut Line= 4
       564084.19      4827022.42       564815.34      4828203.75
       564914.57      4828533.61       565924.72      4829739.89
#Sta/Elev= 30
       0841.2891137.9101828.1069 279.782827.1669824.1341822.76011337.809822.7939
1339.128846.39611346.355 847.2471482.912823.78991482.913823.78971504.077818.9711
1516.314820.17411520.282 819.9521562.283820.21591577.255 823.5931585.432823.6431
1742.521822.7631 1947.94824.52611963.151845.6661 2011.72824.02682037.516823.9061
2104.981 824.0742193.281824.01792332.908837.14292779.964831.50292860.657 832.631
2864.295832.6469 2912.91834.78592929.445834.79513210.778834.43213307.117867.9241
#Mann= 20 ,-1 , 0
       0    .052       0137.9101    .036       0 279.782    .052       0
824.1341    .046       01482.912    .082       01504.077    .037       0
1516.314    .082       01520.282    .037       01562.283    .082       0
1585.432    .057       01742.521    .046       0 2011.72    .046       0
2037.516    .052       02104.981    .036       02193.281    .052       0
2779.964    .036       02860.657    .046       02864.295    .036       0
 2912.91    .046       02929.445    .036       0
Levee=-1,1482.913,823.7982,-1,1577.255,823.5818,,
#XS Ineff= 4 ,-1
  464.82  632.46825.3984  670.56  975.36823.2648 1722.12 1737.36824.1792
 1005.84    1143824.1792
Permanent Ineff=
       T       T       F       F
Bank Sta=1482.913,1577.255
XS Rating Curve= 0 ,0
Exp/Cntr=0.3,0.1

Type RM Length L Ch R = 1 ,53.54053,117.2611,127.4158,133.4911
XS GIS Cut Line= 4
       564005.96      4827066.22       564748.19      4828223.46
       564799.13      4828612.33        565867.4      4829802.13
#Sta/Elev= 30
       0841.5229192.5361827.5201 238.314 827.358 779.569 823.2871191.699822.2712
 1206.49847.23731281.769847.23731283.247 822.5251475.226 823.544 1478.69823.3879
 1497.54818.97291501.904 818.7941527.161 820.0081577.651823.55411577.745823.5533
  1634.2819.57891748.981820.2412 1772.88821.9871 1894.18823.60891901.281842.9335
1976.525821.66612027.596842.71012061.549823.84912505.998 829.0072633.233830.7379
2938.194832.94493099.426835.56293247.531835.55493276.143835.64093366.016867.9741
#Mann= 17 ,-1 , 0
       0    .052       0192.5361    .036       0 238.314    .052       0
 779.569    .046       0 1478.69    .082       0 1497.54    .037       0
1527.161    .082       01577.651    .057       0  1634.2    .026       0
1748.981    .057       0 1772.88    .046       02505.998    .052       0
2633.233    .036       02938.194    .046       03099.426    .036       0
3247.531    .026       03276.143    .036       0
Levee=-1,1475.226,823.5543,-1,1577.745,823.5543,,
#XS Ineff= 3 ,-1
  624.84  937.26823.2648  960.12  1066.8824.1792 1606.291772.068822.0456
Permanent Ineff=
       T       T       T
Bank Sta=1475.226,1577.745
XS Rating Curve= 0 ,0
Exp/Cntr=0.3,0.1

Type RM Length L Ch R = 1 ,53.46153,111.2331,113.7821,112.594
BEGIN DESCRIPTION:
FEMA XS "BH"
PROJECT XS "BH"
END DESCRIPTION:
XS GIS Cut Line= 6
       563924.56      4827163.54       564355.82      4827825.61
       564649.83      4828276.99       564626.02      4828604.13
       565190.24      4829218.56       565802.58      4829885.39
#Sta/Elev= 30
       0840.8259 735.312824.46811008.039 822.9851110.949821.87181379.261823.0901
1379.638823.04991411.187  818.941421.252818.2109 1455.34 819.1641478.095823.1709
1478.588823.16931709.048819.63592005.824 823.433 2012.21847.40192031.434847.4537
 2050.71822.97892065.399823.48912070.125839.37592321.994827.99012335.813844.0278
2405.476 828.8922414.845 861.8192487.467861.86772493.848829.0012 2602.63830.4139
2933.435 833.0123240.125837.87083283.601836.45013288.694835.80063396.359 862.438
#Mann= 14 ,-1 , 0
       0    .052       0 735.312    .046       01008.039    .036       0
1110.949    .046       01379.261    .082       01411.187    .037       0
 1455.34    .082       01478.095    .057       01709.048    .046       0
 2602.63    .036       02933.435    .046       03240.125    .036       0
3283.601    .026       03288.694    .036       0
Levee=-1,1379.638,823.0728,-1,1478.588,823.1978,,
#XS Ineff= 2 ,-1
  502.92  822.96823.2648  853.44  883.92824.1792
Permanent Ineff=
       T       F
Bank Sta=1379.638,1478.588
XS Rating Curve= 0 ,0
Exp/Cntr=0.3,0.1

Type RM Length L Ch R = 1 ,53.39099,101.731,104.54,104.9289
XS GIS Cut Line= 5
       563865.63      4827211.88       564540.58      4828262.23
       564518.46      4828511.25       564509.28      4828620.79
       565750.35      4829969.66
#Sta/Elev= 30
       0840.5439 46.4591839.9261 52.3089839.9849293.7339845.9761355.4572827.8039
780.1649 822.176969.6249 823.593981.6937840.13551019.178840.2117 1025.88822.1871
 1098.15 821.8711246.519834.36871295.059822.75231295.342822.75311362.105818.6589
1385.627817.95211386.883818.39291406.843822.51891407.088822.51381705.901821.0269
1966.152823.09992012.038828.67112016.813 847.789 2050.67847.74942062.027 823.559
 2316.15827.80822324.481 840.226    2622830.01183365.343 840.4263441.396843.4471
#Mann= 13 ,-1 , 0
       0    .052       0 46.4591    .036       0 52.3089    .052       0
780.1649    .046       0 1025.88    .036       0 1098.15    .046       0
1295.342    .082       01362.105    .037       01386.883    .082       0
1406.843    .057       01705.901    .046       0    2622    .046       0
3365.343    .036       0
Levee=-1,1295.059,822.7497,-1,1407.088,822.5059,,
#XS Ineff= 1 ,-1
  480.06  899.16822.6552
Permanent Ineff=
       T
Bank Sta=1295.059,1407.088
XS Rating Curve= 0 ,0
Exp/Cntr=0.3,0.1