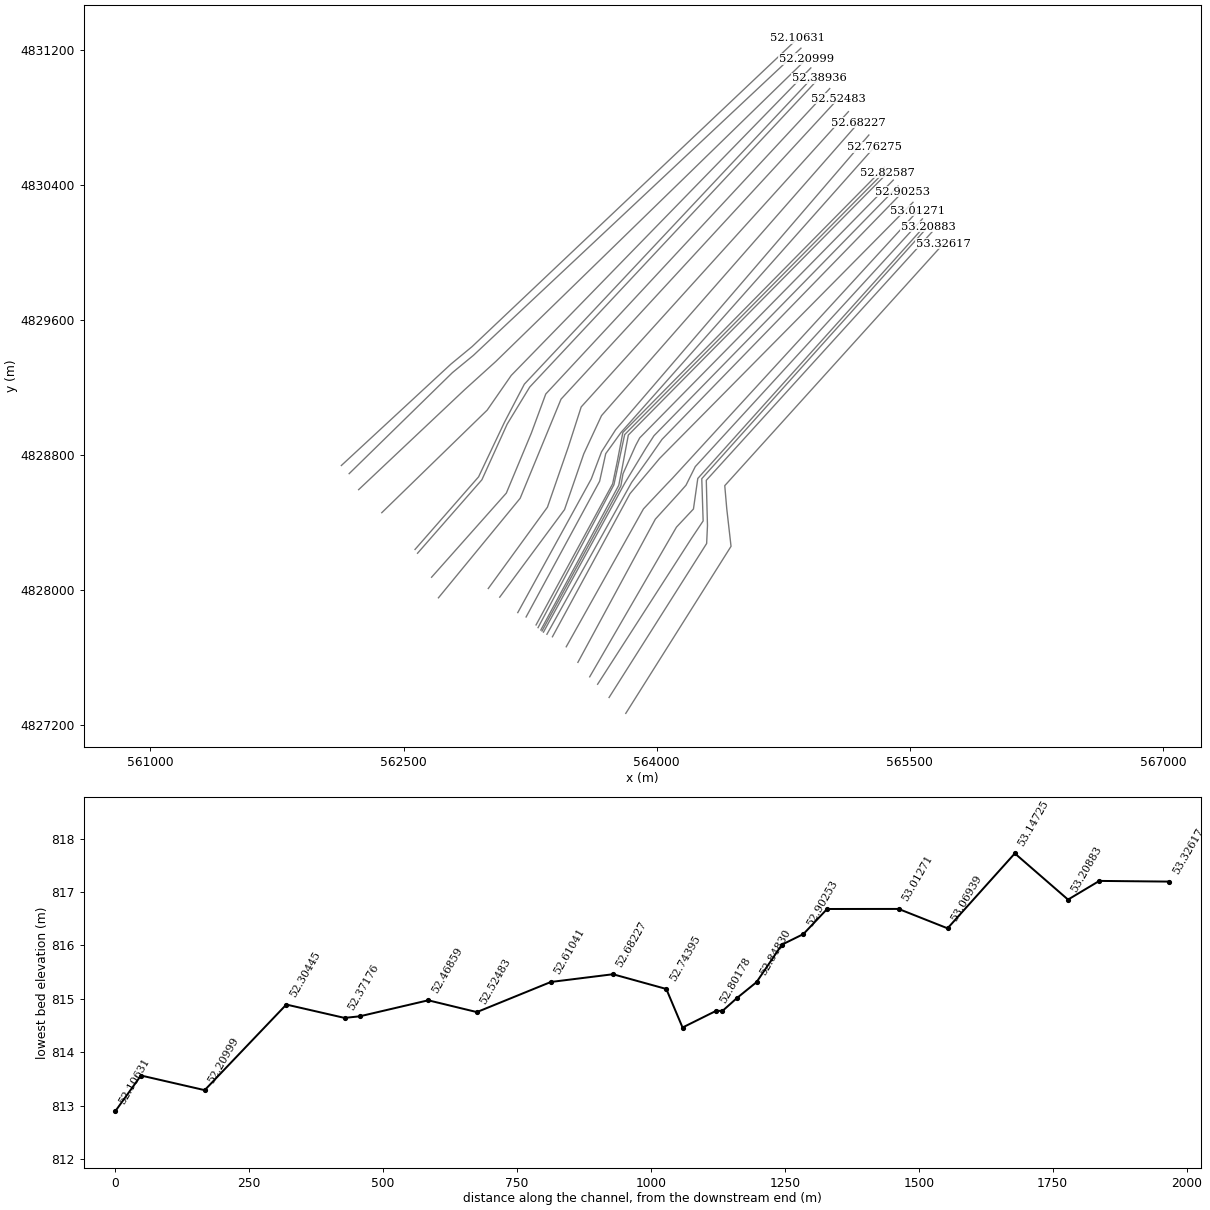
HEC-RAS study Boise2.prj: BoiseRiver_All_reaches

--- Boise2.g01 (geometry) --- (continued)

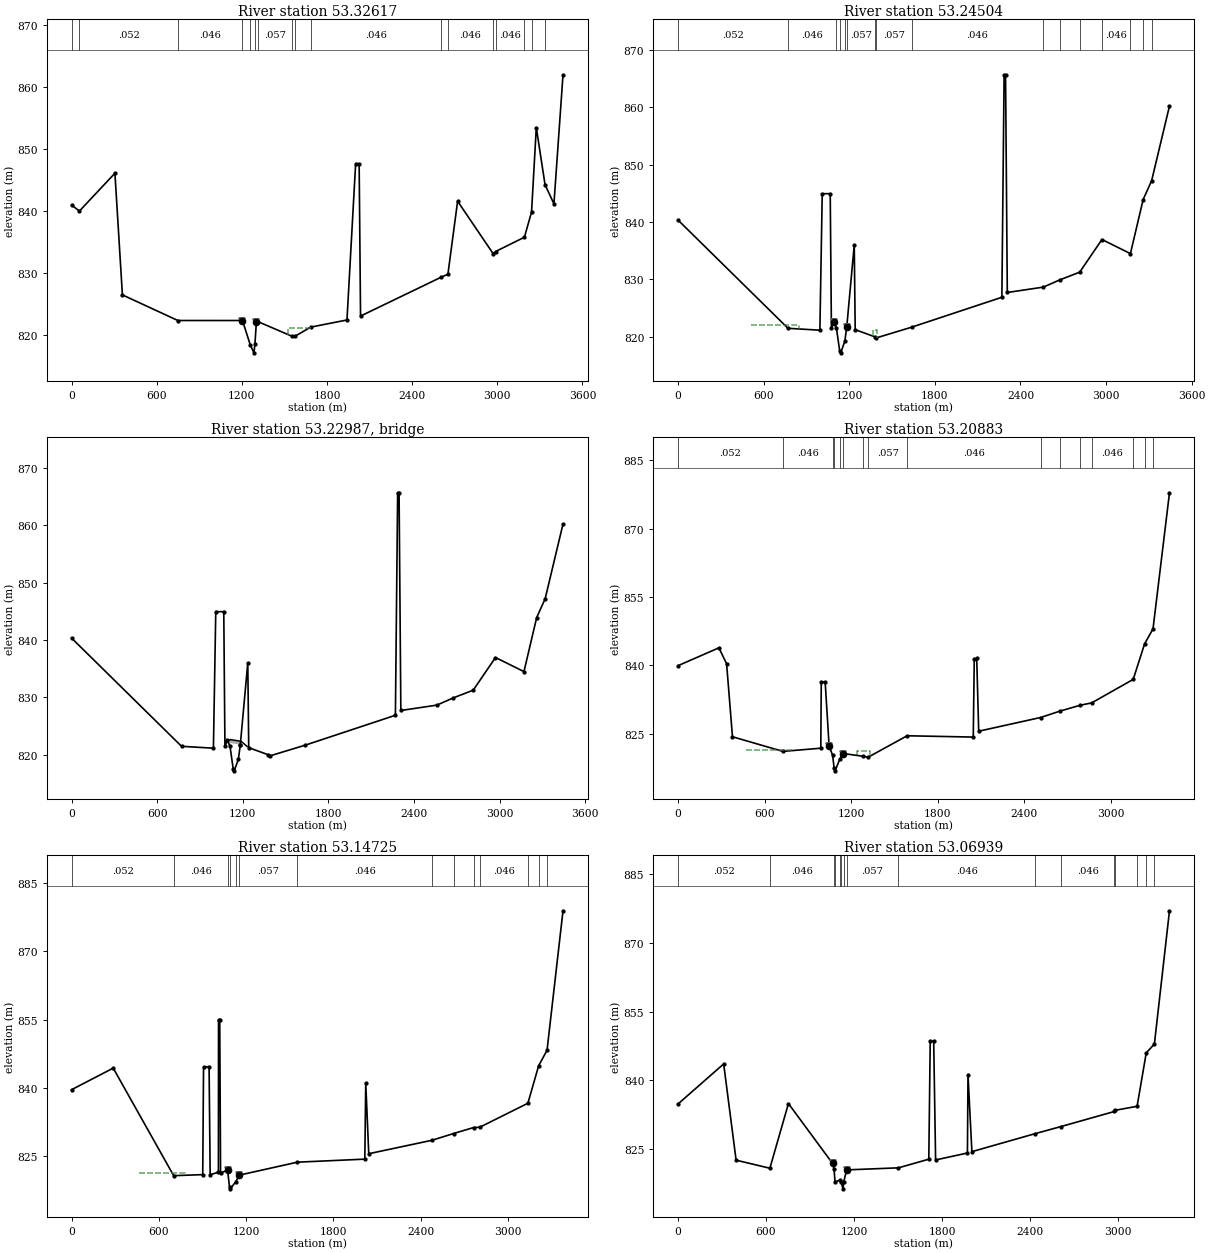
Type RM Length L Ch R = 1 ,53.32617,137.5181,130.8509,125.605
XS GIS Cut Line= 5
       563816.39      4827269.62       564440.06      4828259.48
       564414.77      4828481.69       564402.89      4828618.98
       565698.09      4830051.96
#Sta/Elev= 30
       0840.9691 55.4081840.0068305.6059846.0892358.3351826.5161749.0399822.3961
 1204.35822.39421204.421822.39491259.828818.42611285.159817.19411292.124818.6072
 1302.66822.23221311.426822.23391556.604819.82911573.919819.85591684.734 821.329
1940.711  822.482001.755847.62992026.509847.59392036.299823.10992603.114829.3489
2651.942 829.8432720.244  841.592969.842 833.1762987.503833.49483191.125835.7952
3241.338839.86083274.717853.44493336.225 844.2573398.959841.1611 3462.97 861.929
#Mann= 17 ,-1 , 0
       0    .036       0 55.4081    .052       0749.0399    .046       0
1204.421    .082       01259.828    .037       01292.124    .082       0
1311.426    .057       01556.604    .026       01573.919    .057       0
1684.734    .046       02603.114    .052       02651.942    .046       0
2969.842    .036       02987.503    .046       03191.125    .036       0
3241.338    .046       03336.225    .036       0
Levee=-1,1204.35,822.3779,-1,1302.66,822.2163,,
#XS Ineff= 2 ,-1
  487.68  868.68822.35041525.8231684.919821.1312
Permanent Ineff=
       T       T
Bank Sta=1204.35,1302.66
XS Rating Curve= 0 ,0
Exp/Cntr=0.3,0.1

Type RM Length L Ch R = 1 ,53.24504,73.1611,58.3869,38.531
XS GIS Cut Line= 5
       563717.41      4827363.84       564295.54      4828276.33
       564300.43      4828381.85       564293.44      4828650.65
       565631.76      4830123.09
#Sta/Elev= 30
       0  840.33 770.884 821.479994.3311 821.1511010.753844.92391066.846844.9239
1075.081 821.4461090.739822.51731110.514   821.51132.559817.61291139.739817.2069
 1169.07 819.1961182.504821.71891182.621821.71791235.168835.99321241.768821.2449
1378.497820.00711389.864819.81081636.492821.66712269.793 826.884 2285.54 865.632
2295.543865.62982307.906827.71612560.657828.65312674.671829.90392815.207 831.253
2971.244836.94513170.682834.48693259.894843.89613319.485847.18493444.521860.1998
#Mann= 16 ,-1 , 0
       0    .052       0 770.884    .046       01110.514    .082       0
1132.559    .037       0 1169.07    .082       01182.504    .057       0
1378.497    .026       01389.864    .057       01636.492    .046       0
2560.657    .052       02674.671    .046       02815.207    .036       0
2971.244    .046       03170.682    .036       03259.894    .046       0
3319.485    .036       0
Levee=-1,1090.739,822.5546,-1,1182.621,821.7133,,
#XS Ineff= 2 ,-1
  510.54  845.82822.04561368.3511393.863821.1312
Permanent Ineff=
       T       T
Bank Sta=1090.739,1182.621
XS Rating Curve= 0 ,0
Exp/Cntr=0.3,0.1

Type RM Length L Ch R = 3 ,53.22987,,,
BEGIN DESCRIPTION:
Greenbelt Pathway Friendship Bridge (RM 53.23)
END DESCRIPTION:
Bridge Culvert--1,0,-1,-1, 0
Deck Dist Width WeirC Skew NumUp NumDn MinLoCord MaxHiCord MaxSubmerge Is_Ogee
21.336,3.6576,1.44,0, 6, 6, , , 0.95, 0, 0,0,,
 1089.66 1112.52 1112.52 1188.72 1188.721231.392
822.3504822.6552822.6552822.3504822.3504 821.436
 819.912 819.912822.0456821.7408 819.912 819.912
 1043.94  1066.8  1066.8    1143    11431185.672
822.3504822.6552822.6552822.3504822.3504 821.436
 819.912 819.912822.0456821.7408 819.912 819.912
BR Coef=-1 , 0 , 0 ,1.25, 0 ,,,0.8,-1,2,0,
WSPro=,,,, 1 ,,,, 0 ,,,, 0 ,,,,-1 ,-1 ,-1 , 0 , 0 , 0 , 0 , 0
BC Design=,, 0 ,, 0 ,,,,,,
BC Use User HTab Curves=0
BC User HTab FreeFlow(D)= 0

Type RM Length L Ch R = 1 ,53.20883,103.5991,99.3279,92.7549
XS GIS Cut Line= 5
       563649.49      4827442.28       564206.08      4828307.09
       564274.74      4828409.83       564266.65      4828660.28
       565606.56      4830153.34
#Sta/Elev= 30
       0839.9279283.6679 843.848336.9969840.3409377.7581824.3319727.4241821.1221
 990.254821.8262993.6458836.41911020.774836.28191048.064 822.2691072.047 820.307
1082.614 817.5121089.551 816.8571121.133819.36491141.585820.45911146.085820.6542
1285.433 820.0431318.157 819.8451589.152824.55192047.751824.26482054.772841.3909
2071.716841.53692085.557825.55382514.282828.55622650.631829.97592789.367831.2469
2869.131 831.765 3157.17836.92413236.254 844.7273294.541848.01093408.734 877.864
#Mann= 16 ,-1 , 0
       0    .052       0727.4241    .046       01072.047    .082       0
1082.614    .037       01121.133    .082       01141.585    .057       0
1285.433    .026       01318.157    .057       01589.152    .046       0
2514.282    .052       02650.631    .046       02789.367    .036       0
2869.131    .046       0 3157.17    .036       03236.254    .046       0
3294.541    .036       0
Levee=-1,1048.064,822.2925,-1,1146.085,820.6526,,
#XS Ineff= 2 ,-1
  472.44   800.1 821.4361243.8031332.211821.1312
Permanent Ineff=
       T       T
Bank Sta=1048.064,1146.085
XS Rating Curve= 0 ,0
Exp/Cntr=0.3,0.1

Type RM Length L Ch R = 1 ,53.14725,124.8369,125.5739,126.5911
XS GIS Cut Line= 5
       563602.61      4827486.29       564116.76      4828373.28
       564217.39      4828480.73       564243.07      4828661.56
       565595.94      4830166.63
#Sta/Elev= 30
       0839.5552286.4629844.3118702.1199820.6201901.8931820.8511907.4521844.4862
 945.514844.6465 952.963820.8231 1009.74 821.3871010.449855.00671018.693854.9031
1024.517821.21411072.421821.82561072.777821.83011085.955818.09991090.785 817.722
1128.866819.2679 1153.58820.78441154.207820.74711552.571823.59492016.274 824.263
2022.544841.06512043.304825.45812478.707828.42412626.699829.91092764.218831.2241
2807.129831.3008 3137.24836.57123211.574844.85993269.014 848.2453378.827 878.967
#Mann= 14 ,-1 , 0
       0    .052       0702.1199    .046       01072.777    .082       0
1085.955    .037       01128.866    .082       01154.207    .057       0
1552.571    .046       02478.707    .052       02626.699    .046       0
2764.218    .036       02807.129    .046       0 3137.24    .036       0
3211.574    .046       03269.014    .036       0
Levee=-1,1072.421,821.8384,-1,1153.58,820.8081,,
#XS Ineff= 2 ,-1
  464.82  777.24821.1312  1600.2 1630.68820.8264
Permanent Ineff=
       T       T
Bank Sta=1072.421,1153.58
XS Rating Curve= 0 ,0
Exp/Cntr=0.3,0.1

Type RM Length L Ch R = 1 ,53.06939,91.8622,91.4101,89.855
XS GIS Cut Line= 6
       563532.67      4827571.93       563991.64      4828420.68
       564132.24      4828575.07       564173.26      4828621.69
       564228.15      4828731.79       565574.07      4830199.87
#Sta/Elev= 30
       0834.8301311.2029 843.574396.0739822.5729626.2101 820.812752.8011834.9234
 1053.23821.87621063.452820.68191070.488  817.841106.003 818.2381109.354817.9131
1125.739 816.3191128.786817.7351 1149.56 820.4531149.696820.45261502.368 820.902
1709.669822.78421719.435 848.5511743.038848.5053 1756.12822.62021973.055824.1359
1976.866841.25292003.459824.4331 2433.14828.34492611.393 829.9142975.587833.1992
2978.267833.44093129.711 834.326 3192.03845.96693247.647847.91613350.508 876.983
#Mann= 16 ,-1 , 0
       0    .052       0626.2101    .046       01063.452    .082       0
1070.488    .037       01106.003    .082       01109.354    .037       0
1128.786    .082       0 1149.56    .057       01502.368    .046       0
 2433.14    .052       02611.393    .046       02975.587    .036       0
2978.267    .046       03129.711    .036       0 3192.03    .046       0
3247.647    .036       0
Levee=-1,1053.23,821.881,-1,1149.696,820.4759,,
#XS Ineff= 3 ,-1
  441.96  777.24820.8264  792.48   838.2820.8264 1493.52 1584.96820.8264
Permanent Ineff=
       T       T       T
Bank Sta=1053.23,1149.696
XS Rating Curve= 0 ,0
Exp/Cntr=0.3,0.1

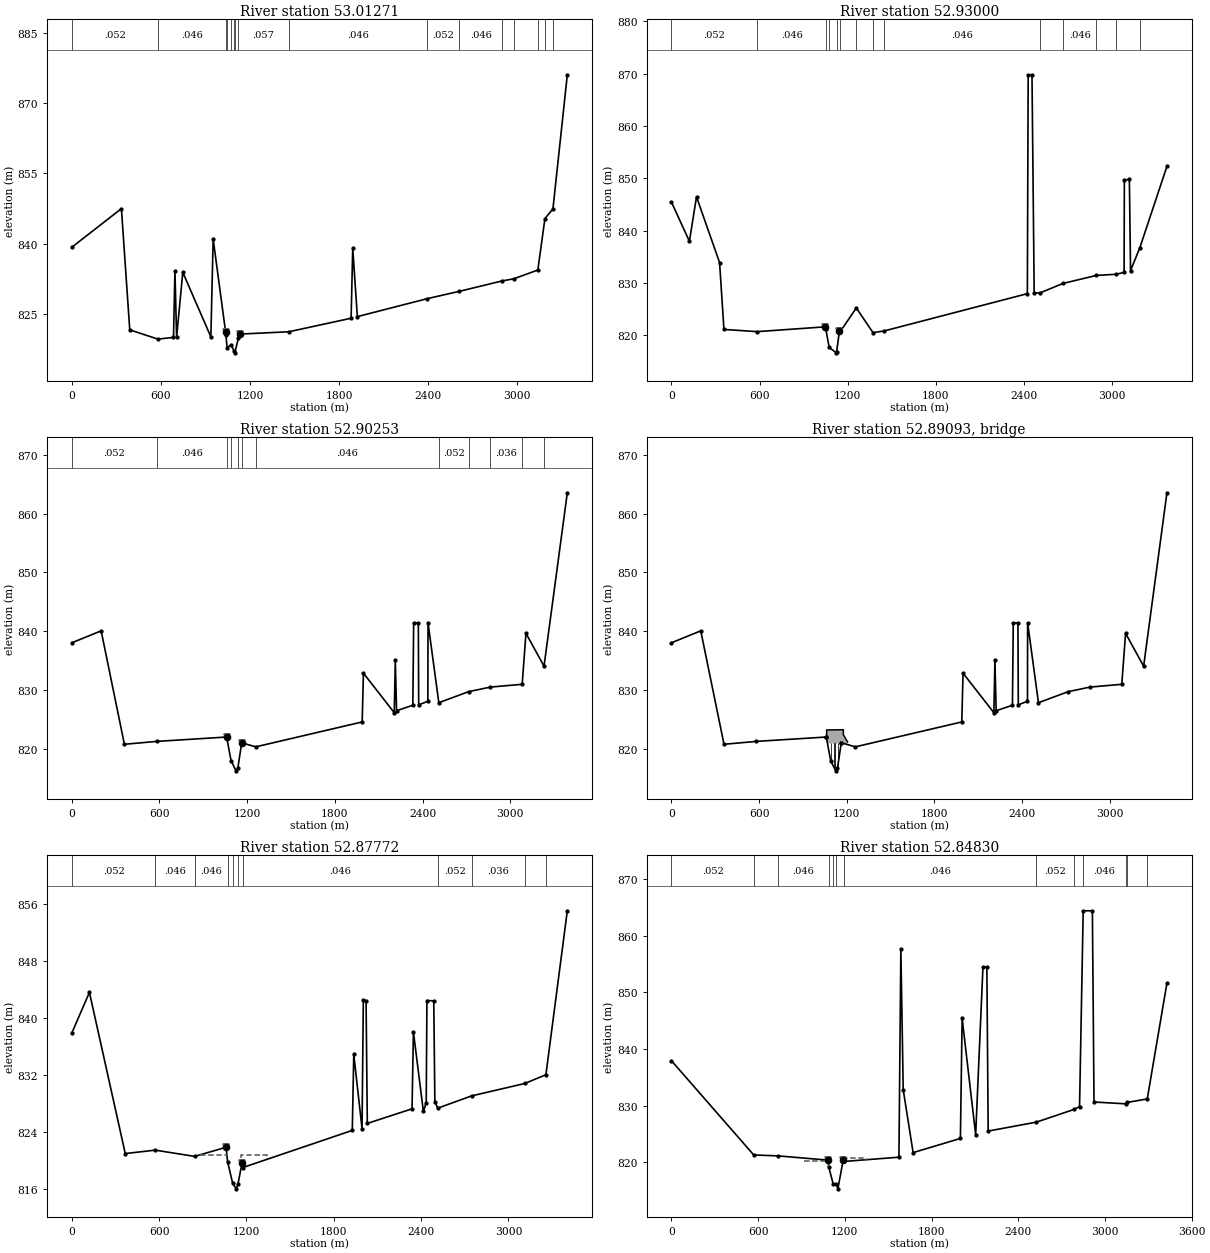
Type RM Length L Ch R = 1 ,53.01271,125.7501,133.411,129.9301
XS GIS Cut Line= 6
       563463.52       4827664.2       563921.19      4828481.37
       563985.74      4828550.07       564060.04      4828628.69
       564092.99      4828662.98       565546.44      4830247.13
#Sta/Elev= 30
       0839.1961 334.333847.4489 390.489821.5842579.8829819.6169684.9261819.9751
 694.702834.1169705.9131820.0032 747.522833.8621936.5998820.0931 951.962 840.981
1035.363821.22941038.318820.42011045.659817.79791071.683818.34111094.372817.0539
1097.708816.68211122.064819.84311130.436820.68081460.385821.17381880.747 824.061
1891.765 838.9691922.898 824.4092394.271828.25012606.806 829.7822898.416  832.03
2975.156 832.4683137.977 834.351 3185.69845.31193239.741847.40413336.499 876.004
#Mann= 16 ,-1 , 0
       0    .052       0579.8829    .046       01038.318    .082       0
1045.659    .037       01071.683    .057       01094.372    .037       0
1097.708    .082       01122.064    .057       01460.385    .046       0
2394.271    .052       02606.806    .046       02898.416    .036       0
2975.156    .046       03137.977    .036       0 3185.69    .046       0
3239.741    .036       0
Levee=-1,1035.363,821.2288,-1,1130.436,820.7015,,
#XS Ineff= 3 ,-1
  426.72  716.28820.8264  731.52  906.78820.8264 1386.84 1546.86820.8264
Permanent Ineff=
       T       T       T
Bank Sta=1035.363,1130.436
XS Rating Curve= 0 ,0
Exp/Cntr=0.3,0.1

Type RM Length L Ch R = 1 ,52.93000,39.3009,44.3231,45.2329
XS GIS Cut Line= 6
       563381.78      4827723.57       563841.07      4828571.18
       563901.92       4828643.8       563976.61      4828732.25
        564016.7      4828780.19       565518.28      4830298.13
#Sta/Elev= 30
       0845.5179122.6799837.9961171.0769846.4891328.0931 833.923 357.784821.1531
584.4041820.73281048.701821.65331050.781 821.2441073.712817.71991122.572816.6811
1124.633816.91711143.482820.78411148.912820.73581258.509825.25091372.153820.5469
1448.028 820.8632422.445827.99012428.061869.69982453.962 869.808 2468.92828.1069
  2509.6 828.1452664.047 829.9322890.997831.46793027.234831.69323080.672 832.051
 3082.58849.66663116.632 849.8223124.669832.40093187.751 836.7513372.213 852.311
#Mann= 14 ,-1 , 0
       0    .052       0584.4041    .046       01050.781    .082       0
1073.712    .037       01124.633    .082       01148.912    .057       0
1258.509    .046       01372.153    .057       01448.028    .046       0
  2509.6    .052       02664.047    .046       02890.997    .036       0
3027.234    .046       03187.751    .036       0
Levee=-1,1048.701,821.686,-1,1143.482,820.7868,,
#XS Ineff= 3 ,-1
  518.16  678.18820.8264  701.04 1021.08820.8264  1219.2 1539.24820.8264
Permanent Ineff=
       T       T       T
Bank Sta=1048.701,1143.482
XS Rating Curve= 0 ,0
Exp/Cntr=0.5,0.3

Type RM Length L Ch R = 1 ,52.90253,37.7239,40.0449,43.1051
BEGIN DESCRIPTION:
Capitol Avenue Bridge Upstream
END DESCRIPTION:
XS GIS Cut Line= 5
       563349.12      4827738.48       563850.84      4828637.93
       563950.43      4828777.35       564031.09       4828893.3
       565458.93      4830360.96
#Sta/Elev= 30
       0838.0062201.0449840.0432 360.109820.7328 581.406821.22381059.751821.9691
1059.896821.92631089.924817.93811124.095816.21111136.368 816.6861162.471820.9809
1162.472 820.9811258.752820.29691986.755 824.534 1995.41832.83252206.317 826.105
2213.422835.07792221.927826.44292333.257827.37682338.996841.42182370.931 841.376
2373.398827.45892436.089 828.0452437.163841.42182511.062827.81092714.808829.6909
2864.312830.47393081.281830.94213107.262839.62013230.782834.0279 3390.12 863.549
#Mann= 12 ,-1 , 0
       0    .052       0 581.406    .046       01059.751    .082       0
1089.924    .037       01136.368    .082       01162.472    .057       0
1258.752    .046       02511.062    .052       02714.808    .046       0
2864.312    .036       03081.281    .046       03230.782    .036       0
Levee=-1,1059.896,821.9603,-1,1162.471,820.988,,
#XS Ineff= 3 ,-1
  594.36  678.18821.1312  701.04 1059.18820.8264 1173.48 1539.24820.8264
Permanent Ineff=
       T       T       T
Bank Sta=1059.896,1162.471
XS Rating Curve= 0 ,0
Exp/Cntr=0.5,0.3

Type RM Length L Ch R = 3 ,52.89093,,,
BEGIN DESCRIPTION:
Capitol Street Bridge
END DESCRIPTION:
Bridge Culvert--1,0,-1,-1, 0
Deck Dist Width WeirC Skew NumUp NumDn MinLoCord MaxHiCord MaxSubmerge Is_Ogee
9.144,18.288,1.44,0, 14, 14, , , 0.95, 0, 0,0,,
 1051.561062.2281062.2281070.7621070.7621162.2021162.2021170.1271170.1271174.699
1174.6991176.5281176.5281205.484
821.7408822.1157823.1733823.1733823.1733  823.21  823.21  823.21  823.21  823.21
  823.21  823.21822.3748821.1312
 813.816 813.816815.6448815.6448 820.863820.8934815.6448815.6448 821.055 821.055
815.6448815.6448 813.816 813.816
 1051.561062.2281062.2281070.7621070.7621162.2021162.2021170.1271170.1271174.699
1174.6991176.5281176.5281205.484
821.7408822.1157823.1733823.1733823.1733  823.21  823.21  823.21  823.21  823.21
  823.21  823.21822.3748821.1312
 813.816 813.816815.6448815.6448 820.863820.8934815.6448815.6448 821.055 821.055
815.6448815.6448 813.816 813.816
Pier Skew, UpSta & Num, DnSta & Num=  ,1092.708, 2 ,1092.708, 2 , 0 , 0 , 0 ,,
  1.8288  1.8288
  815.34 821.436
  1.8288  1.8288
  815.34 821.436
Pier Skew, UpSta & Num, DnSta & Num=  ,1115.568, 2 ,1115.568, 2 , 0 , 0 , 0 ,,
  1.8288  1.8288
  815.34 821.436
  1.8288  1.8288
  815.34 821.436
Pier Skew, UpSta & Num, DnSta & Num=  ,1138.428, 2 ,1138.428, 2 , 0 , 0 , 0 ,,
  1.8288  1.8288
  815.34 821.436
  1.8288  1.8288
  815.34 821.436
BR Coef=-1 , 0 , 0 ,1.25, 0 ,,,0.8,-1,2,0,
WSPro=,,,, 1 ,,,, 0 ,,,, 0 ,,,,-1 ,-1 ,-1 , 0 , 0 , 0 , 0 , 0
BC Design=,, 0 ,, 0 ,,,,,,
BC Use User HTab Curves=0
BC User HTab FreeFlow(D)= 0

Type RM Length L Ch R = 1 ,52.87772,44.7449,47.4741,55.7961
BEGIN DESCRIPTION:
Capitol Avenue Bridge Downstream
END DESCRIPTION:
XS GIS Cut Line= 5
       563328.67      4827751.03       563809.92      4828632.98
       563935.01      4828839.84       563983.23      4828914.62
       565429.98      4830394.14
#Sta/Elev= 30
       0837.8979121.3741 843.644 367.541820.9761574.0399821.4531843.6959820.5759
1060.329821.86031070.792 819.8091105.521816.79611130.376 816.0131141.951 816.678
1169.606819.65671173.615 818.997 1927.38824.23011937.598834.92651994.288824.4932
2003.237842.53122021.991842.4916  2030.7825.21092337.907 827.2652347.372838.0629
2415.785 826.8912435.345828.13212440.201842.49162487.086842.44892494.814828.2449
2514.744827.36012746.607829.08013113.639 830.832 3257.66 832.0623404.744 855.113
#Mann= 11 ,-1 , 0
       0    .052       0574.0399    .046       0843.6959    .046       0
1070.792    .082       01105.521    .037       01141.951    .082       0
1173.615    .046       02514.744    .052       02746.607    .036       0
3113.639    .046       0 3257.66    .036       0
Levee=-1,1060.329,821.9481,-1,1169.606,819.659,,
#XS Ineff= 2 ,-1
  883.92  1066.8820.8264 1165.86 1341.12820.8264
Permanent Ineff=
       F       F
Bank Sta=1060.329,1169.606
XS Rating Curve= 0 ,0
Exp/Cntr=0.5,0.3

Type RM Length L Ch R = 1 ,52.84830,26.6801,36.1941,47.743
XS GIS Cut Line= 6
         563320.      4827757.96       563787.23       4828617.4
        563799.8      4828689.21       563875.45      4828858.19
       563898.92      4828902.06       565401.57       4830429.7
#Sta/Elev= 30
       0837.9339569.8721821.2869 738.228 821.1271082.546 820.379 1087.97 819.236
1119.515816.19191142.488816.11291152.171815.3102 1189.18820.44621192.892  820.14
1574.522820.89311587.878857.64111604.227832.80111672.635 821.7031999.838 824.202
2011.839845.3903 2105.49824.88092155.843854.40112182.914854.4559 2192.02825.5029
2525.338827.08092786.615 829.3272824.279829.82812849.447864.37622913.028864.3762
2924.417830.63213142.528 830.3133154.186830.56413292.712831.17193428.835  851.61
#Mann= 13 ,-1 , 0
       0    .052       0569.8721    .046       0 738.228    .046       0
 1087.97    .082       01119.515    .037       01142.488    .082       0
1192.892    .046       02525.338    .052       02786.615    .036       0
2849.447    .046       03142.528    .036       03154.186    .046       0
3292.712    .036       0
Levee=-1,1082.546,820.4028,-1,1189.18,820.4454,,
#XS Ineff= 2 ,-1
   914.4 1089.66820.2168 1203.96 1348.74820.8264
Permanent Ineff=
       T       F
Bank Sta=1082.546,1189.18
XS Rating Curve= 0 ,0
Exp/Cntr=0.5,0.3

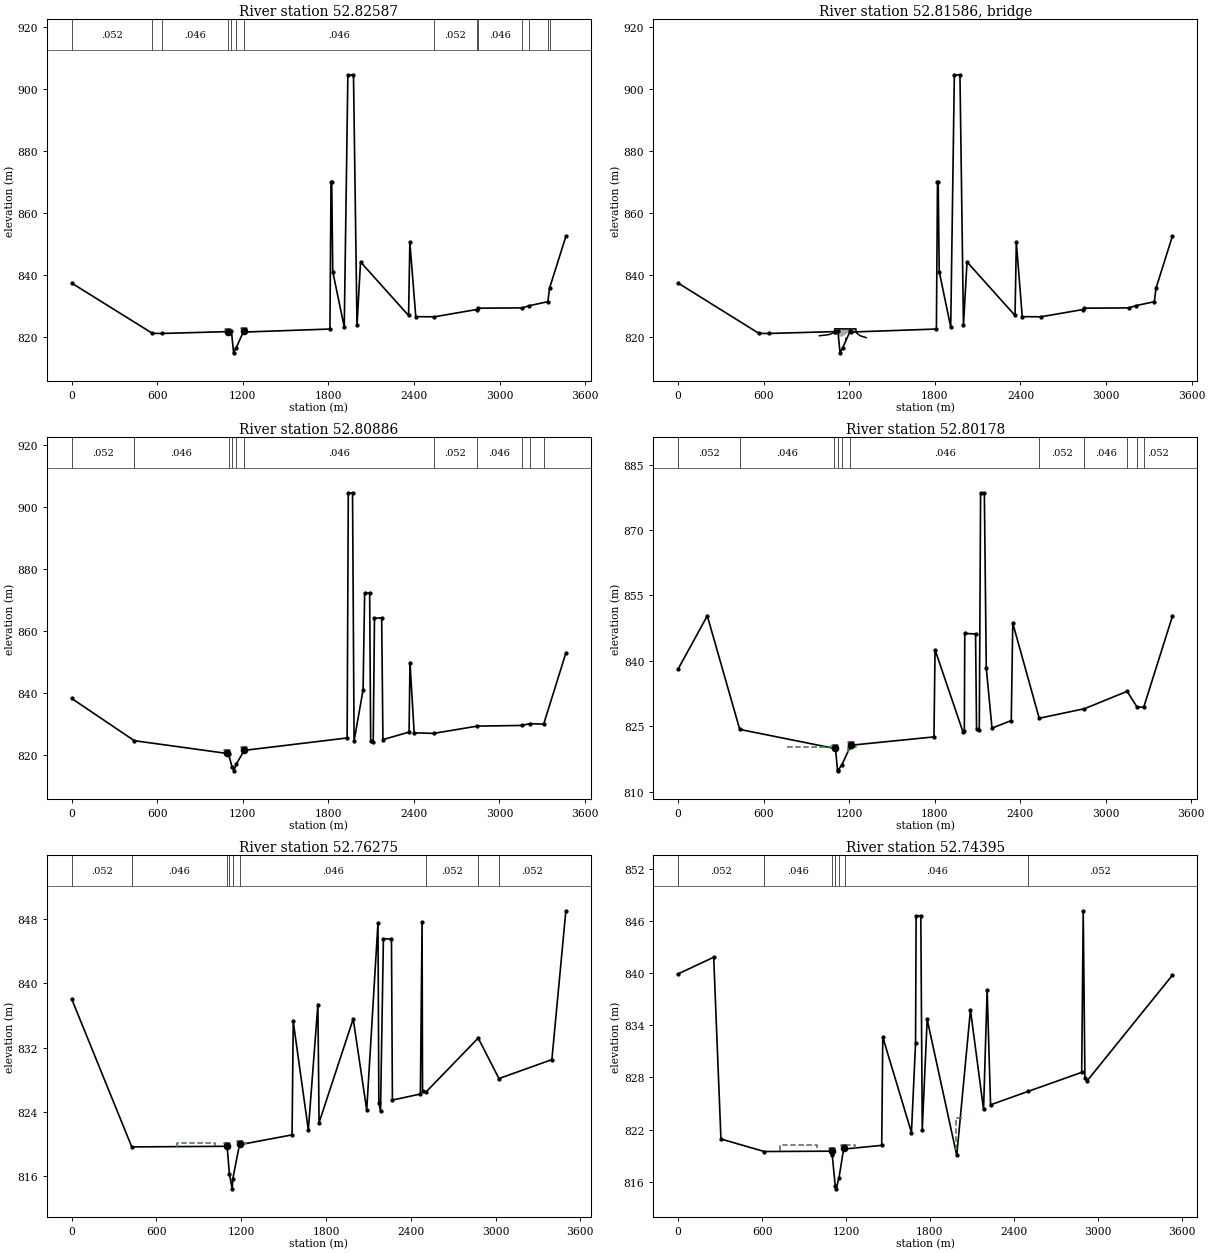
Type RM Length L Ch R = 1 ,52.82587,30.4529,27.4521,26.406
BEGIN DESCRIPTION:
9th Street Bridge Upstream
END DESCRIPTION:
XS GIS Cut Line= 5
       563312.96      4827763.59       563774.79      4828621.13
       563791.69      4828706.44       563831.39      4828918.71
       565369.26      4830474.61
#Sta/Elev= 30
       0837.4722566.1111  821.28 635.056821.2571 1096.19821.84811097.317821.8359
1119.749822.07481135.078 815.0161153.702816.69511205.191821.92721210.521821.7039
1810.502 822.6781818.095869.94791822.966870.06071830.269841.15961910.874 823.319
1936.237  904.421975.606904.52292000.203823.86282025.033844.28082361.782 827.037
2370.737850.6389 2412.28826.66392542.301 826.6142838.175 828.9572845.104829.3892
3159.688829.48213206.459830.18193338.459  831.483349.892835.8009 3464.57852.4979
#Mann= 14 ,-1 , 0
       0    .052       0566.1111    .046       0 635.056    .046       0
 1096.19    .082       01119.749    .037       01153.702    .082       0
1210.521    .046       02542.301    .052       02838.175    .036       0
2845.104    .046       03159.688    .036       03206.459    .046       0
3338.459    .036       03349.892    .052       0
Levee=-1,1097.317,821.8536,-1,1205.191,821.9389,,
#XS Ineff= 2 ,-1
  960.12  1104.9820.2168 1203.96  1371.6820.2168
Permanent Ineff=
       T       T
Bank Sta=1097.317,1205.191
XS Rating Curve= 0 ,0
Exp/Cntr=0.5,0.3

Type RM Length L Ch R = 3 ,52.81586,,,
BEGIN DESCRIPTION:
9th Street Bridge
END DESCRIPTION:
Bridge Culvert--1,0,-1,-1, 0
Deck Dist Width WeirC Skew NumUp NumDn MinLoCord MaxHiCord MaxSubmerge Is_Ogee
3.048,19.5072,1.44,0, 20, 20, , , 0.95, 0, 0,0,,
   990.6 1051.56 1097.28 1097.281118.6161118.6161122.8831122.883 1127.76 1127.76
1214.6281214.6281216.1521216.1521220.4191220.4191246.6321246.6321275.588 1318.26
820.5216820.8264821.5548822.7497822.7497822.7497822.7497822.7497822.7497822.7497
822.7344822.7344822.7344822.7344822.7344822.7344822.7344821.5762820.5216 819.912
 810.768 810.768 810.768 813.816 813.816821.5122821.5122 813.816 813.816820.2351
820.2321 813.816 813.816821.5122821.5122 813.816 813.816 810.768 810.768 810.768
 981.4561042.4161088.1361088.1361109.4721109.4721113.7391113.7391118.6161118.616
1205.4841205.4841207.0081207.0081211.2751211.2751237.4881237.4881266.4441309.116
820.5216820.8264821.5548822.7497822.7497822.7497822.7497822.7497822.7497822.7497
822.7344822.7344822.7344822.7344822.7344822.7344822.7344821.5762820.5216 819.912
 810.768 810.768 810.768 813.816 813.816821.5122821.5122 813.816 813.816820.2351
820.2321 813.816 813.816821.5122821.5122 813.816 813.816 810.768 810.768 810.768
Pier Skew, UpSta & Num, DnSta & Num=  ,1171.346, 2 ,1171.346, 2 , 0 , 0 , 0 ,,
   .6096   .6096
  815.34 821.436
   .6096   .6096
  815.34 821.436
BR Coef=-1 , 0 , 0 ,1.25, 0 ,,,0.8,-1,2,0,
WSPro=,,,, 1 ,,,, 0 ,,,, 0 ,,,,-1 ,-1 ,-1 , 0 , 0 , 0 , 0 , 0
BC Design=,, 0 ,, 0 ,,,,,,
BC Use User HTab Curves=0
BC User HTab FreeFlow(D)= 0

Type RM Length L Ch R = 1 ,52.80886,11.3501,11.437,12.6769
BEGIN DESCRIPTION:
9th Street Bridge Downstream and FEMA XS "BG"
PROJECT XS "BG"
END DESCRIPTION:
XS GIS Cut Line= 6
       563296.57      4827777.69       563510.06      4828179.76
       563746.08      4828624.28       563809.75      4828921.65
       564563.29      4829683.74       565359.16      4830488.63
#Sta/Elev= 30
       0838.1589 439.179824.51511092.242820.37521100.894820.09911125.504 815.903
1138.185814.77091153.581816.86181210.082821.38511210.114821.38471932.006825.3942
1940.138904.43091969.899 904.6221980.783824.45512043.861840.92182054.824872.1243
2089.907872.24012097.197824.34112114.924  824.112123.892864.08972174.324864.2056
2183.149824.8629 2366.63827.30312372.761849.77022402.266827.04892538.364826.8699
2844.437  829.223155.363829.4391 3213.25  830.013310.652829.86283466.289852.8432
#Mann= 11 ,-1 , 0
       0    .052       0 439.179    .046       01100.894    .082       0
1125.504    .037       01153.581    .082       01210.082    .046       0
2538.364    .052       02844.437    .046       03155.363    .036       0
 3213.25    .046       03310.652    .052       0
Levee=-1,1092.242,820.3997,-1,1210.114,821.3812,,
#XS Ineff= 2 ,-1
  777.24 1089.66820.2168 1196.34 1264.92820.2168
Permanent Ineff=
       F       F
Bank Sta=1092.242,1210.114
XS Rating Curve= 0 ,0
Exp/Cntr=0.5,0.3

Type RM Length L Ch R = 1 ,52.80178,75.623,62.9921,39.848
XS GIS Cut Line= 5
       563284.77      4827793.74       563738.44      4828629.56
       563765.17      4828757.97       563799.07      4828934.19
       565347.69      4830503.82
#Sta/Elev= 30
       0838.1461 204.437 850.321431.9391824.27491096.141819.91691103.324819.9919
1118.092814.77491120.061814.87211147.101 816.0531204.993 820.1651209.587820.6395
 1794.44822.55621802.084842.53211998.711 823.6192007.577 823.9282010.494846.3016
 2086.21846.15592093.238824.36692112.375 824.1282121.625878.54392147.877878.5342
2161.492838.32192201.487 824.5772336.695826.29912347.146848.64862532.704 826.837
2850.247 829.0243149.761833.01143219.438829.36783266.237829.40113466.609850.1729
#Mann= 11 ,-1 , 0
       0    .052       0431.9391    .046       01096.141    .082       0
1120.061    .037       01147.101    .082       01204.993    .046       0
2532.704    .052       02850.247    .046       03149.761    .036       0
3219.438    .046       03266.237    .052       0
Levee=-1,1103.324,819.9913,-1,1209.587,820.6526,,
#XS Ineff= 2 ,-1
     762 1074.42820.2168 1188.72 1264.92820.2168
Permanent Ineff=
       F       F
Bank Sta=1103.324,1209.587
XS Rating Curve= 0 ,0
Exp/Cntr=0.5,0.3

Type RM Length L Ch R = 1 ,52.76275,28.582,30.334,32.3039
XS GIS Cut Line= 5
       563225.74      4827840.92       563661.45      4828645.17
       563697.62       4828808.7       563788.82      4828935.02
       565289.42      4830625.01
#Sta/Elev= 30
       0838.0632  425.36 819.6731099.837819.7512 1100.13819.75011116.571816.2629
1136.511814.46091140.358815.71891188.882820.04931194.227 819.9621559.945821.1721
1568.229835.26781675.038821.79111742.755 837.3741751.066822.69211992.755835.5878
2088.315 824.2772168.109847.53782174.143825.16612186.039824.13712206.478845.5548
 2263.57845.51522270.163825.49682468.222826.24792480.212847.66412483.435826.5688
2504.939826.44512877.479 833.2053024.397828.17083398.959830.52693498.031849.0311
#Mann= 9 ,-1 , 0
       0    .052       0  425.36    .046       0 1100.13    .082       0
1116.571    .037       01140.358    .082       01194.227    .046       0
2504.939    .052       02877.479    .036       03024.397    .052       0
Levee=-1,1099.837,819.7596,-1,1188.882,820.0705,,
#XS Ineff= 2 ,-1
  746.76 1013.46820.2168  1181.1 1249.68820.2168
Permanent Ineff=
       F       F
Bank Sta=1099.837,1188.882
XS Rating Curve= 0 ,0
Exp/Cntr=0.3,0.1

Type RM Length L Ch R = 1 ,52.74395,95.8441,99.5379,104.423
XS GIS Cut Line= 5
       563176.38       4827866.8       563611.77      4828658.58
       563672.57      4828819.32       563756.43       4828950.7
        565256.7      4830696.62
#Sta/Elev= 30
       0839.9191254.1319841.8342305.8641820.9182615.8499819.47711097.496819.5176
1101.675819.06591122.874815.55091129.151 815.1831149.727816.42211184.029819.8743
1194.953819.77511455.409820.18511462.921832.64651668.006821.66491697.382831.9485
1701.403846.57591734.897846.6094 1745.26 821.998 1780.45834.67351991.914819.0338
2089.972835.77292183.534 824.3162209.181838.09332233.571 824.8512501.911826.3951
2885.218 828.586 2896.12  847.182908.322827.93312923.963 827.6113533.275 839.756
#Mann= 7 ,-1 , 0
       0    .052       0615.8499    .046       01101.675    .082       0
1122.874    .037       01149.727    .082       01194.953    .046       0
2501.911    .052       0
Levee=-1,1097.496,819.5646,-1,1184.029,819.8784,,
#XS Ineff= 3 ,-1
1983.0232039.008823.3532  731.52   990.6820.2168  1181.1 1264.92820.2168
Permanent Ineff=
       T       F       F
Bank Sta=1097.496,1184.029
XS Rating Curve= 0 ,0
Exp/Cntr=0.3,0.1

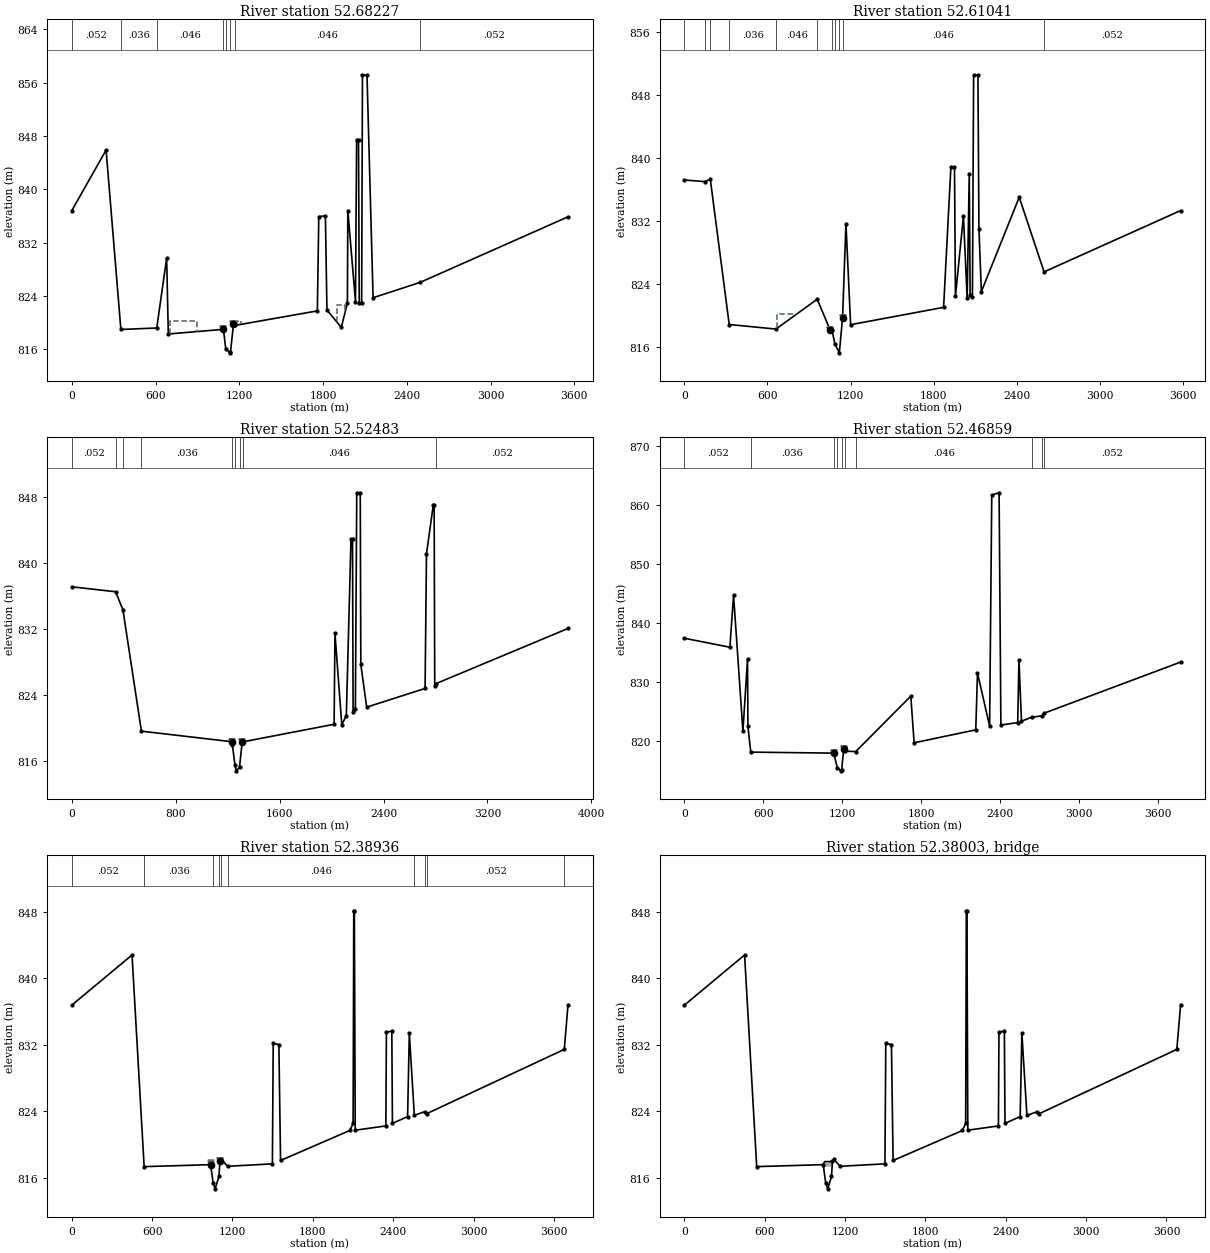
Type RM Length L Ch R = 1 ,52.68227,109.557,115.9801,120.0141
XS GIS Cut Line= 5
       563069.46       4827958.3       563453.35      4828477.03
       563567.32      4828807.18       563672.55      4829033.95
       565196.67      4830770.81
#Sta/Elev= 30
       0 836.808 245.781845.8989 351.624818.9689608.6761819.1881679.6156829.6717
691.4391818.28991086.515 818.9861086.597818.9802 1102.87816.07921135.735815.4589
1137.001815.58391158.484819.73631166.155819.56391759.302821.75521769.596835.9031
1816.922836.03281827.996821.88591930.901819.28411974.506822.93411977.705836.8242
2032.347  823.162040.691847.47912054.128847.42912059.452 822.9172076.527822.8701
2082.602857.1979 2115.01 857.1192158.571 823.7262496.568 826.0433555.352 835.882
#Mann= 8 ,-1 , 0
       0    .052       0 351.624    .036       0608.6761    .046       0
1086.515    .082       0 1102.87    .037       01137.001    .082       0
1166.155    .046       02496.568    .052       0
Levee=-1,1086.597,818.9732,-1,1158.484,819.7382,,
#XS Ineff= 3 ,-1
1899.8311956.499822.7009  701.04  899.16820.2168  1181.1 1211.58820.2168
Permanent Ineff=
       T       F       F
Bank Sta=1086.597,1158.484
XS Rating Curve= 0 ,0
Exp/Cntr=0.3,0.1

Type RM Length L Ch R = 1 ,52.61041,143.7589,138.114,135.3681
XS GIS Cut Line= 5
       563001.65      4828009.65       563352.18      4828491.54
       563476.65       4828850.6       563552.13      4829085.41
       565135.78      4830835.27
#Sta/Elev= 30
       0837.2411146.5299837.0359187.3718837.3289323.8701 818.908 660.996818.3301
959.0709822.1129 1051.63818.25491065.475 818.2021086.613816.46111118.856815.3141
1142.144819.73881142.165819.73761166.605831.71511200.387 818.8831871.627821.0848
1924.208838.85221950.296838.85221957.102 822.4732014.746832.66182041.747 822.251
2056.841 838.0622063.123822.63112079.732822.45592088.404 850.5872119.493850.5261
2126.769831.01592144.328823.08312417.551 835.0532597.051 825.5853582.634 833.361
#Mann= 11 ,-1 , 0
       0    .052       0146.5299    .036       0187.3718    .052       0
323.8701    .036       0 660.996    .046       0959.0709    .036       0
1065.475    .082       01086.613    .037       01118.856    .082       0
1142.144    .046       02597.051    .052       0
Levee=-1,1051.63,818.2539,-1,1142.165,819.726,,
#XS Ineff= 1 ,-1
  670.56  822.96820.2168
Permanent Ineff=
       F
Bank Sta=1051.63,1142.165
XS Rating Curve= 0 ,0
Exp/Cntr=0.3,0.1

Type RM Length L Ch R = 1 ,52.52483,89.6289,90.7569,92.0859
BEGIN DESCRIPTION:
FEMA XS "BF"
PROJECT XS "BF"
END DESCRIPTION:
XS GIS Cut Line= 6
       562706.27      4827954.47       563126.29      4828465.94
       563190.47       4828544.1       563432.73      4829131.61
       563697.23      4829418.38       565074.92      4830911.99
#Sta/Elev= 30
       0837.1201337.3551836.5181393.5169 834.343 536.024819.57311232.885 818.287
1236.714 817.8761255.817815.51191266.788814.74991291.348815.20591311.759818.2543
1316.564818.2719 2019.58  820.412026.023831.46212078.641820.34782113.687 821.476
2149.731842.96892161.248 842.9642165.788821.94992183.165822.31992193.871  848.53
2220.823848.5488 2225.18827.67832270.254822.49092719.878824.7651 2730.74841.1279
2782.866847.03192789.635 847.0562794.295 825.0362803.906825.35083820.555832.0562
#Mann= 9 ,-1 , 0
       0    .052       0337.3551    .036       0393.5169    .052       0
 536.024    .036       01236.714    .082       01255.817    .037       0
1291.348    .082       01316.564    .046       02803.906    .052       0
Levee=-1,1232.885,818.2905,-1,1311.759,818.2509,,
Bank Sta=1232.885,1311.759
XS Rating Curve= 0 ,0
Exp/Cntr=0.3,0.1

Type RM Length L Ch R = 1 ,52.46859,146.9941,127.874,120.1171
XS GIS Cut Line= 5
       562665.58      4828076.33       563108.49      4828574.82
        563256.7       4828930.3       563342.14      4829161.97
       565024.97      4830972.04
#Sta/Elev= 30
       0837.4608345.9891835.9351373.8881 844.756 445.086821.6819 479.928833.9691
483.0922822.5101504.4781 818.1461134.929 817.9731135.641817.93511161.656 815.518
1190.375814.97091194.836815.1022 1210.62818.6401 1219.72818.30511301.915818.2383
1720.515827.64111745.748819.72492214.159 821.9242227.167 831.5662319.353822.5711
2335.679861.75412391.289 862.1312405.047 822.7352532.792823.15692542.147833.7801
2561.387  823.392638.517 824.0562715.433824.29692731.269824.72913770.388 833.418
#Mann= 10 ,-1 , 0
       0    .052       0504.4781    .036       01135.641    .082       0
1161.656    .037       01194.836    .082       0 1219.72    .057       0
1301.915    .046       02638.517    .036       02715.433    .046       0
2731.269    .052       0
Levee=-1,1134.929,817.9765,-1,1210.62,818.6288,,
Bank Sta=1134.929,1210.62
XS Rating Curve= 0 ,0
Exp/Cntr=0.3,0.1

Type RM Length L Ch R = 1 ,52.38936,21.5841,28.3961,30.9061
XS GIS Cut Line= 5
       562582.43      4828218.49       562963.77      4828653.86
        563113.5      4828983.68         563247.      4829203.18
       564961.49      4831033.17
#Sta/Elev= 30
       0836.7781 449.779842.8171540.2672817.3449 1036.25817.58081056.078  815.34
1070.542 814.6711098.692 816.1661106.025817.96591117.219  818.211163.168 817.384
1497.857817.67811504.121 832.1711546.308  832.041558.797 818.0822076.635821.6982
2100.649 822.5642105.519848.13042109.952848.13712116.496 821.7282345.174822.2449
2349.249833.55182389.571 833.6312394.209  822.552507.562823.36212520.261   833.4
2557.932 823.5122633.896823.95212650.571823.72113677.375 831.4563705.536836.8479
#Mann= 10 ,-1 , 0
       0    .052       0540.2672    .036       01056.078    .037       0
1098.692    .082       01117.219    .036       01163.168    .046       0
2557.932    .036       02633.896    .046       02650.571    .052       0
3677.375    .036       0
Levee=-1,1036.25,817.7936,-1,1106.025,817.9857,,
Bank Sta=1036.25,1106.025
XS Rating Curve= 0 ,0
Exp/Cntr=0.3,0.1

Type RM Length L Ch R = 3 ,52.38003,,,
BEGIN DESCRIPTION:
Greenbelt Pathway Pioneer Bridge (RM 52.38)
END DESCRIPTION:
Bridge Culvert--1,0,-1,-1, 0
Deck Dist Width WeirC Skew NumUp NumDn MinLoCord MaxHiCord MaxSubmerge Is_Ogee
12.192,4.572,1.44,0, 6, 6, , , 0.95, 0, 0,0,,
1033.2721048.5121048.5121103.3761103.3761109.472
817.5864817.9613817.9613817.9613817.9613817.9613
  815.34  815.34817.3517817.3517  815.34  815.34
 1021.08 1036.32 1036.321091.1841091.184 1097.28
817.5864817.9613817.9613817.9613817.9613817.9613
  815.34  815.34817.3517817.3517  815.34  815.34
BR Coef=-1 , 0 , 0 ,1.25, 0 ,,,0.8,-1,2,0,
WSPro=,,,, 1 ,,,, 0 ,,,, 0 ,,,,-1 ,-1 ,-1 , 0 , 0 , 0 , 0 , 0
BC Design=,, 0 ,, 0 ,,,,,,
BC Use User HTab Curves=0
BC User HTab FreeFlow(D)= 0

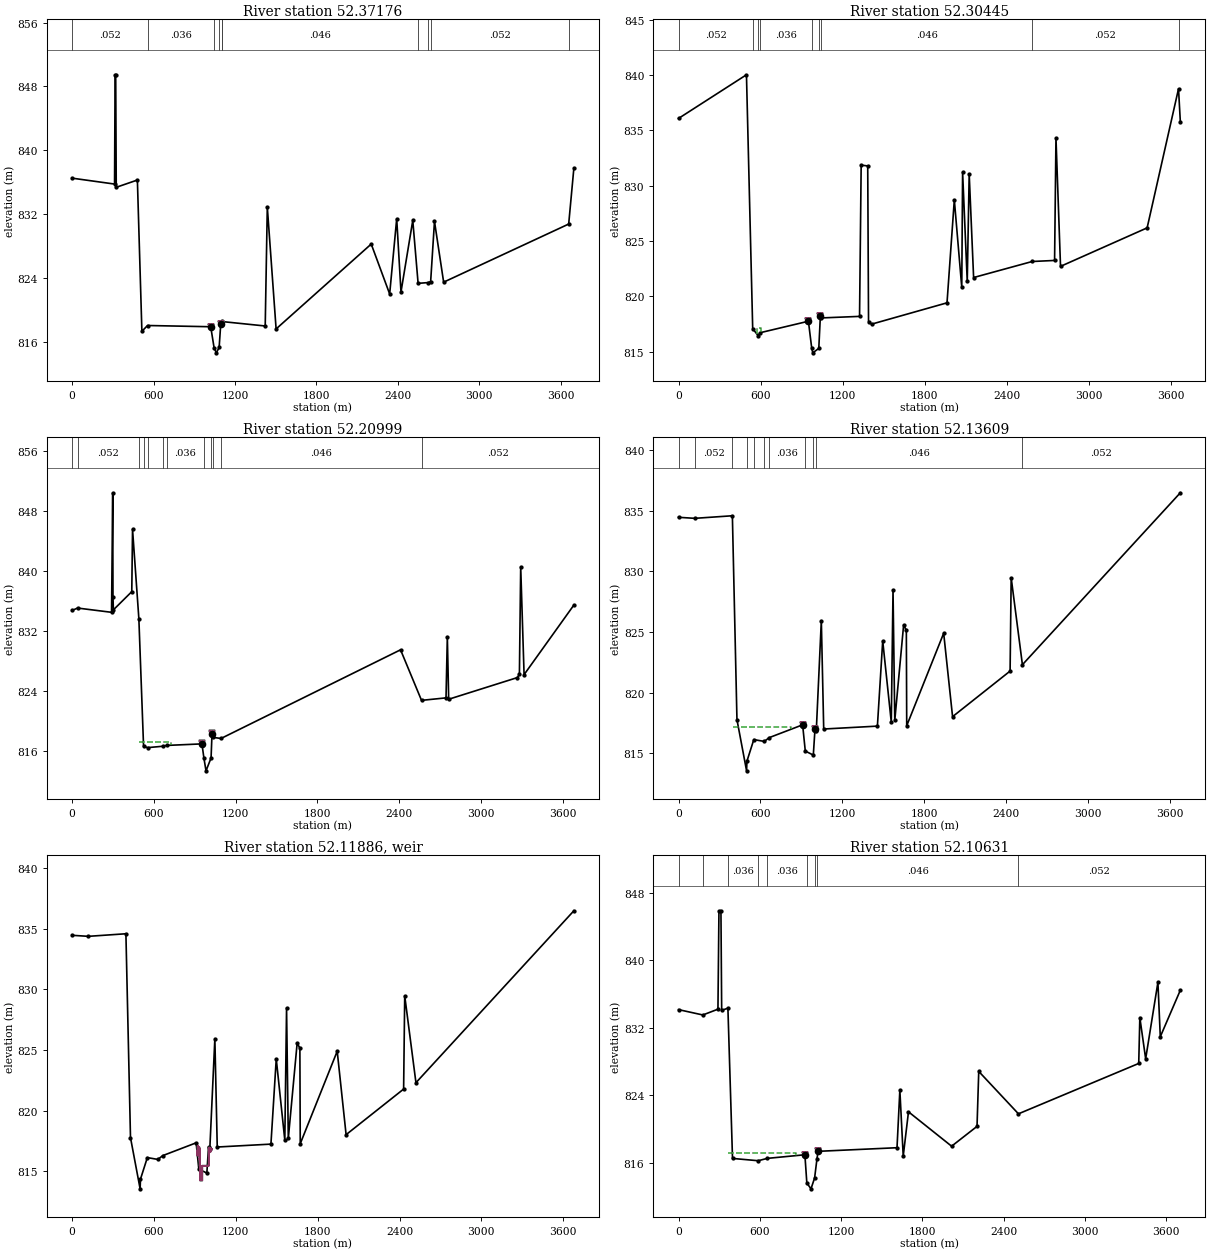
Type RM Length L Ch R = 1 ,52.37176,120.9961,108.635,103.226
XS GIS Cut Line= 5
       562567.48      4828241.07       562944.11      4828671.21
       563097.23      4828994.08       563215.34       4829220.5
       564935.33      4831050.65
#Sta/Elev= 30
       0 836.515312.9439 835.775317.0895849.4593 321.375 849.438325.3831 835.369
 481.068  836.28514.2701817.3362555.8741 818.0641021.254817.9091 1046.33815.2488
1062.708814.6411 1083.29 815.3121095.098818.26931102.509818.57091106.205818.5551
1422.622818.00311438.028832.89341502.829817.63392203.479828.26292339.273822.0099
 2391.11831.4371 2422.65822.25712509.445831.22582548.743823.34412623.771 823.438
2641.142823.56682669.413831.10212736.821 823.4913657.905 830.7693695.974837.7571
#Mann= 10 ,-1 , 0
       0    .052       0555.8741    .036       0 1046.33    .037       0
 1083.29    .082       01102.509    .036       01106.205    .046       0
2548.743    .036       02623.771    .046       02641.142    .052       0
3657.905    .036       0
Levee=-1,1021.254,817.9277,-1,1095.098,818.2478,,
Bank Sta=1021.254,1095.098
XS Rating Curve= 0 ,0
Exp/Cntr=0.3,0.1

Type RM Length L Ch R = 1 ,52.30445,173.148,152.439,141.903
XS GIS Cut Line= 4
       562370.52      4828458.81       562995.14      4829066.68
       563137.57      4829272.14       564913.05      4831094.48
#Sta/Elev= 30
       0836.0679 496.215840.0111541.8101817.0749582.1339816.4312 594.232816.7031
948.7784817.7462972.5461815.3571 980.665814.8911  1024.6 815.2911036.241818.2215
1041.463818.04391322.362818.18411334.238 831.8511382.107831.77481388.068 817.704
1410.189817.48221961.362819.40912014.737 828.7142069.083 820.8162075.267831.1982
2109.163 821.3612123.404831.03112155.672821.69382583.679823.1429 2747.22 823.238
2757.324834.28332790.583822.70213423.313826.18123652.635 838.7453665.833835.7789
#Mann= 9 ,-1 , 0
       0    .052       0541.8101    .036       0582.1339    .026       0
 594.232    .036       0972.5461    .037       0  1024.6    .082       0
1041.463    .046       02583.679    .052       03652.635    .036       0
Levee=-1,948.7784,817.7448,-1,1036.241,818.2203,,
#XS Ineff= 2 ,-1
571.6981605.3298817.1688  502.92   533.4817.1688
Permanent Ineff=
       T       T
Bank Sta=948.7784,1036.241
XS Rating Curve= 0 ,0
Exp/Cntr=0.3,0.1

Type RM Length L Ch R = 1 ,52.20999,123.1029,118.9689,116.354
XS GIS Cut Line= 4
       562233.44      4828595.39        562860.7      4829186.93
       563046.03      4829354.72       564887.45      4831147.54
#Sta/Elev= 30
       0834.7048 40.1361835.0289289.7429834.4589298.3138850.4225 300.192  836.53
 303.158 834.785438.1329 837.217443.7611 845.535490.1041833.6249524.7169816.5439
 554.543816.3879668.6919816.5759693.7269816.6821 953.012816.8879967.6879 814.973
982.8932813.28811019.976 815.0061026.856818.21411034.336 817.7621092.884817.6089
2410.427 829.452  2564.3   822.72744.115823.03312753.765831.20092763.632822.8491
3267.679825.74323282.644826.18123292.123840.54523316.907826.13513682.222835.4251
#Mann= 12 ,-1 , 0
       0    .036       0 40.1361    .052       0490.1041    .036       0
524.7169    .026       0 554.543    .036       0668.6919    .026       0
693.7269    .036       0967.6879    .037       01019.976    .082       0
1034.336    .057       01092.884    .046       0  2564.3    .052       0
Levee=-1,953.012,816.9493,-1,1026.856,818.324,,
#XS Ineff= 1 ,-1
  487.68   723.9817.1688
Permanent Ineff=
       T
Bank Sta=953.012,1026.856
XS Rating Curve= 0 ,0
Exp/Cntr=0.3,0.1

Type RM Length L Ch R = 1 ,52.13609,46.154,47.928,45.396
XS GIS Cut Line= 4
       562177.21      4828690.21       562788.93      4829288.67
       562912.63      4829390.36       564854.37      4831211.44
#Sta/Elev= 30
       0834.4479 119.167834.3629 394.649 834.575428.2251 817.779498.7979813.5621
501.3101 814.358 551.699816.1362628.5689815.9858 664.613 816.298909.5018817.3524
929.0609815.1901987.9089  814.861000.357817.02481009.609816.83991046.633825.9349
1064.103 817.0071457.608817.2459 1496.59824.26791559.372817.57391572.139828.4628
1584.954 817.7151649.861825.57611669.765 825.1471672.523817.27921943.427824.8979
2008.576 818.0252430.214821.78012438.201829.46292520.528 822.3053677.991836.4681
#Mann= 11 ,-1 , 0
       0    .036       0 119.167    .052       0 394.649    .036       0
501.3101    .026       0 551.699    .036       0628.5689    .026       0
 664.613    .036       0929.0609    .037       0987.9089    .082       0
1009.609    .046       02520.528    .052       0
Levee=-1,909.5018,817.3486,-1,1000.357,817.0256,,
#XS Ineff= 1 ,-1
  396.24  822.96817.1688
Permanent Ineff=
       T
Bank Sta=909.5018,1000.357
XS Rating Curve= 0 ,0
Exp/Cntr=0.5,0.3

Type RM Length L Ch R = 5 ,52.11886,,,
BEGIN DESCRIPTION:
Settler's Irrigation District (RM 52.12)
END DESCRIPTION:
IW Pilot Flow=0
#Inline Weir SE= 16
 917.448816.3154 921.002817.1078929.9601816.9554935.4465816.9554935.4465815.4619
939.1041815.4619939.1041814.2427953.7344814.2427953.7344815.4619969.8889815.4619
1002.502815.46191002.502816.95541007.989816.95541012.857816.59281016.639816.6445
1021.184816.8488
IW Dist,WD,Coef,Skew,MaxSub,Min_El,Is_Ogee,SpillHt,DesHd
27.432,3.048,1.77,0,0.98,, 0 ,,,0,0,

Type RM Length L Ch R = 1 ,52.10631,42.928,47.215,50.2521
XS GIS Cut Line= 4
       562130.96      4828738.44       562779.64      4829338.85
       562905.82      4829443.02       564835.98      4831269.69
#Sta/Elev= 30
       0  834.14 179.323833.5061 291.016834.1909 298.416845.8489 313.072845.8581
318.5529 834.052364.5731 834.311 398.576816.4988 587.986816.2252655.4169816.5049
 932.877816.9327947.3721 813.584977.9481812.8931  1004.8 814.1871022.214816.4601
1030.273817.3401 1613.14817.76811634.127824.58311658.995 816.7751697.839822.0248
2016.279817.94782203.902820.29912216.643826.81422509.777821.78593397.889827.7591
3406.046833.1979 3449.08828.3099 3539.52837.37623557.089 830.9263705.015 836.441
#Mann= 9 ,-1 , 0
       0    .036       0 179.323    .052       0364.5731    .036       0
 587.986    .026       0655.4169    .036       0947.3721    .037       0
  1004.8    .082       01022.214    .046       02509.777    .052       0
Levee=-1,932.877,816.928,-1,1030.273,817.3456,,
#XS Ineff= 2 ,-1
  365.76  868.68817.1688 1112.52 1135.38817.1688
Permanent Ineff=
       T       T
Bank Sta=932.877,1030.273
XS Rating Curve= 0 ,0
Exp/Cntr=0.5,0.3