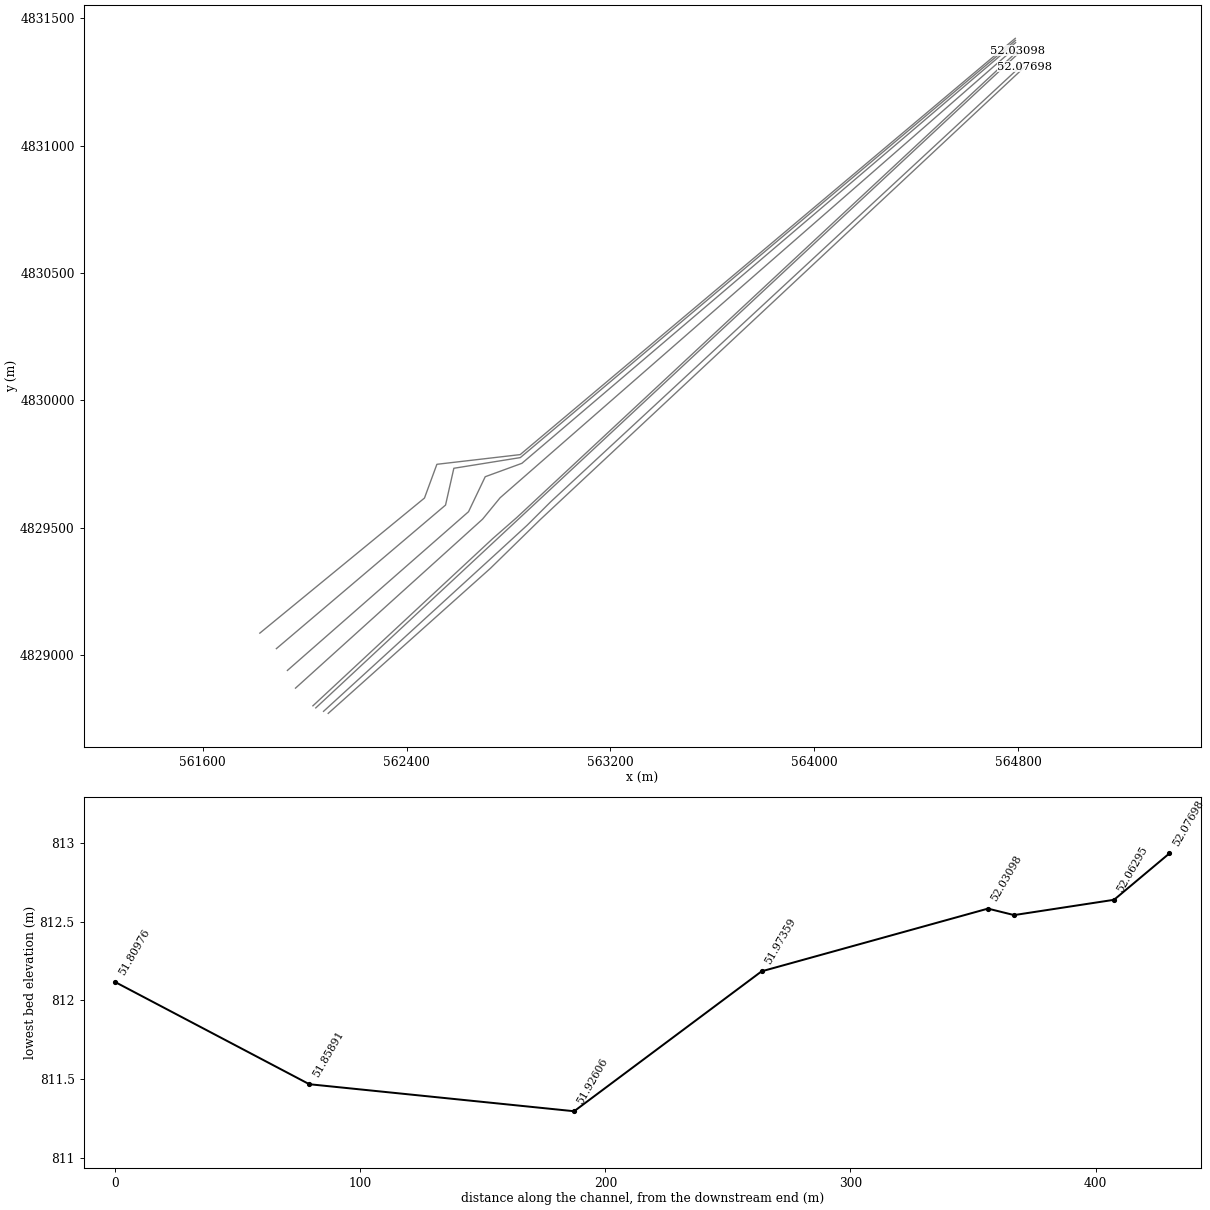
HEC-RAS study Boise2.prj: BoiseRiver_All_reaches

--- Boise2.g01 (geometry) --- (continued)

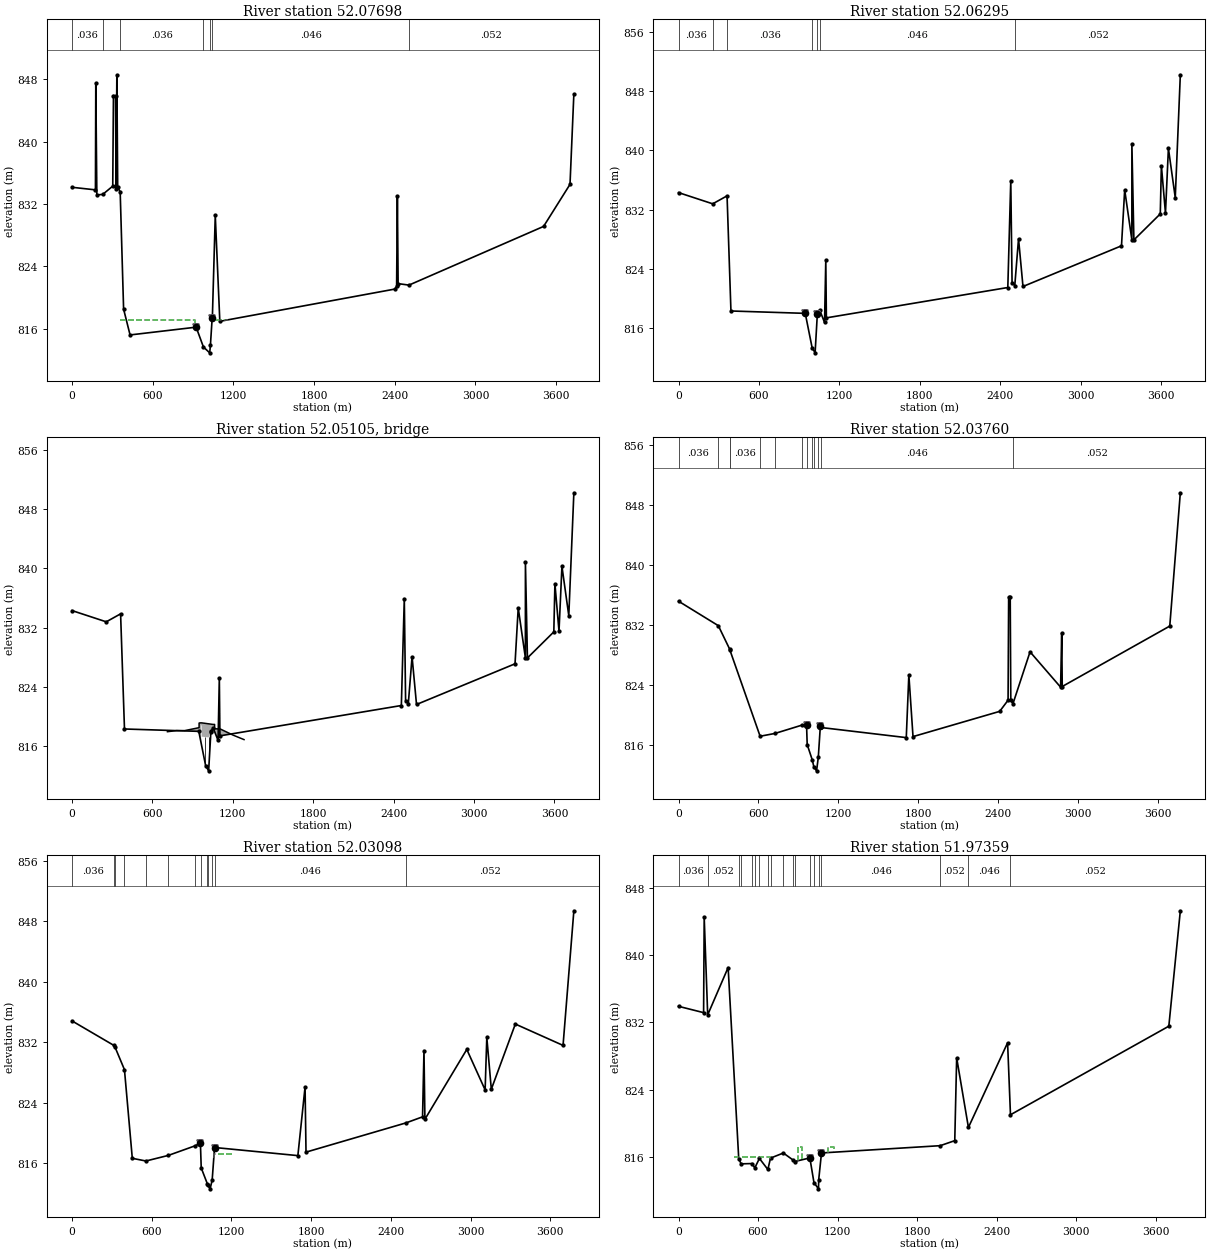
Type RM Length L Ch R = 1 ,52.07698,28.2089,22.596,21.0791
XS GIS Cut Line= 4
       562092.58      4828771.53       562729.55      4829341.18
       562924.87      4829532.18        564827.4      4831310.16
#Sta/Elev= 30
       0 834.141173.8451 833.813176.3786847.4811184.2479833.1619228.0081833.2311
 302.535834.2891 307.759845.8931323.0606 845.884327.1172833.9709333.0184848.5541
339.3439834.2312357.8721833.5189383.2479818.5361431.3481815.2281922.6875816.2233
976.9651813.68091023.546812.93521028.836813.89891041.947817.4067 1043.39 817.451
1064.944830.53221098.816816.97192400.038821.10192413.619821.45612419.194 832.972
2424.787   821.82505.479821.61183506.556829.12923703.082 834.5183731.724846.1041
#Mann= 7 ,-1 , 0
       0    .036       0228.0081    .052       0357.8721    .036       0
976.9651    .037       01028.836    .082       0 1043.39    .046       0
2505.479    .052       0
Levee=-1,922.6875,816.2483,-1,1041.947,817.4127,,
#XS Ineff= 2 ,-1
  358.14   914.4817.1688  1066.8 1158.24817.1688
Permanent Ineff=
       T       T
Bank Sta=922.6875,1041.947
XS Rating Curve= 0 ,0
Exp/Cntr=0.5,0.3

Type RM Length L Ch R = 1 ,52.06295,45.2409,40.7899,40.756
BEGIN DESCRIPTION:
Americana Boulevard Bridge Upstream
END DESCRIPTION:
XS GIS Cut Line= 5
       562074.24      4828779.58       562753.22      4829399.64
       562873.11      4829509.71       562965.98      4829602.16
       564822.65      4831322.86
#Sta/Elev= 30
       0834.3062255.0149832.7889 362.114 833.866391.1279 818.299945.6664817.9784
996.8429813.33511019.163812.64011036.163 817.9851036.671817.9232 1052.64818.4569
1089.732816.74391098.943825.21011103.292817.36992457.293821.4732 2479.35835.9171
2489.056822.14712509.334821.73992537.297 828.0692570.497  821.613305.638 827.112
3329.531 834.6753383.015827.92493383.213840.87923398.169827.90393595.122831.4271
 3603.34837.94093633.832831.52923655.741  840.293706.896833.62713744.715850.2368
#Mann= 7 ,-1 , 0
       0    .036       0255.0149    .052       0 362.114    .036       0
996.8429    .037       01036.163    .082       0 1052.64    .046       0
2509.334    .052       0
Levee=-1,945.6664,817.9613,-1,1036.671,817.9399,,
#XS Ineff= 2 ,-1
  365.76  944.88817.1688 1051.56 1173.48817.1688
Permanent Ineff=
       T       T
Bank Sta=945.6664,1036.671
XS Rating Curve= 0 ,0
Exp/Cntr=0.5,0.3

Type RM Length L Ch R = 3 ,52.05105,,,
BEGIN DESCRIPTION:
Americana Boulevard Bridge
END DESCRIPTION:
Bridge Culvert--1,0,-1,-1, 0
Deck Dist Width WeirC Skew NumUp NumDn MinLoCord MaxHiCord MaxSubmerge Is_Ogee
6.096,25.908,1.44,0, 24, 24, , , 0.95, 0, 0,0,,
 711.708 780.288 841.248 947.928 947.928 955.548962.1012962.1012966.6732966.6732
  967.74  967.74 1051.56 1051.561052.4741052.4741057.0461057.0461063.7521063.752
1067.6231106.4241200.9121283.208
817.9308818.0832818.0832818.4794819.1013819.1256819.1256819.1256819.1256819.1256
819.1256819.1256818.9153818.9153818.9153818.9153818.9153818.9153818.9153818.3362
 818.327818.2966817.4736 816.864
  807.72  807.72  807.72  807.72  807.72 810.768 810.768818.7873818.7873 810.768
 810.768817.2603817.0956 810.768 810.768818.4825818.4825 810.768 810.768  807.72
  807.72  807.72  807.72  807.72
 711.708 780.288 841.248 947.928 947.928 955.548962.1012962.1012966.6732966.6732
  967.74  967.74 1051.56 1051.561052.4741052.4741057.0461057.0461063.7521063.752
1067.6231106.4241200.9121283.208
817.9308818.0832818.0832818.4794819.1013819.1256819.1256819.1256819.1256819.1256
819.1256819.1256818.9153818.9153818.9153818.9153818.9153818.9153818.9153818.3362
 818.327818.2966817.4736 816.864
  807.72  807.72  807.72  807.72  807.72 810.768 810.768818.7873818.7873 810.768
 810.768817.2603817.0956 810.768 810.768818.4825818.4825 810.768 810.768  807.72
  807.72  807.72  807.72  807.72
Pier Skew, UpSta & Num, DnSta & Num=  ,995.172, 2 ,995.172, 2 , 0 , 0 , 0 ,,
   .6706   .6706
 810.768 818.388
   .6706   .6706
 810.768 818.388
Pier Skew, UpSta & Num, DnSta & Num=  ,1024.128, 2 ,1024.128, 2 , 0 , 0 , 0 ,,
   .6706   .6706
 810.768 818.388
   .6706   .6706
 810.768 818.388
BR Coef=-1 , 0 , 0 ,1.25, 0 ,,,0.8,-1,2,0,
WSPro=,,,, 1 ,,,, 0 ,,,, 0 ,,,,-1 ,-1 ,-1 , 0 , 0 , 0 , 0 , 0
BC Design=,, 0 ,, 0 ,,,,,,
BC Use User HTab Curves=0
BC User HTab FreeFlow(D)= 0

Type RM Length L Ch R = 1 ,52.03760,13.7181,10.6659,9.5491
BEGIN DESCRIPTION:
Americana Boulevard Bridge Downstream and FEMA XS "BE"
PROJECT XS "BE"
END DESCRIPTION:
XS GIS Cut Line= 4
        562043.7      4828792.99        562285.4      4829018.14
       562931.66      4829620.14       564803.36      4831363.66
#Sta/Elev= 30
       0 835.142299.0789831.8809 383.938 828.767384.6929828.7031 613.235817.1511
 725.257 817.527930.4261 818.648962.2353818.6379  967.01816.04021005.102814.0032
1017.548813.04491037.405812.5428 1050.36 814.3261065.849818.50161069.217818.3188
1711.674816.96891731.058825.33111762.353 817.1032413.791820.46492476.853821.9539
2481.164835.64792492.968835.63972497.318 821.931 2513.32821.47322641.959 828.397
2871.694823.68912880.022830.91712883.921823.77813692.155 831.8273771.489849.5861
#Mann= 13 ,-1 , 0
       0    .036       0299.0789    .052       0 383.938    .052       0
384.6929    .036       0 613.235    .082       0 725.257    .036       0
930.4261    .046       0  967.01    .082       01005.102    .046       0
1017.548    .037       0 1050.36    .082       01069.217    .046       0
 2513.32    .052       0
Levee=-1,962.2353,818.6257,-1,1065.849,818.5679,,
#XS Ineff= 2 ,-1
  929.64  960.12817.1688  1066.8 1203.96817.1688
Permanent Ineff=
       F       F
Bank Sta=962.2353,1065.849
XS Rating Curve= 0 ,0
Exp/Cntr=0.5,0.3

Type RM Length L Ch R = 1 ,52.03098,87.2301,92.3809,98.9759
XS GIS Cut Line= 4
        562032.5      4828801.24       562738.38      4829457.68
       562833.51      4829541.02       564799.42      4831371.99
#Sta/Elev= 30
       0 834.811  314.24831.5761 324.437831.2969  394.31828.3613453.3729816.6241
555.9619  816.27 725.168817.0131 927.611818.2899965.9905818.6418972.1779  815.35
1017.879 813.2671020.523813.08911039.139 812.5841054.515813.74291072.527818.0549
1072.644 818.0561699.567816.9819 1753.78826.07511760.861817.44312513.916821.3171
2638.038822.11512648.816 830.8862655.715821.78892971.057  831.043109.018825.6791
3121.664832.62183155.594825.77083336.441834.39923695.563831.57213776.917849.3941
#Mann= 13 ,-1 , 0
       0    .036       0  314.24    .052       0 324.437    .052       0
  394.31    .036       0555.9619    .082       0 725.168    .036       0
 927.611    .046       0972.1779    .082       01017.879    .046       0
1020.523    .037       01054.515    .082       01072.644    .046       0
2513.916    .052       0
Levee=-1,965.9905,818.6532,-1,1072.527,818.0496,,
#XS Ineff= 2 ,-1
  922.02   952.5817.1688  1066.8 1203.96817.1688
Permanent Ineff=
       F       F
Bank Sta=965.9905,1072.527
XS Rating Curve= 0 ,0
Exp/Cntr=0.5,0.3

Type RM Length L Ch R = 1 ,51.97359,68.523,76.51,85.6009
XS GIS Cut Line= 4
       561964.17      4828870.64       562698.44      4829533.82
        562767.1      4829617.68       564792.25      4831387.17
#Sta/Elev= 30
       0833.9209189.1509833.1689193.7019844.5249220.0309832.9029 374.356838.5441
454.4519  815.76472.6299815.1611556.3331 815.197575.2609  814.67610.4812815.8051
674.1039 814.489694.1759815.8442791.1261 816.451863.0799815.6298875.5779815.4351
 990.981815.8643 991.084815.86551022.139 812.9251056.138 812.1851058.116813.2969
1078.855816.45691078.945816.45891974.973817.32482084.748817.92412099.087827.7871
2187.809819.49512483.462829.57812505.167 821.0053700.309831.55413787.103845.2991
#Mann= 19 ,-1 , 0
       0    .036       0220.0309    .052       0454.4519    .057       0
472.6299    .026       0556.3331    .057       0575.2609    .026       0
610.4812    .057       0674.1039    .026       0694.1759    .057       0
791.1261    .036       0863.0799    .082       0875.5779    .046       0
 991.084    .082       01022.139    .037       01058.116    .082       0
1078.945    .046       01974.973    .052       02187.809    .046       0
2505.167    .052       0
Levee=-1,990.981,815.8704,-1,1078.855,816.4434,,
#XS Ineff= 3 ,-1
415.8387 689.043815.9496  899.16  929.64817.1688 1127.76 1173.48817.1688
Permanent Ineff=
       T       F       F
Bank Sta=990.981,1078.855
XS Rating Curve= 0 ,0
Exp/Cntr=0.3,0.1

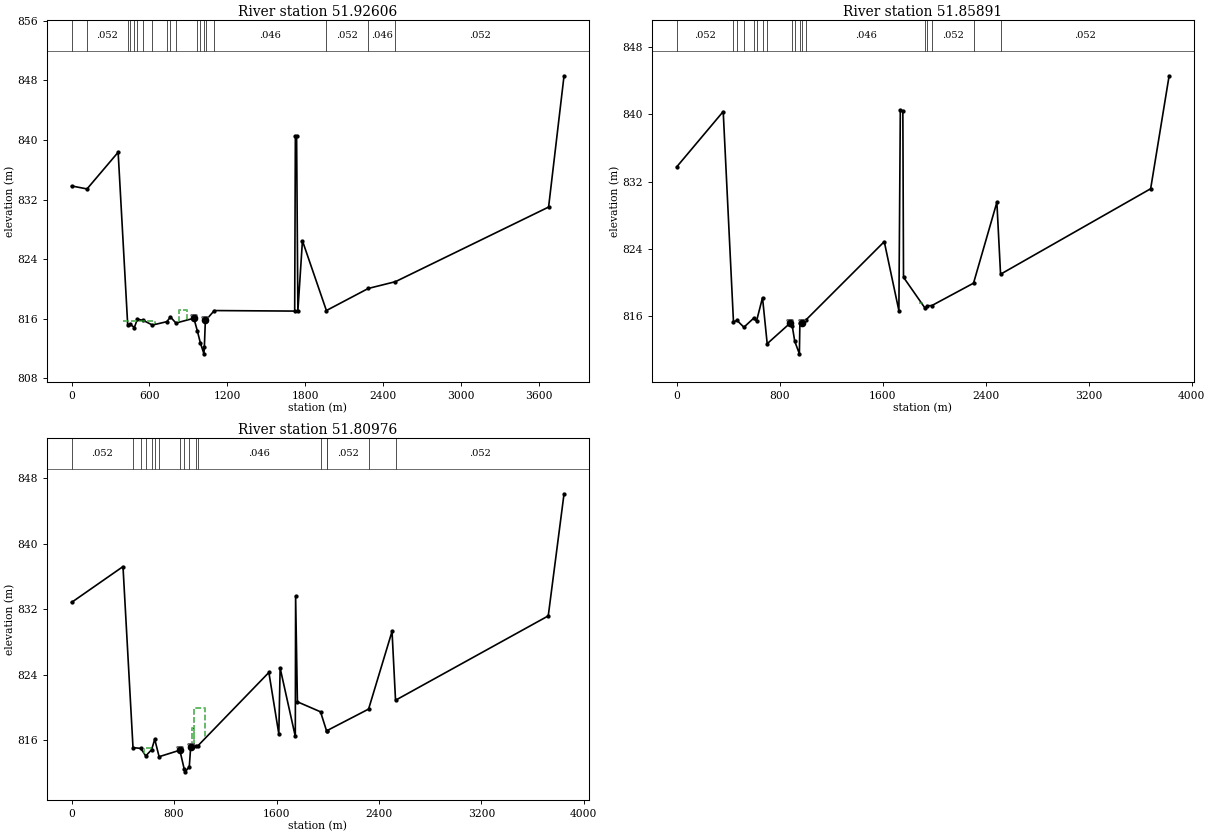
Type RM Length L Ch R = 1 ,51.92606,100.5791,108.083,116.2309
XS GIS Cut Line= 5
       561932.37      4828940.11       562643.29      4829563.07
        562708.8       4829700.4       562852.84      4829753.06
       564790.67      4831404.44
#Sta/Elev= 30
       0833.8218  118.84833.4202358.8261838.3411432.4539815.2053452.1979815.2711
483.7109814.8279507.2509815.9401551.6731 815.793623.0529 815.155734.2988 815.611
762.0159816.2371  804.54 815.426942.6824816.0678970.4591 814.311992.4809812.7791
1020.232 811.2951023.614812.23411031.483815.84831036.523815.83721100.309817.1021
1720.026817.03111725.235 840.514  1734.8840.52561744.589817.0311 1779.79 826.463
1964.459817.10392287.565820.06812496.769820.97693677.689830.9882 3796.79848.6019
#Mann= 19 ,-1 , 0
       0    .036       0  118.84    .052       0432.4539    .036       0
452.1979    .057       0483.7109    .026       0507.2509    .057       0
551.6731    .026       0623.0529    .057       0734.2988    .036       0
762.0159    .082       0  804.54    .046       0970.4591    .082       0
992.4809    .037       01023.614    .082       01036.523    .057       0
1100.309    .046       01964.459    .052       02287.565    .046       0
2496.769    .052       0
Levee=-1,942.6824,816.0898,-1,1031.483,815.8582,,
#XS Ineff= 2 ,-1
399.0167645.4597815.6448  830.58  891.54817.1688
Permanent Ineff=
       T       F
Bank Sta=942.6824,1031.483
XS Rating Curve= 0 ,0
Exp/Cntr=0.3,0.1

Type RM Length L Ch R = 1 ,51.85891,84.2809,79.13,74.2139
XS GIS Cut Line= 5
        561889.1      4829025.67       562553.04      4829589.14
       562585.65      4829733.57       562846.56       4829775.5
       564790.01      4831412.98
#Sta/Elev= 30
       0833.7481361.3568 840.351440.9651 815.293469.2609815.4448 522.038814.6398
597.3799 815.707 619.944815.3619666.6031818.1661702.9349812.6739881.7833 815.138
897.2181 814.816916.7219812.9711952.9459811.4669 956.879815.1861 973.707815.1251
975.1192815.14291002.773815.48991612.129824.84091725.714816.61991736.843 840.475
1756.452 840.4441761.597820.59691930.586816.87191945.119817.18591982.216817.2261
2305.383819.89092486.653829.52812515.345820.95813681.015831.14513824.457844.6121
#Mann= 18 ,-1 , 0
       0    .052       0440.9651    .036       0469.2609    .057       0
 522.038    .026       0597.3799    .057       0 619.944    .036       0
666.6031    .082       0702.9349    .046       0897.2181    .082       0
916.7219    .037       0 956.879    .082       0 973.707    .057       0
1002.773    .046       01930.586    .052       01945.119    .046       0
1982.216    .052       02305.383    .046       02515.345    .052       0
Levee=-1,881.7833,815.0931,-1,975.1192,815.148,,
#XS Ineff= 2 ,-1
 466.472603.4034  815.34 1882.14    1905817.4736
Permanent Ineff=
       T       T
Bank Sta=881.7833,975.1192
XS Rating Curve= 0 ,0
Exp/Cntr=0.3,0.1

Type RM Length L Ch R = 1 ,51.80976,159.1571,106.6501,68.666
XS GIS Cut Line= 5
       561824.12       4829086.5       562470.34       4829616.7
       562519.09      4829749.18       562846.03      4829787.22
       564789.37      4831421.13
#Sta/Elev= 30
       0832.8349401.2851837.2122  479.49  815.08 539.859814.9819579.0789814.0562
624.8361  814.83 649.061816.1029 683.282813.9659843.5065814.7535844.0101814.8249
878.6162 812.502887.7278812.1161  918.99812.7449929.6095815.1066970.5149815.2659
985.8951 815.2941540.363824.26611618.021816.75491628.319824.80711746.772816.4489
 1749.18833.59441763.209820.67891943.721819.45511990.632 817.1311995.631817.1661
2319.007819.78882502.088 829.2882529.337  820.873721.855831.18413845.146846.1141
#Mann= 17 ,-1 , 0
       0    .052       0  479.49    .036       0 539.859    .057       0
579.0789    .026       0624.8361    .036       0 649.061    .082       0
 683.282    .046       0844.0101    .082       0878.6162    .037       0
  918.99    .082       0970.5149    .057       0985.8951    .046       0
1943.721    .052       01990.632    .046       01995.631    .052       0
2319.007    .046       02529.337    .052       0
Levee=-1,843.5065,814.8249,-1,929.6095,815.1083,,
#XS Ineff= 4 ,-1
566.7116 628.778815.0352  937.26   952.5817.4736   952.5 1043.94 819.912
 1897.38 1950.72817.4736
Permanent Ineff=
       T       T       T       T
Bank Sta=843.5065,929.6095
XS Rating Curve= 0 ,0
Exp/Cntr=0.5,0.3