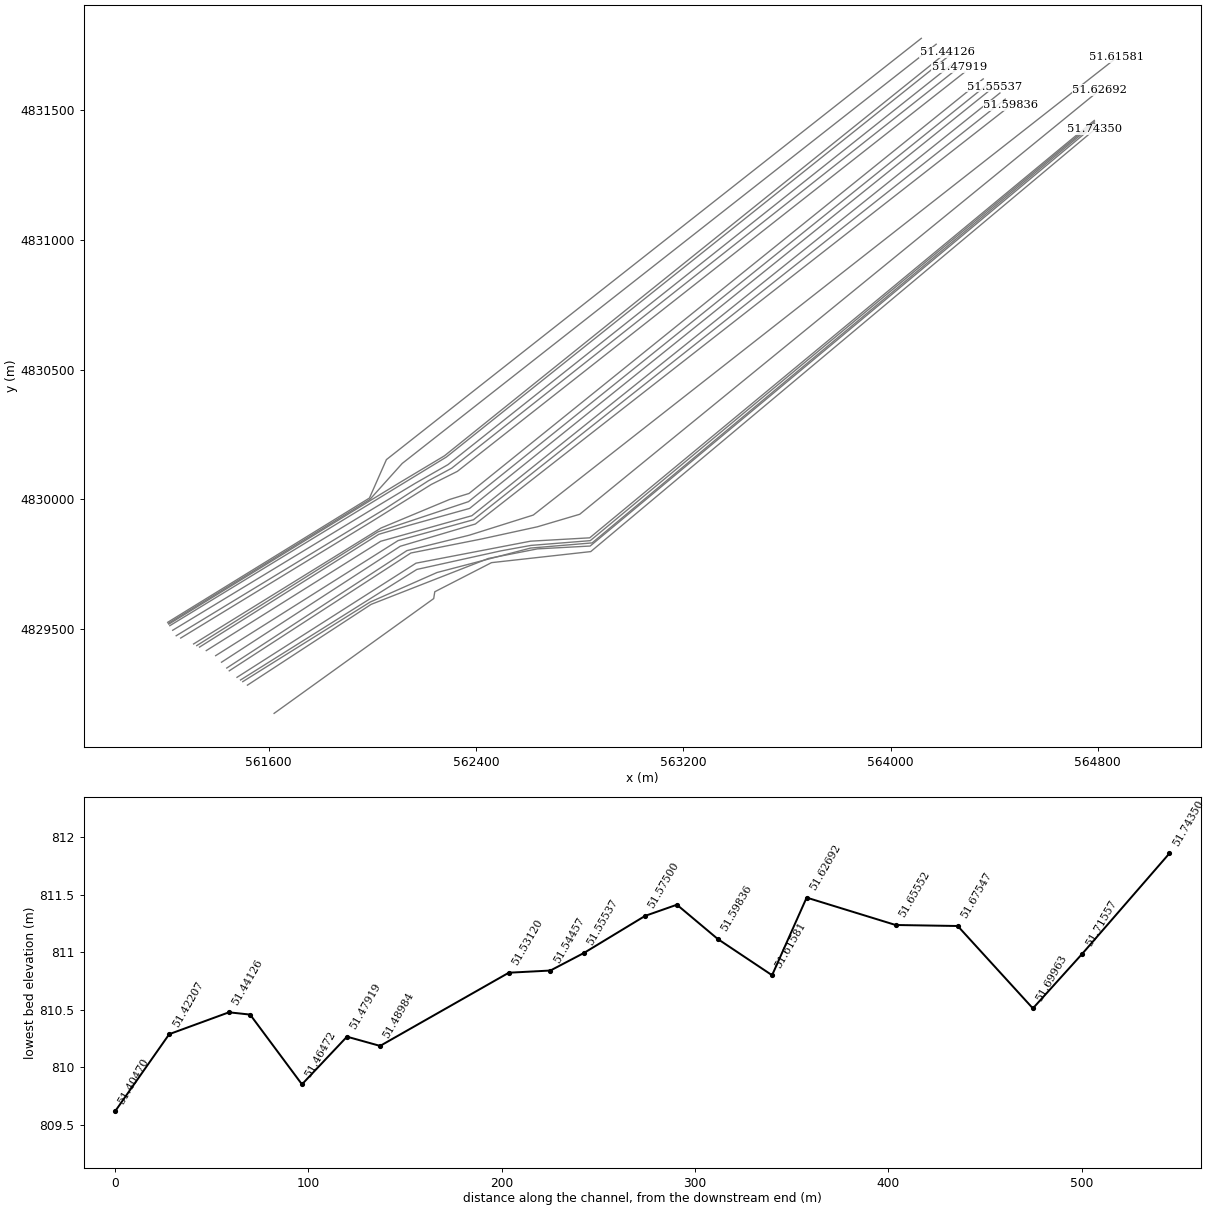
HEC-RAS study Boise2.prj: BoiseRiver_All_reaches

--- Boise2.g01 (geometry) --- (continued)

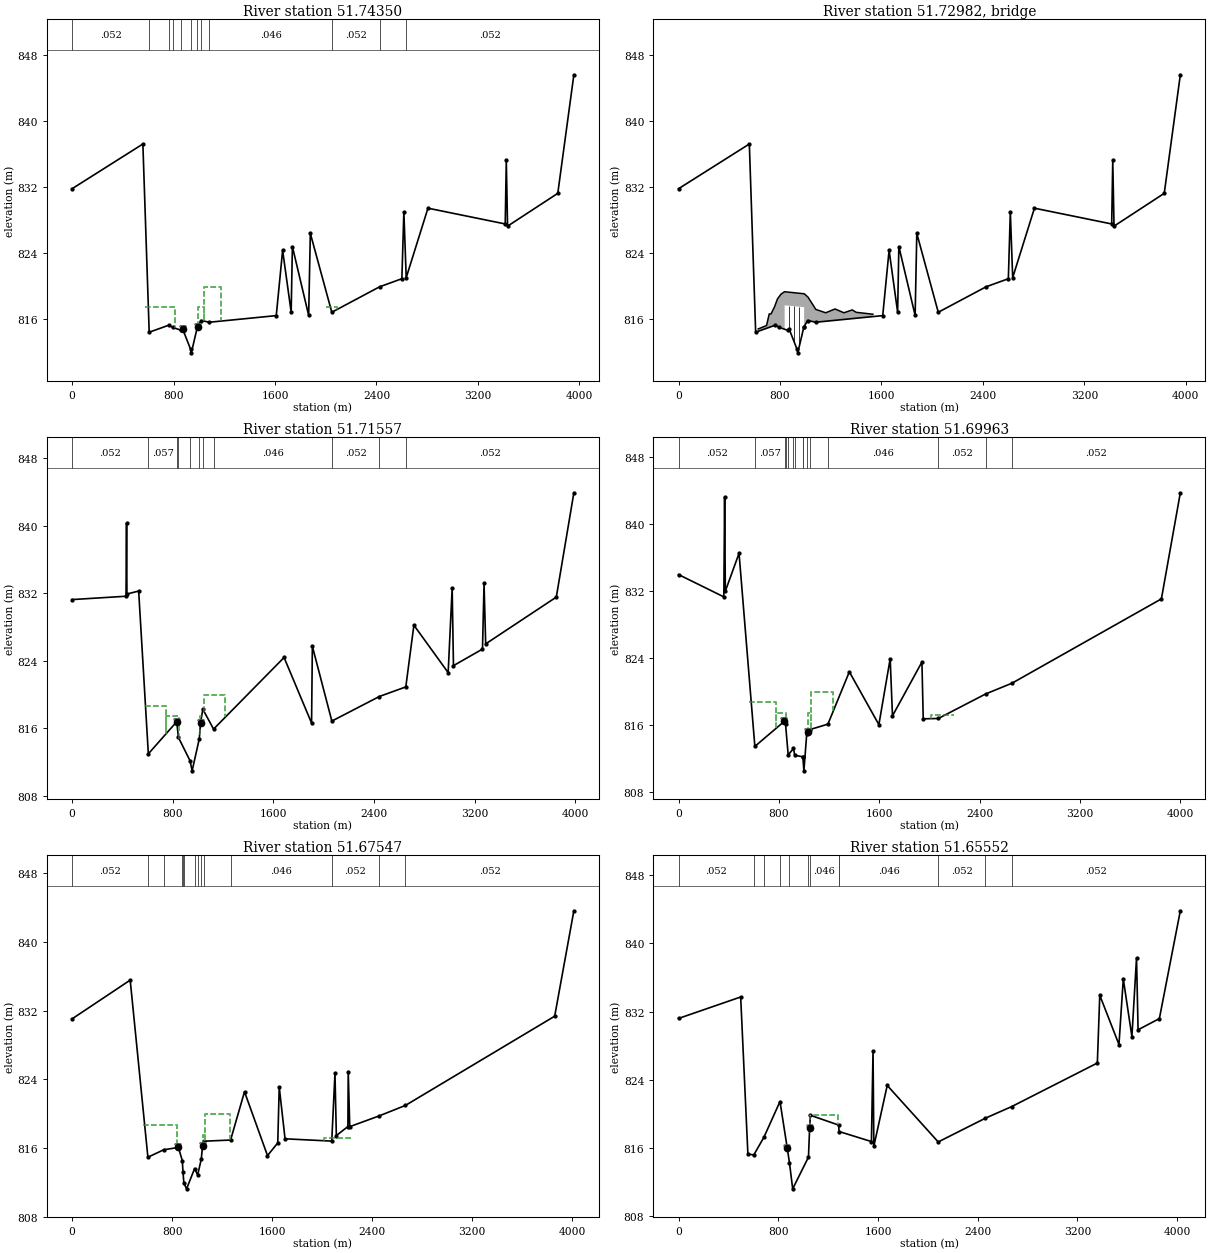
Type RM Length L Ch R = 1 ,51.74350,48.0999,44.9571,22.7939
BEGIN DESCRIPTION:
KOA Upstream
END DESCRIPTION:
XS GIS Cut Line= 6
       561620.88      4829173.27       562236.84      4829616.33
        562240.9      4829642.54       562459.86      4829754.97
       562842.91      4829797.66       564788.87      4831427.63
#Sta/Elev= 30
       0 831.794558.2558 837.228608.0949814.3619 763.976815.2238 792.858814.9481
862.4901814.5872872.6699814.7241934.1002 812.306940.2681 811.858987.5109814.9651
 990.533815.04651017.975815.78591082.069815.57591609.933  816.381660.146824.3069
1727.479816.80221737.128824.77291865.472816.40411878.565826.3701 2047.82816.7859
2424.071819.87512600.424 820.8632615.992 828.9812634.551820.99322806.016829.4309
3415.226 827.5153423.632 835.2273433.618 827.2473829.626 831.2353956.377845.6371
#Mann= 12 ,-1 , 0
       0    .052       0608.0949    .082       0 763.976    .057       0
 792.858    .046       0862.4901    .082       0934.1002    .037       0
987.5109    .082       01017.975    .057       01082.069    .046       0
 2047.82    .052       02424.071    .046       02634.551    .052       0
Levee=-1,872.6699,814.7274,-1,990.533,815.0535,,
#XS Ineff= 4 ,-1
   571.5  815.34817.4736 2004.06 2087.88817.4736   990.6 1036.32817.4736
 1036.32 1173.48 819.912
Permanent Ineff=
       T       T       T       T
Bank Sta=872.6699,990.533
XS Rating Curve= 0 ,0
Exp/Cntr=0.5,0.3

Type RM Length L Ch R = 3 ,51.72982,,,
BEGIN DESCRIPTION:
Greenbelt Pathway KOA Walk Bridge (RM 51.73)
END DESCRIPTION:
Bridge Culvert--1,0,-1,-1, 0
Deck Dist Width WeirC Skew NumUp NumDn MinLoCord MaxHiCord MaxSubmerge Is_Ogee
9.144,3.6576,1.44,0, 21, 21, , , 0.95, 0, 0,0,,
628.2598694.0052 714.948728.9139756.2576780.1112 807.973 835.405836.6242836.6242
990.2434990.2434991.46261021.0281082.7141160.2881233.9831303.7971369.7351400.766
1532.641
814.7609815.1815816.5836816.5836817.4249818.4063818.9915819.2811819.2811819.2811
819.0342819.0342819.0342818.6196817.1322816.7238817.1902816.7238817.0743816.7817
  816.55
  807.72  807.72  807.72  807.72  807.72  807.72 810.768 810.768 810.768817.6321
817.4066 810.768 810.768 810.768  807.72  807.72  807.72  807.72  807.72  807.72
  807.72
651.1199716.8652 737.808751.7739779.1176802.9712 830.833 858.265859.4842859.4842
1013.1031013.1031014.3231043.8881105.5741183.1481256.8431326.6571392.5951423.626
1555.501
814.7609815.1815816.5836816.5836817.4249818.4063818.9915819.2811819.2811819.2811
819.0342819.0342819.0342818.6196817.1322816.7238817.1902816.7238817.0743816.7817
  816.55
  807.72  807.72  807.72  807.72  807.72  807.72 810.768 810.768 810.768817.6321
817.4066 810.768 810.768 810.768  807.72  807.72  807.72  807.72  807.72  807.72
  807.72
Pier Skew, UpSta & Num, DnSta & Num=  ,873.505, 2 ,896.365, 2 , 0 , 0 , 0 ,,
  1.8288  1.8288
 810.768 818.388
  1.8288  1.8288
 810.768 818.388
Pier Skew, UpSta & Num, DnSta & Num=  ,913.129, 2 ,935.989, 2 , 0 , 0 , 0 ,,
  1.8288  1.8288
 810.768 818.388
  1.8288  1.8288
 810.768 818.388
Pier Skew, UpSta & Num, DnSta & Num=  ,952.753, 2 ,975.613, 2 , 0 , 0 , 0 ,,
  1.8288  1.8288
 810.768 818.388
  1.8288  1.8288
 810.768 818.388
BR Coef=-1 , 0 , 0 ,1.25, 0 ,,,0.8,-1,2,0,
WSPro=,,,, 1 ,,,, 0 ,,,, 0 ,,,,-1 ,-1 ,-1 , 0 , 0 , 0 , 0 , 0
BC Design=,, 0 ,, 0 ,,,,,,
BC Use User HTab Curves=0
BC User HTab FreeFlow(D)= 0

Type RM Length L Ch R = 1 ,51.71557,24.042,25.6611,10.077
BEGIN DESCRIPTION:
KOA Downstream
END DESCRIPTION:
XS GIS Cut Line= 6
       561517.96      4829282.17       561995.35      4829594.01
       562447.94      4829771.13       562637.03      4829808.09
       562840.65      4829819.09       564787.65      4831443.31
#Sta/Elev= 30
       0831.2552  428.75831.6511433.0711840.2668436.0761831.9102529.3141 832.267
 606.228813.0009831.9241 816.804832.3671816.8131845.1299814.9459937.6599812.1829
954.1929 810.9881011.444814.80111021.013816.68391039.363818.28011124.713815.9279
1684.984824.40111903.609816.64211909.874825.72822064.766 816.8742442.063819.7849
2652.648820.92212716.837828.22612989.307822.61193021.062832.62183031.394823.4361
3262.189825.39693274.457833.15893287.442826.01293848.865831.54723988.345843.8949
#Mann= 11 ,-1 , 0
       0    .052       0 606.228    .057       0832.3671    .036       0
845.1299    .082       0937.6599    .037       01011.444    .082       0
1039.363    .057       01124.713    .046       02064.766    .052       0
2442.063    .046       02652.648    .052       0
Levee=-1,831.9241,816.8214,-1,1021.013,816.7025,,
#XS Ineff= 5 ,-1
  579.12  746.76818.6928 2011.68 2164.08817.1688  746.76  853.44817.4736
 1013.46 1051.56817.4736 1051.56  1219.2 819.912
Permanent Ineff=
       T       T       F       F       T
Bank Sta=831.9241,1021.013
XS Rating Curve= 0 ,0
Exp/Cntr=0.5,0.3

Type RM Length L Ch R = 1 ,51.69963,33.542,38.8849,13.5919
XS GIS Cut Line= 6
       561499.91      4829295.71       561991.59      4829602.88
       562249.66      4829716.91       562610.79      4829811.25
       562848.22      4829831.17       564787.06       4831450.8
#Sta/Elev= 30
       0833.9481361.1029 831.285 367.441843.2061373.0389831.9659482.3521 836.487
608.4369813.4289844.7014816.4411844.8511 816.455 853.252 816.066 874.053812.4069
916.4559 813.183926.4561812.3591  990.86812.1929991.2599812.1411999.3819 810.511
1021.662814.85781035.933815.19311046.064815.43121190.872 816.0881361.582822.3361
 1597.12816.02891687.177 823.897 1705.57817.07891940.301823.50291950.708816.7219
2070.926 816.7642447.749819.68792658.962 820.9813849.392831.04514000.244 843.715
#Mann= 15 ,-1 , 0
       0    .052       0608.4369    .057       0844.8511    .036       0
 853.252    .082       0 874.053    .026       0916.4559    .082       0
926.4561    .037       0  990.86    .082       0991.2599    .037       0
1021.662    .082       01046.064    .057       01190.872    .046       0
2070.926    .052       02447.749    .046       02658.962    .052       0
Levee=-1,844.7014,816.4556,-1,1035.933,815.2029,,
#XS Ineff= 5 ,-1
  563.88  777.24818.6928 2011.68 2194.56817.1688  777.24  853.44817.4736
  1028.7 1059.18817.4736 1059.18 1234.44 819.912
Permanent Ineff=
       T       T       F       F       T
Bank Sta=844.7014,1035.933
XS Rating Curve= 0 ,0
Exp/Cntr=0.5,0.3

Type RM Length L Ch R = 1 ,51.67547,26.129,32.1159,20.2799
XS GIS Cut Line= 6
        561491.3      4829302.16       562171.69      4829728.74
       562496.66      4829800.55       562611.97      4829821.51
       562841.01      4829839.86       564786.64      4831456.27
#Sta/Elev= 30
       0831.0289464.8029835.5461606.2609814.9111 732.649815.7771850.3158816.0509
 881.506 814.504 886.722813.2381 893.944811.8961 915.664811.2271979.8079813.5941
1004.283812.84091033.172 814.688 1043.41816.23721052.431816.77721267.491 816.913
1378.764822.53911562.622815.09891644.726816.57811656.414823.09991702.942817.0569
2076.374816.78812102.145824.68482113.177817.43212205.541818.4879 2208.13824.8922
2220.297818.47212454.334819.71812665.382820.94593859.061831.34294012.317843.6252
#Mann= 14 ,-1 , 0
       0    .052       0606.2609    .057       0 732.649    .036       0
 881.506    .082       0 886.722    .026       0 893.944    .037       0
979.8079    .082       01004.283    .037       01033.172    .082       0
1052.431    .057       01267.491    .046       02076.374    .052       0
2454.334    .046       02665.382    .052       0
Levee=-1,850.3158,816.0806,-1,1043.41,816.233,,
#XS Ineff= 4 ,-1
 2011.68 2240.28817.1688  563.88 841.248818.6928 1043.94 1059.18817.4736
 1059.18 1264.92 819.912
Permanent Ineff=
       T       T       F       T
Bank Sta=850.3158,1043.41
XS Rating Curve= 0 ,0
Exp/Cntr=0.5,0.3

Type RM Length L Ch R = 1 ,51.65552,45.0991,46.044,51.955
BEGIN DESCRIPTION:
I-184 Connector Bridge Upstream and FEMA XS "BD"
PROJECT XS "BD"
END DESCRIPTION:
XS GIS Cut Line= 6
       561477.68      4829312.38       561918.54      4829593.52
       562168.56      4829752.95       562610.62      4829837.84
       562838.89      4829850.78       564786.23      4831461.53
#Sta/Elev= 30
       0 831.199  498.53833.7139 556.395 815.308 603.803815.2098685.1151 817.285
813.9261 821.465872.3833815.9846 890.119814.2698915.7125811.23581042.321814.9526
1051.472818.31571057.743819.85751284.088818.70591288.113  817.951547.307 816.775
1560.256827.42221566.755  816.231674.052823.3511 2083.12816.73112461.906819.5151
2673.237820.87793359.667 825.9763379.065833.91693533.129828.1419  3567.8835.8359
3636.837829.07493674.035838.28993686.446829.87193857.241 831.1824025.354843.8141
#Mann= 12 ,-1 , 0
       0    .052       0 603.803    .057       0685.1151    .036       0
813.9261    .046       0 890.119    .037       01042.321    .082       0
1057.743    .046       01284.088    .057       01288.113    .046       0
 2083.12    .052       02461.906    .046       02673.237    .052       0
Levee=-1,872.3833,815.9587,-1,1051.472,818.2996,,
#XS Ineff= 3 ,-1
 2011.68 2270.76817.1688   533.4  807.72818.6928 1051.56 1280.16 819.912
Permanent Ineff=
       T       T       T
Bank Sta=872.3833,1051.472
XS Rating Curve= 0 ,0
Exp/Cntr=0.5,0.3

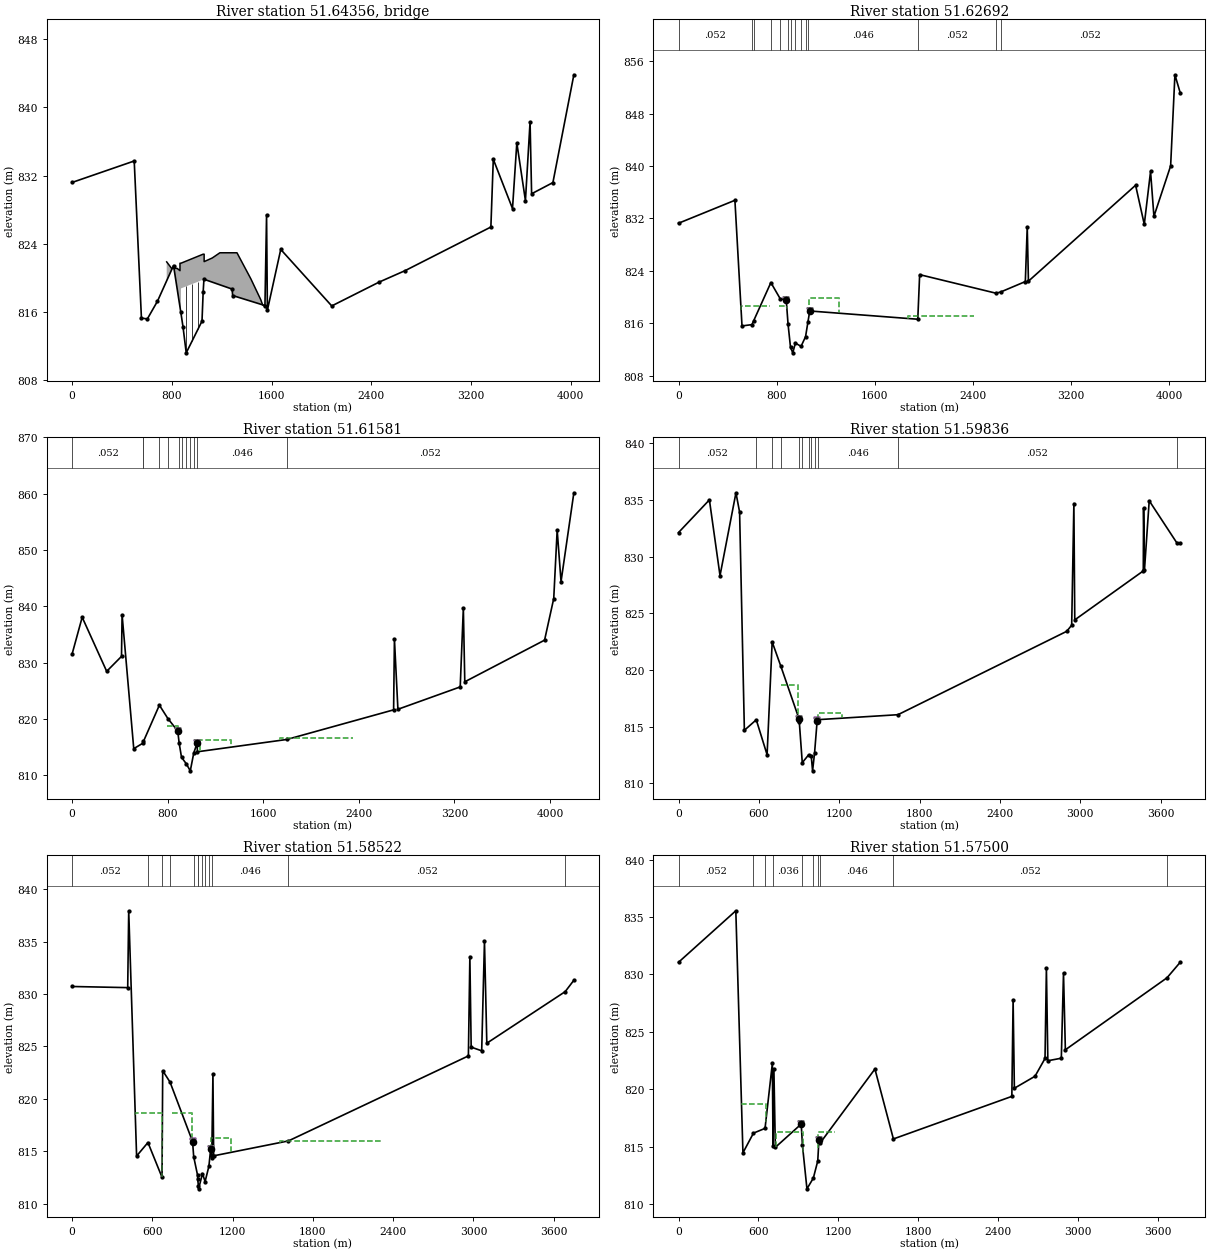
Type RM Length L Ch R = 3 ,51.64356,,,
BEGIN DESCRIPTION:
I-184 Connector Bridge
END DESCRIPTION:
Bridge Culvert--1,0,-1,-1, 0
Deck Dist Width WeirC Skew NumUp NumDn MinLoCord MaxHiCord MaxSubmerge Is_Ogee
1.524,37.7952,1.44,0, 19, 19, , , 0.95, 0, 0,0,,
 758.952 798.576  815.34 842.772 865.632 865.632873.5568873.5568 1051.56 1051.56
1059.4851059.4851124.7121185.6721322.8321434.0841513.3321528.5721566.672
821.8932821.1312821.1312821.1312 820.863821.7377821.7377821.7377822.7954822.7954
822.7954821.9237822.3504  822.96  822.96 819.912817.4736 816.864816.4068
  807.72  807.72  807.72  807.72  807.72 809.244 809.244818.7842819.8083 809.244
 809.244  807.72  807.72  807.72  807.72  807.72  807.72  807.72  807.72
  777.24 816.864 833.628  861.06  883.92  883.92891.8448891.84481069.8481069.848
1077.7731077.773    1143 1203.96 1341.121452.372 1531.62 1546.86 1584.96
821.8932821.1312821.1312821.1312 820.863821.7377821.7377821.7377822.7954822.7954
822.7954821.9237822.3504  822.96  822.96 819.912817.4736 816.864816.4068
  807.72  807.72  807.72  807.72  807.72 809.244 809.244818.7842819.8083 809.244
 809.244  807.72  807.72  807.72  807.72  807.72  807.72  807.72  807.72
Pier Skew, UpSta & Num, DnSta & Num=  ,914.4, 2 ,932.688, 2 , 0 , 0 , 0 ,,
    .762    .762
 810.768 819.912
    .762    .762
 810.768 819.912
Pier Skew, UpSta & Num, DnSta & Num=  ,961.644, 2 ,979.932, 2 , 0 , 0 , 0 ,,
    .762    .762
 810.768 819.912
    .762    .762
 810.768 819.912
Pier Skew, UpSta & Num, DnSta & Num=  ,1010.412, 2 ,1028.7, 2 , 0 , 0 , 0 ,,
    .762    .762
 810.768 819.912
    .762    .762
 810.768 819.912
BR Coef=-1 , 0 , 0 ,1.25, 0 ,,,0.8,-1,2,0,
WSPro=,,,, 1 ,,,, 0 ,,,, 0 ,,,,-1 ,-1 ,-1 , 0 , 0 , 0 , 0 , 0
BC Design=,, 0 ,, 0 ,,,,,,
BC Use User HTab Curves=0
BC User HTab FreeFlow(D)= 0

Type RM Length L Ch R = 1 ,51.62692,15.4592,17.878,29.07
BEGIN DESCRIPTION:
I-184 Connector Bridge Downstream
END DESCRIPTION:
XS GIS Cut Line= 6
       561447.78      4829337.49       562148.73      4829792.21
       562420.37      4829846.06       562636.57      4829893.23
       562800.31      4829941.66       564807.71      4831579.32
#Sta/Elev= 30
       0831.2579 459.775834.7609 517.665 815.582 598.711815.7802611.8149816.3309
 753.098822.1971829.6769819.7151 878.269819.5928893.1521 815.871 913.218 812.317
 931.738811.4739 952.941812.9589999.2161812.46511036.073 813.9441055.727816.2252
1070.186817.86461951.339816.60491966.559 823.4122588.953 820.5782626.219820.7538
2828.488822.35312844.024830.71292853.773822.41323727.777 837.0573798.668  831.09
3849.776839.15893877.297 832.3074013.527840.01114048.469 853.9214092.614851.1119
#Mann= 14 ,-1 , 0
       0    .052       0 598.711    .057       0611.8149    .036       0
 753.098    .046       0829.6769    .036       0893.1521    .082       0
 913.218    .037       0 952.941    .082       0999.2161    .037       0
1036.073    .082       01055.727    .046       01951.339    .052       0
2588.953    .046       02626.219    .052       0
Levee=-1,878.269,819.5797,-1,1070.186,817.9064,,
#XS Ineff= 4 ,-1
 1874.52 2407.92817.1688  510.54  746.76818.6928  822.96  883.92818.6928
  1066.8 1310.64 819.912
Permanent Ineff=
       T       T       F       F
Bank Sta=878.269,1070.186
XS Rating Curve= 0 ,0
Exp/Cntr=0.5,0.3

Type RM Length L Ch R = 1 ,51.61581,26.4829,28.0809,40.835
XS GIS Cut Line= 5
       561438.14      4829348.25        562133.4      4829801.41
        562373.8      4829860.82       562621.04      4829938.62
       564873.32      4831704.53
#Sta/Elev= 30
       0831.5178 84.6149 838.079 289.738828.4711413.6849831.1271418.5691838.4941
516.1431814.7371594.5441815.7369 597.063 816.013730.5839 822.465801.5429  820.09
884.2858817.8651 896.015815.7271 915.749813.2079955.2179812.0662989.2329810.7991
1018.199813.95981046.232815.7156 1048.85814.18511796.649816.36812690.491821.6298
2697.376 834.2042726.489821.73113247.766825.70513274.061839.70573286.067826.6121
3953.628834.00594030.389841.40414059.113 853.5544091.461844.41224198.757 860.181
#Mann= 12 ,-1 , 0
       0    .052       0594.5441    .057       0 597.063    .036       0
730.5839    .046       0801.5429    .036       0 896.015    .082       0
 915.749    .037       0955.2179    .082       0989.2329    .037       0
1018.199    .082       0 1048.85    .046       01796.649    .052       0
Levee=-1,884.2858,817.8546,-1,1046.232,815.721,,
#XS Ineff= 4 ,-1
 1737.36 2346.96816.5592   495.3  731.52818.6928  792.48  883.92818.6928
  1066.8 1325.88816.2544
Permanent Ineff=
       T       T       F       T
Bank Sta=884.2858,1046.232
XS Rating Curve= 0 ,0
Exp/Cntr=0.5,0.3

Type RM Length L Ch R = 1 ,51.59836,21.8859,21.1559,22.6399
XS GIS Cut Line= 4
       561417.99      4829370.75        562107.6      4829818.18
       562397.73      4829904.18       564463.23       4831519.5
#Sta/Elev= 30
       0832.1229 230.448835.0029 309.689 828.326428.7219835.6281455.9521 833.924
491.6311 814.688580.3761 815.614661.1871812.5361699.1481822.4781763.5929820.3478
901.0406815.6529901.8489815.4019923.9548 811.832971.1641812.5231991.0222812.4051
1000.845 811.1141015.751 812.6911035.119815.54791042.738815.62711638.465 816.063
2898.291 823.4132935.593823.95312951.986834.67992958.611824.42223470.212828.7399
3472.318 834.2693478.911828.80213514.417834.92613719.051831.24113746.775831.1868
#Mann= 12 ,-1 , 0
       0    .052       0580.3761    .036       0699.1481    .046       0
763.5929    .036       0901.8489    .082       0923.9548    .037       0
971.1641    .082       0991.0222    .037       01015.751    .082       0
1042.738    .046       01638.465    .052       03719.051    .036       0
Levee=-1,901.0406,815.6539,-1,1035.119,815.5778,,
#XS Ineff= 4 ,-1
 1569.72 2316.48815.9496  480.06  701.04818.6928     762  891.54818.6928
 1043.94  1219.2816.2544
Permanent Ineff=
       T       T       F       T
Bank Sta=901.0406,1035.119
XS Rating Curve= 0 ,0
Exp/Cntr=0.3,0.1

Type RM Length L Ch R = 1 ,51.58522,16.5448,16.461,17.1139
XS GIS Cut Line= 4
       561395.35      4829396.02       562099.42      4829840.13
       562390.14       4829920.5       564442.54      4831543.79
#Sta/Elev= 30
       0830.7129415.8859 830.605423.3958837.9352482.3539814.5399 567.123815.8301
672.5211 812.509677.4531 822.682 732.158 821.596 900.623 815.925909.1962814.4731
938.0781812.7089939.2031 812.309944.8291811.6501945.7371 811.412974.8361 812.866
994.3402812.10211022.846 813.5711035.643815.17611044.226814.33911052.928822.3668
1058.396 814.5611617.725815.98582962.421 824.0922973.476833.56492983.236824.9299
3061.871 824.5773082.671835.04193100.157825.30213685.922830.22193750.811831.3069
#Mann= 14 ,-1 , 0
       0    .052       0 567.123    .036       0672.5211    .046       0
 732.158    .036       0909.1962    .082       0938.0781    .037       0
939.2031    .082       0944.8291    .037       0974.8361    .082       0
994.3402    .037       01022.846    .082       01044.226    .046       0
1617.725    .052       03685.922    .036       0
Levee=-1,900.623,815.9313,-1,1035.643,815.1693,,
#XS Ineff= 4 ,-1
  472.44  670.56818.6928  746.76  899.16818.6928 1554.48 2316.48815.9496
 1036.32 1188.72816.2544
Permanent Ineff=
       T       T       T       T
Bank Sta=900.623,1035.643
XS Rating Curve= 0 ,0
Exp/Cntr=0.5,0.3

Type RM Length L Ch R = 1 ,51.57500,32.4841,31.5959,31.865
BEGIN DESCRIPTION:
Fairview Bridge Upstream and FEMA XS "BC"
PROJECT XS "BC"
END DESCRIPTION:
XS GIS Cut Line= 6
        561359.1      4829415.52       561753.64      4829662.79
       562032.38      4829837.49       562384.11       4829936.1
       562889.97      4830341.02       564422.13      4831567.45
#Sta/Elev= 30
       0831.0601 430.423 835.547 483.909814.4531562.9211816.1691 650.018 816.586
 705.045822.2501 709.967815.0269716.3909821.7941 727.433814.9318921.9713 816.961
931.0728815.1038964.8712811.3148 1012.92812.25051046.083813.74621054.937815.5767
1064.945815.32531475.619 821.7561614.487815.66312504.434819.37192513.977827.7999
2523.379  820.082678.584 821.1272753.707 822.6762764.109830.56812775.028822.4781
2876.195822.69912892.599830.13412906.585823.43213670.112 829.7043770.406831.0701
#Mann= 10 ,-1 , 0
       0    .052       0562.9211    .036       0 650.018    .046       0
 709.967    .036       0931.0728    .082       0 1012.92    .037       0
1046.083    .082       01064.945    .046       01614.487    .052       0
3670.112    .036       0
Levee=-1,921.9713,816.9646,-1,1054.937,815.5747,,
#XS Ineff= 4 ,-1
  472.44  655.32818.6928 1546.86 2331.72815.6448  731.52  937.26816.2544
 1051.56 1173.48816.2544
Permanent Ineff=
       T       T       T       T
Bank Sta=921.9713,1054.937
XS Rating Curve= 0 ,0
Exp/Cntr=0.5,0.3

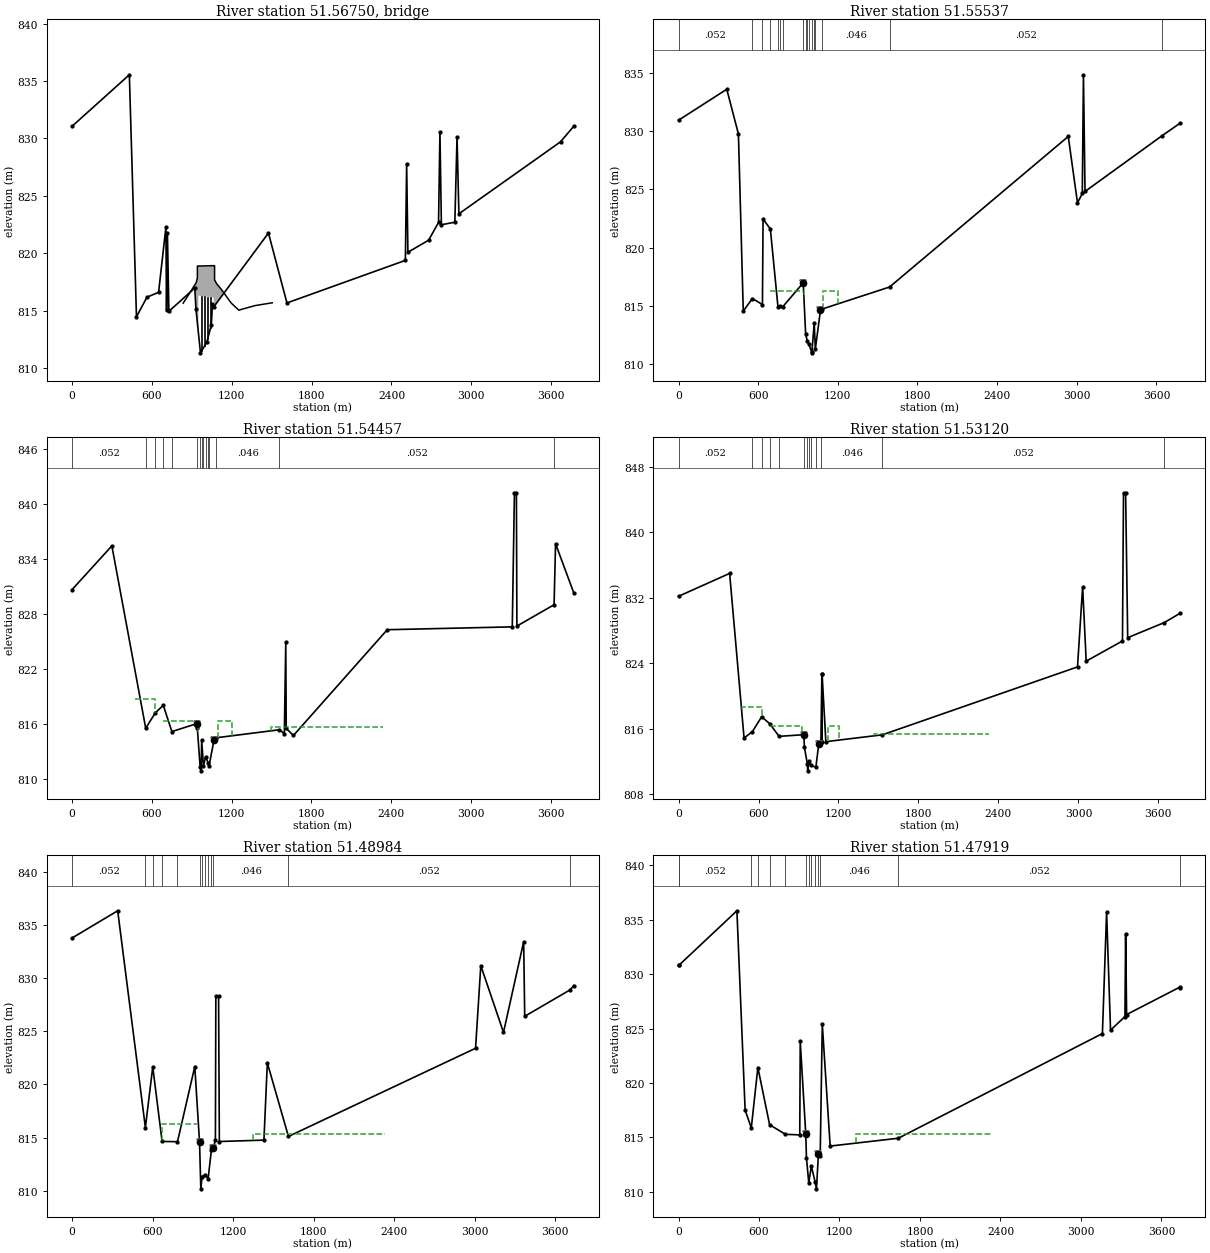
Type RM Length L Ch R = 3 ,51.56750,,,
BEGIN DESCRIPTION:
Fairview Avenue Bridge
END DESCRIPTION:
Bridge Culvert--1,0,-1,-1, 0
Deck Dist Width WeirC Skew NumUp NumDn MinLoCord MaxHiCord MaxSubmerge Is_Ogee
1.524,24.384,1.44,0, 17, 17, , , 0.95, 0, 0,0,,
 835.152 902.208 932.688941.5272941.5272948.8424948.84241063.4471063.4471070.762
1070.915 1085.88 1120.14 1196.341252.7281374.6481504.188
815.6448 816.864 817.434817.8333818.8818818.8818818.8818818.9122818.9122818.9122
817.6747817.3486 816.864815.6448815.0352815.4315815.6753
  807.72  807.72  807.72  807.72 810.768 810.768816.3032816.1447 810.768 810.768
  807.72  807.72  807.72  807.72  807.72  807.72  807.72
 835.152 902.208 932.688941.5272941.5272948.8424948.84241063.4471063.4471070.762
1070.915 1085.88 1120.14 1196.341252.7281374.6481504.188
815.6448 816.864 817.434817.8333818.8818818.8818818.8818818.9122818.9122818.9122
817.6747817.3486 816.864815.6448815.0352815.4315815.6753
  807.72  807.72  807.72  807.72 810.768 810.768816.3032816.1447 810.768 810.768
  807.72  807.72  807.72  807.72  807.72  807.72  807.72
Pier Skew, UpSta & Num, DnSta & Num=  ,972.312, 2 ,972.312, 2 , 0 , 0 , 0 ,,
  1.8288  1.8288
 810.768 816.864
  1.8288  1.8288
 810.768 816.864
Pier Skew, UpSta & Num, DnSta & Num=  ,995.172, 2 ,995.172, 2 , 0 , 0 , 0 ,,
  1.8288  1.8288
 810.768 816.864
  1.8288  1.8288
 810.768 816.864
Pier Skew, UpSta & Num, DnSta & Num=  ,1018.032, 2 ,1018.032, 2 , 0 , 0 , 0 ,,
  1.8288  1.8288
 810.768 816.864
  1.8288  1.8288
 810.768 816.864
Pier Skew, UpSta & Num, DnSta & Num=  ,1040.892, 2 ,1040.892, 2 , 0 , 0 , 0 ,,
  1.8288  1.8288
 810.768 816.864
  1.8288  1.8288
 810.768 816.864
BR Coef=-1 , 0 , 0 ,1.25, 0 ,,,0.8,-1,2,0,
WSPro=,,,, 1 ,,,, 0 ,,,, 0 ,,,,-1 ,-1 ,-1 , 0 , 0 , 0 , 0 , 0
BC Design=,, 0 ,, 0 ,,,,,,
BC Use User HTab Curves=0
BC User HTab FreeFlow(D)= 0

Type RM Length L Ch R = 1 ,51.55537,15.5049,17.3879,23.4099
BEGIN DESCRIPTION:
Fairview Bridge Downstream
END DESCRIPTION:
XS GIS Cut Line= 5
       561333.15      4829429.13         562025.      4829864.41
       562140.84       4829898.7       562375.53      4829964.35
       564400.55      4831592.23
#Sta/Elev= 30
       0830.9241 363.407 833.574451.1491829.7382487.6291 814.571556.4319815.6478
632.0339815.1309 636.783 822.458691.7592821.6039 749.217814.9042 761.313815.0251
785.8838814.9498939.3561 816.993  939.36816.9927957.5009812.5999969.9751 812.007
981.6858 811.7191002.484 811.0851004.383 810.9931022.141813.57011030.457811.3179
1069.403814.6623 1081.11814.74411589.535816.6312 2935.87829.53213005.485823.8391
3041.617824.64593050.292834.81583062.158824.81993642.131829.59223780.105830.6812
#Mann= 17 ,-1 , 0
       0    .052       0556.4319    .036       0632.0339    .046       0
691.7592    .036       0 749.217    .046       0 761.313    .036       0
785.8838    .046       0939.3561    .082       0957.5009    .037       0
969.9751    .082       0981.6858    .037       01002.484    .082       0
1022.141    .037       01030.457    .082       0 1081.11    .046       0
1589.535    .052       03642.131    .036       0
Levee=-1,939.36,817.0164,-1,1069.403,814.6633,,
#XS Ineff= 4 ,-1
  472.44  640.08818.6928    1524 2339.34815.6448   685.8  944.88816.2544
 1089.66 1203.96816.2544
Permanent Ineff=
       T       T       F       F
Bank Sta=939.36,1069.403
XS Rating Curve= 0 ,0
Exp/Cntr=0.5,0.3

Type RM Length L Ch R = 1 ,51.54457,19.221,21.5189,30.9979
XS GIS Cut Line= 4
       561322.29      4829434.83       562022.03      4829874.02
       562371.11      4829990.37       564381.21      4831606.31
#Sta/Elev= 30
       0 830.665 299.231835.4479553.9082815.4912625.9769817.1902 685.971818.0101
750.4929815.1348938.7078816.0065942.1719815.4851963.3021811.2121970.7441  810.84
974.6221 814.207987.8281811.35991004.053 812.3841024.051811.69181030.466811.4135
 1066.69814.16611081.781 814.4541559.471815.33391596.114814.91111606.943824.9119
1610.403815.47321664.895814.71312370.107826.27813310.134826.58983326.344841.2571
3341.208841.23273344.799826.67613624.554  829.013635.526835.68393773.217830.2831
#Mann= 15 ,-1 , 0
       0    .052       0553.9082    .036       0625.9769    .046       0
 685.971    .036       0750.4929    .046       0942.1719    .082       0
963.3021    .037       0974.6221    .082       0987.8281    .037       0
1004.053    .082       01024.051    .037       01030.466    .082       0
1081.781    .046       01559.471    .052       03624.554    .036       0
Levee=-1,938.7078,816.0075,-1,1066.69,814.1665,,
#XS Ineff= 4 ,-1
  472.44  624.84818.6928   685.8  944.88816.2544 1097.28 1203.96816.2544
 1493.52 2339.34815.6448
Permanent Ineff=
       T       F       F       T
Bank Sta=938.7078,1066.69
XS Rating Curve= 0 ,0
Exp/Cntr=0.5,0.3

Type RM Length L Ch R = 1 ,51.53120,61.4879,66.582,78.913
XS GIS Cut Line= 5
       561310.19      4829441.18       562033.73      4829888.68
       562297.67      4829998.68       562373.22      4830021.99
       564357.51      4831621.89
#Sta/Elev= 30
       0 832.183 383.325834.9841491.6058 814.845553.4102 815.603 623.433 817.433
683.6679   816.6754.4449815.0394939.7441815.2449944.5621813.6959966.7728811.6388
969.1951 810.821979.1971811.9711 993.132 811.4831030.397811.2599 1051.56814.0568
 1068.42 814.4541075.383822.72721076.087814.33021077.068822.68691105.193 814.392
1529.595815.22992993.249 823.5413031.718833.33113058.445824.2441 3330.55826.7151
3338.435844.85083354.172844.82333369.863 827.1193645.353828.97313764.695830.1219
#Mann= 13 ,-1 , 0
       0    .052       0553.4102    .036       0 623.433    .046       0
683.6679    .036       0754.4449    .046       0944.5621    .082       0
966.7728    .037       0979.1971    .082       0 993.132    .037       0
1030.397    .082       0 1068.42    .046       01529.595    .052       0
3645.353    .036       0
Levee=-1,939.7441,815.2363,-1,1051.56,814.0599,,
#XS Ineff= 4 ,-1
 1463.04 2331.72  815.34  472.44  624.84818.6928   685.8  929.64816.2544
 1120.14 1203.96816.2544
Permanent Ineff=
       T       T       F       F
Bank Sta=939.7441,1051.56
XS Rating Curve= 0 ,0
Exp/Cntr=0.3,0.1

Type RM Length L Ch R = 1 ,51.48984,16.4351,17.1301,17.629
XS GIS Cut Line= 5
       561260.44        4829464.       561994.48      4829911.68
       562227.35      4830056.68       562328.01      4830107.17
       564286.42      4831648.24
#Sta/Elev= 30
       0 833.774339.9309 836.335546.2339815.9511601.1939821.6509670.7349814.6411
 785.515 814.618914.3448 821.685949.5983814.6076 949.648814.6052959.3141810.1849
968.3411 811.338991.8951811.5291 1013.58811.12921038.256813.85411051.517814.0587
1053.211814.08911067.944 814.7641071.214828.2849 1091.62828.28491097.373814.6359
1429.591814.76611454.849822.03311612.157 815.1123006.337823.40413045.407831.1771
3214.467824.89793364.779833.42113372.606826.40913708.483828.88263738.768829.3019
#Mann= 13 ,-1 , 0
       0    .052       0546.2339    .036       0601.1939    .046       0
670.7349    .036       0 785.515    .046       0 949.648    .082       0
968.3411    .037       0991.8951    .082       0 1013.58    .037       0
1038.256    .082       01053.211    .046       01612.157    .052       0
3708.483    .036       0
Levee=-1,949.5983,814.6146,-1,1051.517,814.0568,,
#XS Ineff= 4 ,-1
 1348.74 2331.72  815.34  480.06  594.36818.6928  670.56  929.64816.2544
  1066.8 1226.82814.1208
Permanent Ineff=
       T       T       F       T
Bank Sta=949.5983,1051.517
XS Rating Curve= 0 ,0
Exp/Cntr=0.3,0.1

Type RM Length L Ch R = 1 ,51.47919,26.8599,23.2931,22.9609
XS GIS Cut Line= 5
         561243.      4829472.83       562046.06      4829960.69
       562216.67      4830071.16        562306.3      4830119.51
       564265.02       4831667.2
#Sta/Elev= 30
       0 830.808  2.2449 830.808435.2309835.8241496.4921 817.502542.4599 815.871
 591.468821.4141679.0099 816.159797.2291815.2751903.8052815.2251 907.374823.8119
948.6473 815.288953.6071813.1299 970.816810.8329990.2699812.35111018.328810.8951
 1028.34810.2651 1043.02813.49111043.044813.48951056.105813.25791071.796825.3923
 1130.49814.19611637.855814.91483160.233824.53883191.402 835.6973220.782  824.85
3328.178826.10193333.293833.67713340.742 826.2853736.988 828.8043741.103828.7548
#Mann= 14 ,-1 , 0
       0    .046       0  2.2449    .052       0542.4599    .036       0
 591.468    .046       0679.0099    .036       0797.2291    .046       0
953.6071    .082       0 970.816    .037       0990.2699    .082       0
1018.328    .037       0 1043.02    .082       01056.105    .046       0
1637.855    .052       03736.988    .036       0
Levee=-1,948.6473,815.3034,-1,1043.044,813.4929,,
#XS Ineff= 4 ,-1
  480.06  586.74818.6928  670.56  929.64816.2544 1325.88 2339.34  815.34
 1059.18 1234.44814.1208
Permanent Ineff=
       T       T       T       T
Bank Sta=948.6473,1043.044
XS Rating Curve= 0 ,0
Exp/Cntr=0.55,0.35

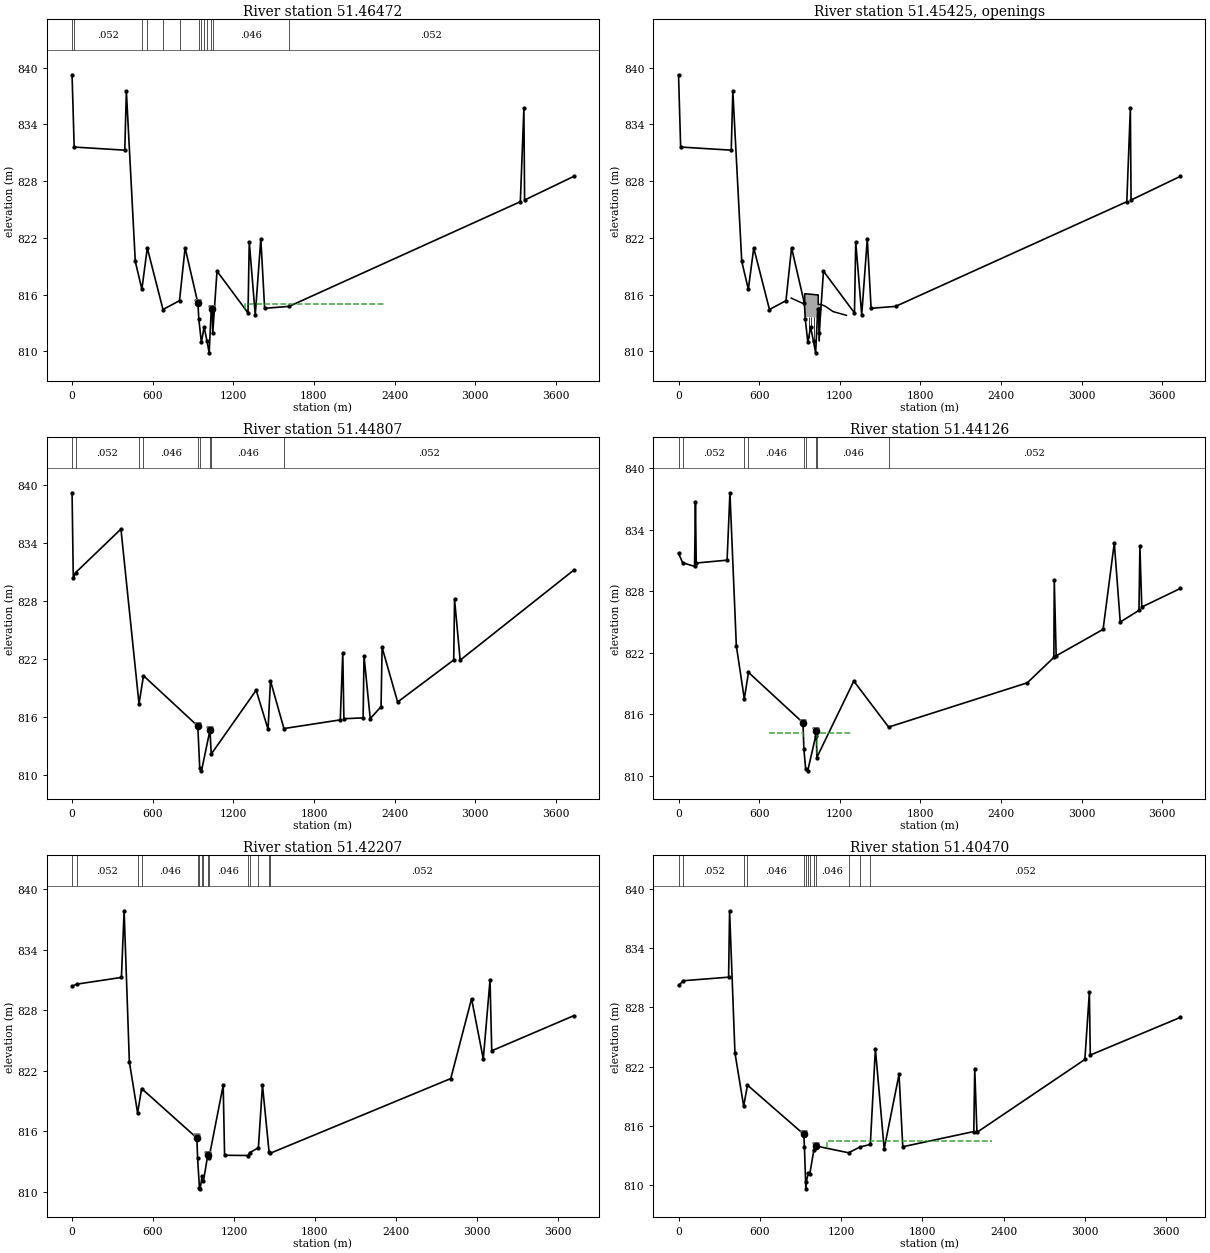
Type RM Length L Ch R = 1 ,51.46472,25.1969,26.812,26.958
BEGIN DESCRIPTION:
Main Street Bridge Upstream
END DESCRIPTION:
XS GIS Cut Line= 5
        561229.6      4829494.05       562031.27      4829980.32
       562166.49      4830061.69       562291.89      4830133.24
       564245.32      4831684.65
#Sta/Elev= 30
       0839.2571 15.6841831.6139 392.266831.2841 404.116837.5029470.4521819.5188
 519.449816.5759559.7801820.9401676.6652814.4341799.5251 815.368 841.198 820.959
936.7327815.0829943.2929813.4061962.3429810.9591982.8818812.57911004.541811.0521
1020.366809.8508 1035.91 814.4571043.751814.53051047.113 811.982  1078.6818.4901
 1309.32814.0739 1318.68821.59391363.243 813.8581404.702 821.9061433.071 814.561
1615.108 814.7633336.018825.83483362.468835.70623367.753 826.0113734.355828.5159
#Mann= 13 ,-1 , 0
       0    .046       0 15.6841    .052       0 519.449    .036       0
559.7801    .046       0676.6652    .036       0799.5251    .046       0
943.2929    .082       0962.3429    .037       0982.8818    .082       0
1004.541    .037       0 1035.91    .082       01047.113    .046       0
1615.108    .052       0
Levee=-1,936.7327,815.0688,-1,1043.751,814.5292,,
#XS Ineff= 4 ,-1
   457.2  556.26818.6928 1287.78 2331.72815.0352  670.56  937.26814.1208
 1036.32  1219.2814.1208
Permanent Ineff=
       T       T       T       T
Bank Sta=936.7327,1043.751
XS Rating Curve= 0 ,0
Exp/Cntr=0.55,0.35

Type RM Length L Ch R = 4 ,51.45425,,,
BEGIN DESCRIPTION:
Main Street Bridge
END DESCRIPTION:
Bridge Culvert--1,0,-1,-1, 0
Deck Dist Width WeirC Skew NumUp NumDn MinLoCord MaxHiCord MaxSubmerge Is_Ogee
6.096,17.6784,1.44,0, 14, 14, , , 0.95, 0, 0,0,,
   838.2  922.02 938.784 938.784 946.404 946.4041031.7481031.7481039.3681039.368
 1059.181094.5061149.736 1249.68
815.6448815.0961815.0961816.0989816.0989816.0989815.9801815.9801815.9801814.9742
814.9742814.7609814.2123 813.816
  807.72  807.72  807.72809.5488809.5488813.6575813.5691809.5488809.5488809.5488
809.5488809.5488809.5488809.5488
  822.96  906.78 923.544 923.544 931.164 931.1641016.5081016.5081024.1281024.128
 1043.941079.2661134.496 1234.44
815.6448815.0961815.0961816.0989816.0989816.0989815.9801815.9801815.9801814.9742
814.9742814.7609814.2123 813.816
  807.72  807.72  807.72809.5488809.5488813.6575813.5691809.5488809.5488809.5488
809.5488809.5488809.5488809.5488
Pier Skew, UpSta & Num, DnSta & Num=  ,967.74, 2 ,952.5, 2 , 0 , 0 , 0 ,,
   .6096   .6096
 809.244 813.816
   .6096   .6096
 809.244 813.816
Pier Skew, UpSta & Num, DnSta & Num=  ,989.076, 2 ,973.836, 2 , 0 , 0 , 0 ,,
   .6096   .6096
 809.244 813.816
   .6096   .6096
 809.244 813.816
Pier Skew, UpSta & Num, DnSta & Num=  ,1010.412, 2 ,995.172, 2 , 0 , 0 , 0 ,,
   .6096   .6096
 809.244 813.816
   .6096   .6096
 809.244 813.816
BR Coef=-1 , 0 , 0 ,1.25, 0 ,,,0.8,0,2,0,
WSPro=,,,, 1 ,,,, 0 ,,,, 0 ,,,,-1 ,-1 ,-1 , 0 , 0 , 0 , 0 , 0
Culvert=1,3.048,,17.6784,0.02,1,1,1,1,811.0728,1047.598,811.0728,1032.358,Culvert #1  , 0 ,6.096
Culvert Bottom n=0.02
BC Mult= 3 ,0,1043.94,0,1025.652
BC Mult= 2 ,1043.94,3734.355,1025.652,3733.379
BC Design=,, 0 ,, 0 ,,,,,,
BC Use User HTab Curves=0
BC User HTab FreeFlow(D)= 0

Type RM Length L Ch R = 1 ,51.44807,10.4059,10.9609,11.604
BEGIN DESCRIPTION:
Main Street Bridge Downstream and FEMA XS "BB"
PROJECT XS "BB"
END DESCRIPTION:
XS GIS Cut Line= 5
       561218.45       4829511.7       561584.74      4829735.07
       562285.81      4830162.58        562539.1      4830364.81
       564226.42       4831711.9
#Sta/Elev= 30
       0839.2031   9.084830.4059  27.254830.9589363.6029 835.451498.0331817.3901
  531.26 820.293935.0319815.0894935.5851815.0964949.6797810.7534962.9288810.4571
1025.899814.65621026.105814.69231035.331 812.1861369.697 818.7941458.112814.7499
1476.138  819.771576.232814.82891995.555815.72592014.101822.6658 2022.38815.8442
2165.446815.93192172.098822.33312218.322 815.859 2298.84 817.0852306.694823.2081
2422.279817.57292839.387821.91822845.733 828.1832887.508 821.9023733.379 831.213
#Mann= 9 ,-1 , 0
       0    .046       0  27.254    .052       0498.0331    .036       0
  531.26    .046       0935.5851    .082       0949.6797    .037       0
1026.105    .082       01035.331    .046       01576.232    .052       0
Levee=-1,935.0319,815.0961,-1,1025.899,814.6938,,
#XS Ineff= 4 ,-1
  441.96   533.4818.6928 1280.16  2324.1815.0352  670.56  937.26814.1208
 1021.08 1280.16814.1208
Permanent Ineff=
       T       T       F       F
Bank Sta=935.0319,1025.899
XS Rating Curve= 0 ,0
Exp/Cntr=0.55,0.35

Type RM Length L Ch R = 1 ,51.44126,10.2949,30.8839,41.3671
XS GIS Cut Line= 5
       561214.66       4829517.7        561999.5      4829999.21
       562105.25      4830063.68        562278.6      4830167.46
       564217.55       4831725.4
#Sta/Elev= 30
       0 831.677 30.9921 830.761   119.2 830.409 125.791836.6669131.7471830.7379
361.2941 831.015  382.46837.5849 430.106 822.665 489.524817.4958520.5161 820.075
926.1653815.1664932.7471812.5889 945.816810.7001961.1981810.47691020.869813.8839
1025.743 814.3811029.084811.77591304.175819.22711563.416814.74292595.179819.0601
2792.772821.53422795.912829.10992810.111 821.6883159.267824.2679 3242.67832.6971
3286.978824.98113426.275826.12293433.145 832.3563447.194826.44383733.977828.2581
#Mann= 9 ,-1 , 0
       0    .046       0 30.9921    .052       0 489.524    .036       0
520.5161    .046       0932.7471    .082       0 945.816    .037       0
1020.869    .082       01029.084    .046       01563.416    .052       0
Levee=-1,926.1653,815.1754,-1,1025.743,814.3738,,
#XS Ineff= 4 ,-1
  441.96  518.16818.6928 1280.16  2324.1814.7304  670.56  929.64814.1208
  1028.7 1280.16814.1208
Permanent Ineff=
       T       T       F       F
Bank Sta=926.1653,1025.743
XS Rating Curve= 0 ,0
Exp/Cntr=0.55,0.35

Type RM Length L Ch R = 1 ,51.42207,9.0251,27.9691,35.7521
XS GIS Cut Line= 4
       561212.74      4829520.74       561990.17      4829998.58
       562115.18      4830137.74       564176.01      4831755.72
#Sta/Elev= 30
       0 830.352 33.1049830.5739 365.842831.2421385.7701837.8488424.6651822.8838
485.7921 817.804515.5491820.2299925.2418 815.325 930.298 813.363944.4301 810.345
949.5349 810.287964.1439811.5529974.1871811.08811006.163813.64421006.916813.6121
1015.104 813.3561120.229820.55691130.622813.61521303.752813.59111317.887813.8791
1381.122814.35881411.391820.55791460.723 813.8951466.675813.80022807.213 821.218
2961.329 829.1313048.341  823.163098.234 830.9863110.914823.96983719.691827.4531
#Mann= 15 ,-1 , 0
       0    .046       0 33.1049    .052       0485.7921    .036       0
515.5491    .046       0 930.298    .082       0944.4301    .037       0
964.1439    .057       0974.1871    .037       01006.916    .082       0
1015.104    .046       01303.752    .052       01317.887    .036       0
1381.122    .052       01460.723    .046       01466.675    .052       0
Levee=-1,925.2418,815.3766,-1,1006.163,813.6514,,
#XS Ineff= 4 ,-1
 1112.52 2308.86814.4256  441.96  518.16818.6928  662.94  922.02814.1208
 1051.56 1112.52814.1208
Permanent Ineff=
       T       T       F       F
Bank Sta=925.2418,1006.163
XS Rating Curve= 0 ,0
Exp/Cntr=0.3,0.1

Type RM Length L Ch R = 1 ,51.40470,24.658,23.668,22.8091
XS GIS Cut Line= 4
       561210.24       4829524.7       561988.83      4830004.27
       562054.28      4830152.57       564118.64      4831778.43
#Sta/Elev= 30
       0  830.21  35.561 830.694 369.634831.0522376.8389 837.777416.4799 823.377
480.8128817.9951508.9651 820.118924.4553815.1456929.3989 813.862939.7841809.6171
943.1039 810.341958.6622811.2371968.2942811.0811 998.668813.52191011.244813.9683
1011.263 813.9691255.374813.2679 1339.09813.85411415.768814.10891453.104 823.796
1518.071813.66821627.747821.20191655.403813.88092179.532815.41712186.623 821.803
2202.844815.33782999.629822.71893032.764 829.5013039.635823.16393704.259  826.98
#Mann= 13 ,-1 , 0
       0    .046       0  35.561    .052       0480.8128    .036       0
508.9651    .046       0929.3989    .082       0943.1039    .037       0
958.6622    .057       0968.2942    .037       0 998.668    .082       0
1011.263    .046       01255.374    .052       0 1339.09    .036       0
1415.768    .052       0
Levee=-1,924.4553,815.151,-1,1011.244,813.9501,,
#XS Ineff= 3 ,-1
 1097.28 2316.48814.4256  434.34  502.92818.6928  662.94  922.02814.1208
Permanent Ineff=
       T       T       F
Bank Sta=924.4553,1011.244
XS Rating Curve= 0 ,0
Exp/Cntr=0.3,0.1