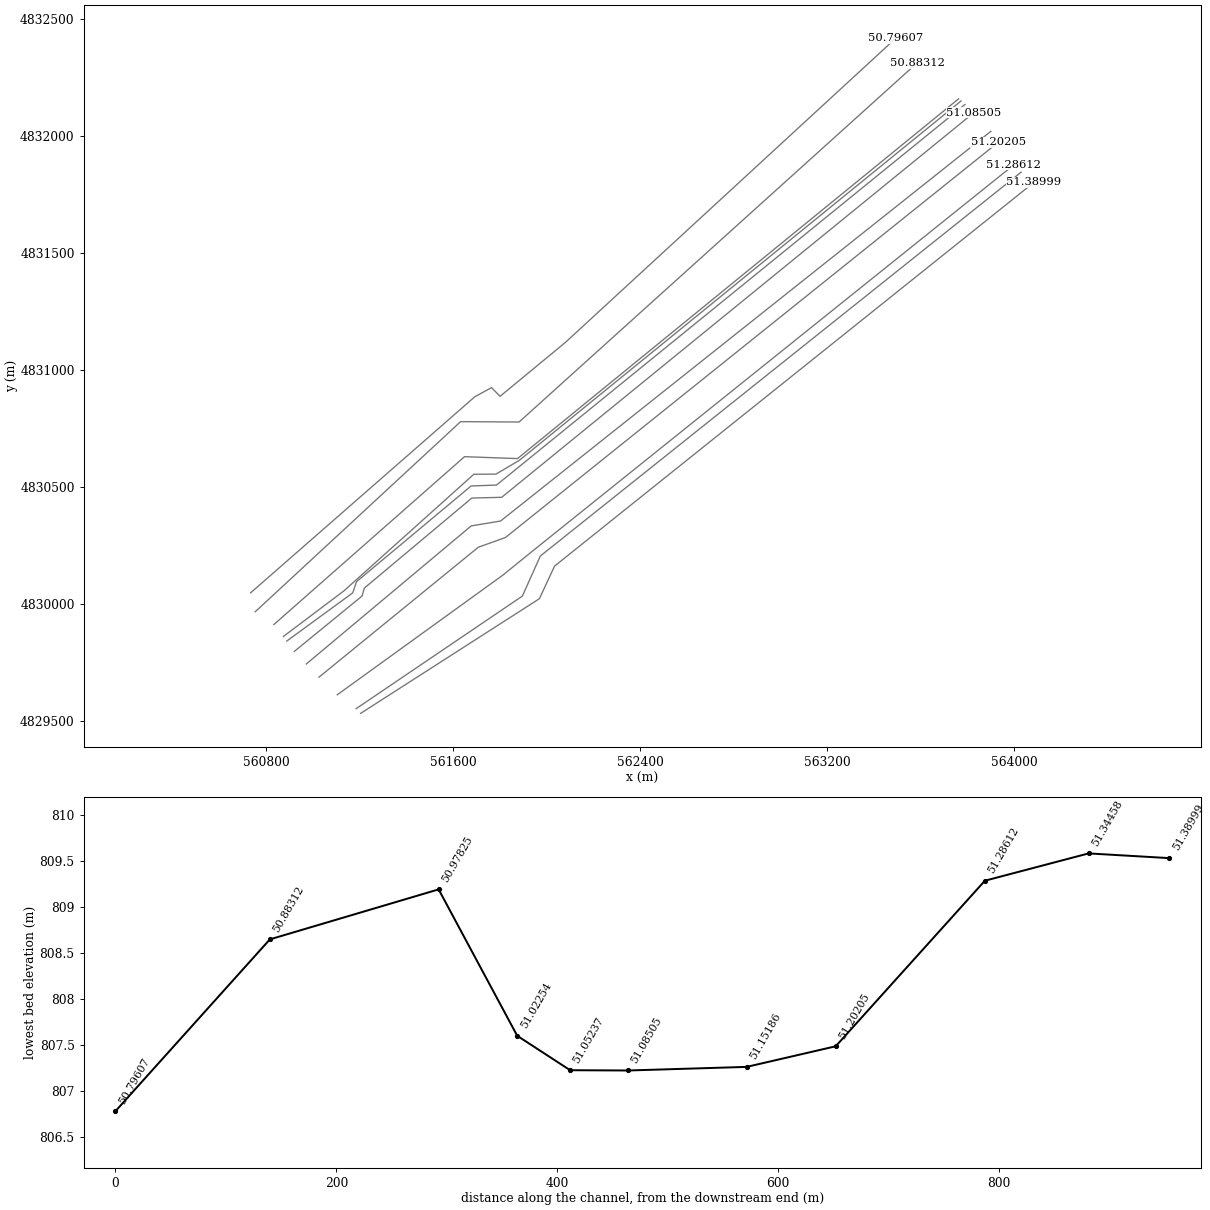
HEC-RAS study Boise2.prj: BoiseRiver_All_reaches

--- Boise2.g01 (geometry) --- (continued)

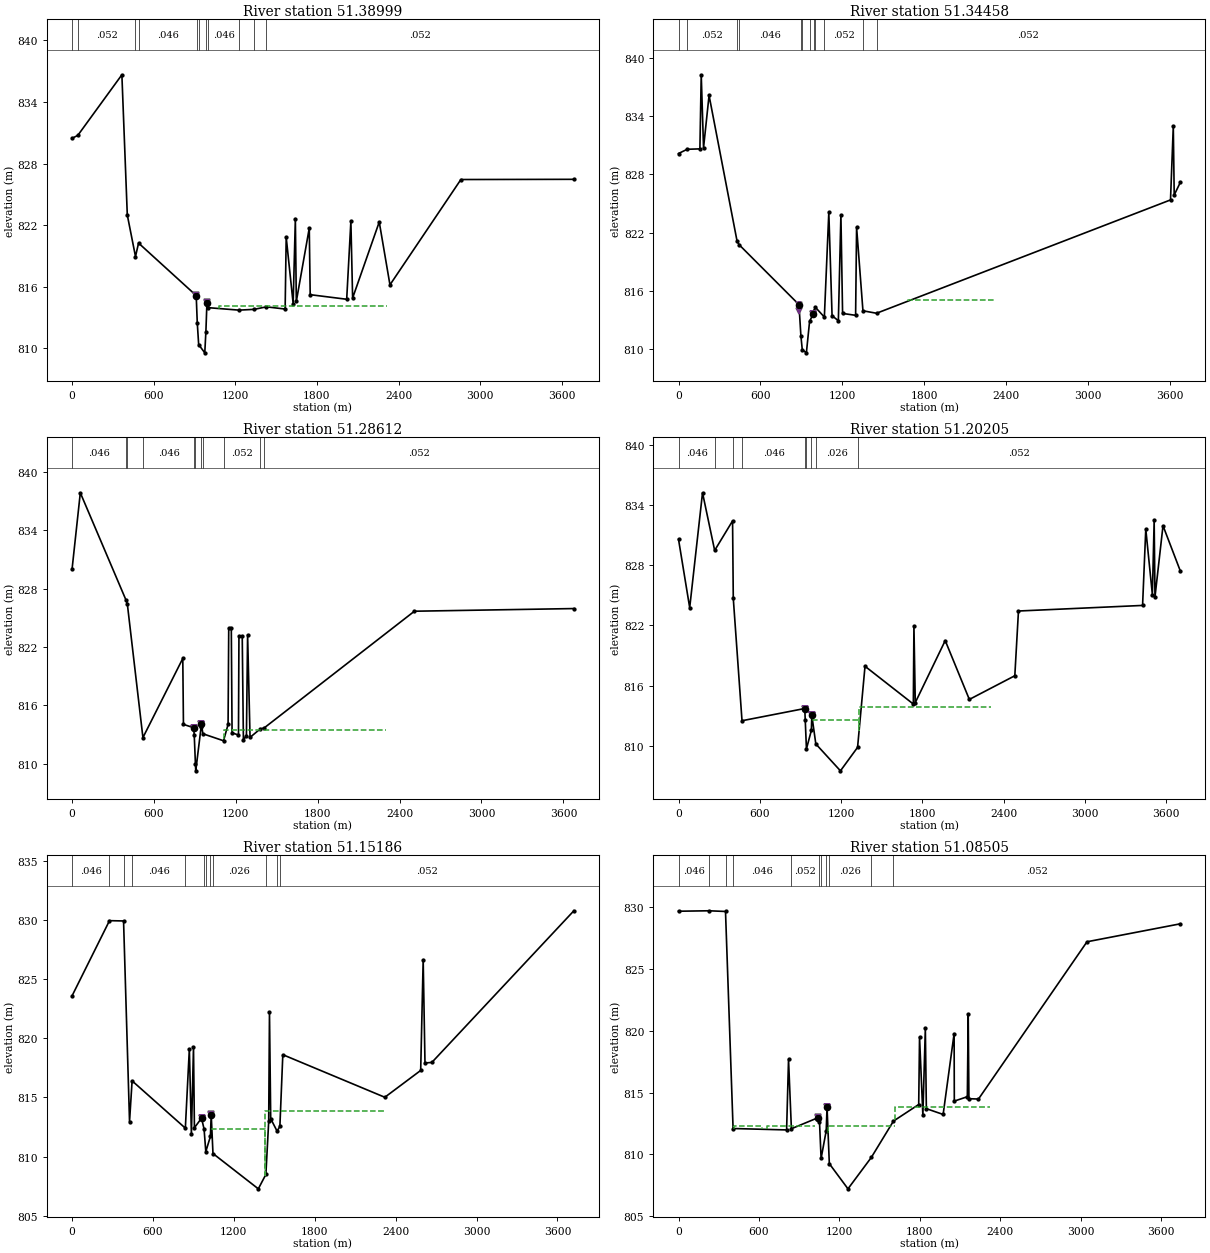
Type RM Length L Ch R = 1 ,51.38999,71.632,72.9411,72.857
XS GIS Cut Line= 4
       561204.51      4829530.88       561969.32      4830020.97
       562034.32      4830160.39       564085.71      4831800.56
#Sta/Elev= 30
       0830.4581 42.0511 830.741366.1638836.6531  405.99822.9771466.2471818.9278
488.7471820.2391912.5529815.1207 920.321812.4669930.6489 810.338975.5319809.5338
983.7661811.6129991.2614814.40051000.365813.94011226.479 813.6991338.246813.7739
1428.249814.01991566.291813.80511574.037820.81511625.188 814.336 1641.41 822.626
1648.455814.54781743.641 821.6961750.425815.20592018.748 814.7592049.551822.3559
2062.339814.88092258.056 822.2952336.796816.16512858.169826.43683688.659 826.457
#Mann= 11 ,-1 , 0
       0    .046       0 42.0511    .052       0466.2471    .036       0
488.7471    .046       0 920.321    .082       0930.6489    .037       0
983.7661    .082       01000.365    .046       01226.479    .052       0
1338.246    .036       01428.249    .052       0
Levee=-1,912.5529,815.148,-1,991.2614,814.4866,,
#XS Ineff= 3 ,-1
 1082.04 2316.48814.1208  426.72  487.68818.6928  655.32  906.78814.1208
Permanent Ineff=
       T       T       F
Bank Sta=912.5529,991.2614
XS Rating Curve= 0 ,0
Exp/Cntr=0.3,0.1

Type RM Length L Ch R = 1 ,51.34458,109.1519,93.9049,72.8189
XS GIS Cut Line= 4
       561185.33      4829551.04        561896.5      4830032.17
       561973.37      4830203.38        564030.5      4831843.93
#Sta/Elev= 30
       0830.1511 63.6209830.5879156.5419  830.63166.3531 838.274183.2049830.7379
223.7061836.1441429.1651 821.097444.9791820.7271882.6094814.5598 896.945811.3011
906.8742809.9109936.9689 809.585960.5659812.8449988.6675813.6287 990.721813.9261
1003.585 814.2721068.684813.27681101.376824.07011125.191813.41911171.264812.8961
1189.992 823.8141202.287813.65111297.765813.45511304.913 822.5471351.485 813.923
1451.146813.66913605.571 825.363 3625.95832.96813632.701825.8729 3677.51827.1751
#Mann= 12 ,-1 , 0
       0    .046       0 63.6209    .052       0429.1651    .036       0
444.9791    .046       0 896.945    .082       0906.8742    .037       0
960.5659    .082       0 990.721    .046       01003.585    .036       0
1068.684    .052       01351.485    .036       01451.146    .052       0
Levee=-1,882.6094,813.9288,-1,988.6675,813.624,,
#XS Ineff= 3 ,-1
 1082.041682.801813.5112  777.24   876.3814.12081682.801 2308.86815.0352
Permanent Ineff=
       T       F       T
Bank Sta=882.6094,988.6675
XS Rating Curve= 0 ,0
Exp/Cntr=0.3,0.1

Type RM Length L Ch R = 1 ,51.28612,143.0368,135.0529,133.065
XS GIS Cut Line= 4
       561104.59      4829610.42       561811.98      4830120.91
       561939.54      4830224.18       563999.68      4831875.52
#Sta/Elev= 30
       0 830.003 60.4211 837.844396.3549 826.785 404.811826.4411519.1661 812.702
811.2819820.8292816.0541 814.061891.3053813.7137895.2908812.9321903.7469810.0319
 906.221809.2882945.2952813.7681947.8762814.1389958.1632 813.0971109.646812.3771
1143.114814.05011147.907823.94761166.787 823.9081172.359813.18991219.283812.9689
1222.733823.0911 1246.83823.10941255.431 812.4631277.557812.90581286.235823.2617
 1304.08812.72611379.152813.59411406.728 813.6842508.476 825.681 3676.76825.9532
#Mann= 11 ,-1 , 0
       0    .046       0396.3549    .052       0 404.811    .036       0
519.1661    .046       0895.2908    .082       0903.7469    .037       0
945.2952    .082       0958.1632    .036       01109.646    .052       0
1379.152    .036       01406.728    .052       0
Levee=-1,891.3053,813.691,-1,947.8762,814.1483,,
#XS Ineff= 2 ,-1
  510.54  632.46813.2064 1112.52 2301.24813.5112
Permanent Ineff=
       T       T
Bank Sta=891.3053,947.8762
XS Rating Curve= 0 ,0
Exp/Cntr=0.3,0.1

Type RM Length L Ch R = 1 ,51.20205,86.277,80.6129,81.1609
BEGIN DESCRIPTION:
FEMA XS "BA"
PROJECT XS "BA"
END DESCRIPTION:
XS GIS Cut Line= 6
       561026.28      4829685.64       561366.54      4829962.81
       561708.04      4830241.01       561823.99      4830282.42
       562466.89      4830797.46       563933.23      4831972.18
#Sta/Elev= 30
       0  830.59  82.406823.7759177.0931835.2459266.7658 829.491398.9469 832.438
404.2239824.7059468.6931 812.491 931.993813.7119 935.533812.5721 944.425809.6793
980.7352811.5239984.1535813.0175 1013.71 810.1741195.496 807.4891321.973809.8311
 1376.86 817.9281733.694814.15581738.098 821.9591748.069814.30191969.112820.4921
2147.218 814.6172482.997816.98112509.952823.44313426.373824.00093449.976831.6221
 3498.79825.06713511.887832.49413517.941  824.853577.145831.95893705.082827.4381
#Mann= 9 ,-1 , 0
       0    .046       0266.7658    .052       0404.2239    .036       0
468.6931    .046       0 935.533    .082       0 944.425    .037       0
980.7352    .082       0 1013.71    .026       01321.973    .052       0
Levee=-1,931.993,813.7002,-1,984.1535,813.0327,,
#XS Ineff= 4 ,-1
 984.5041332.839812.5968  464.82  624.84812.9016  670.56  845.82812.9016
1332.839 2308.86 813.816
Permanent Ineff=
       T       T       T       T
Bank Sta=931.993,984.1535
XS Rating Curve= 0 ,0
Exp/Cntr=0.3,0.1

Type RM Length L Ch R = 1 ,51.15186,111.6269,107.3161,92.7049
XS GIS Cut Line= 4
       560972.09        4829742.       561677.63      4830332.13
       561803.43      4830353.09       563900.91      4832018.52
#Sta/Elev= 30
       0 823.601277.5579 829.964381.8738829.9381   426.2812.9559445.2101 816.405
840.1239812.4011869.8751 819.118 885.035811.8979900.5749819.2509907.4219812.4349
960.1017813.2457979.0889 812.324991.7558 810.4151026.031811.6971 1031.91813.5518
1045.032810.25291381.326 807.2651437.338808.4829 1458.33 812.9721464.083822.2291
1473.213813.20211520.419812.14811541.283812.55111563.014818.61992319.587815.0151
2585.543817.28612604.075 826.6632617.417817.91712668.382 817.9643721.568   830.8
#Mann= 12 ,-1 , 0
       0    .046       0277.5579    .052       0381.8738    .036       0
445.2101    .046       0840.1239    .052       0979.0889    .082       0
991.7558    .037       01026.031    .082       01045.032    .026       0
1437.338    .052       01520.419    .036       01541.283    .052       0
Levee=-1,960.1017,813.246,-1,1031.91,813.5874,,
#XS Ineff= 4 ,-1
  441.96  624.84812.5968  662.94  960.12812.5968 1033.68 1432.56 812.292
 1432.56 2316.48 813.816
Permanent Ineff=
       T       T       T       T
Bank Sta=960.1017,1031.91
XS Rating Curve= 0 ,0
Exp/Cntr=0.3,0.1

Type RM Length L Ch R = 1 ,51.08505,52.2119,52.496,70.7331
XS GIS Cut Line= 6
       560920.71      4829795.65        561210.8      4830032.61
       561220.12      4830066.16       561680.21      4830451.21
       561808.09      4830454.36       563828.39      4832098.38
#Sta/Elev= 30
       0829.6391227.8858 829.675350.2481 829.619 406.752 812.096805.9159 811.982
 820.222 817.672841.5681812.07811042.837812.98031051.118 812.6581063.092809.6759
 1101.26811.92191107.393813.82551124.461 809.2581263.486807.22591437.289 809.757
1602.684812.69561790.974814.03391797.176819.47311821.985 813.1781840.439820.1842
 1847.99 813.6991973.124 813.2322055.056819.76112056.496814.30882153.624814.6639
 2160.11821.34312165.453 814.5032236.664814.47593045.924 827.1733741.871828.6229
#Mann= 11 ,-1 , 0
       0    .046       0227.8858    .052       0350.2481    .036       0
 406.752    .046       0841.5681    .052       01051.118    .082       0
1063.092    .037       0 1101.26    .082       01124.461    .026       0
1437.289    .036       01602.684    .052       0
Levee=-1,1042.837,813.0479,-1,1107.393,813.8282,,
#XS Ineff= 4 ,-1
1115.156 1615.44 812.292  411.48  624.84 812.292  662.94 1021.08 812.292
 1615.44  2324.1 813.816
Permanent Ineff=
       T       T       T       T
Bank Sta=1042.837,1107.393
XS Rating Curve= 0 ,0
Exp/Cntr=0.3,0.1

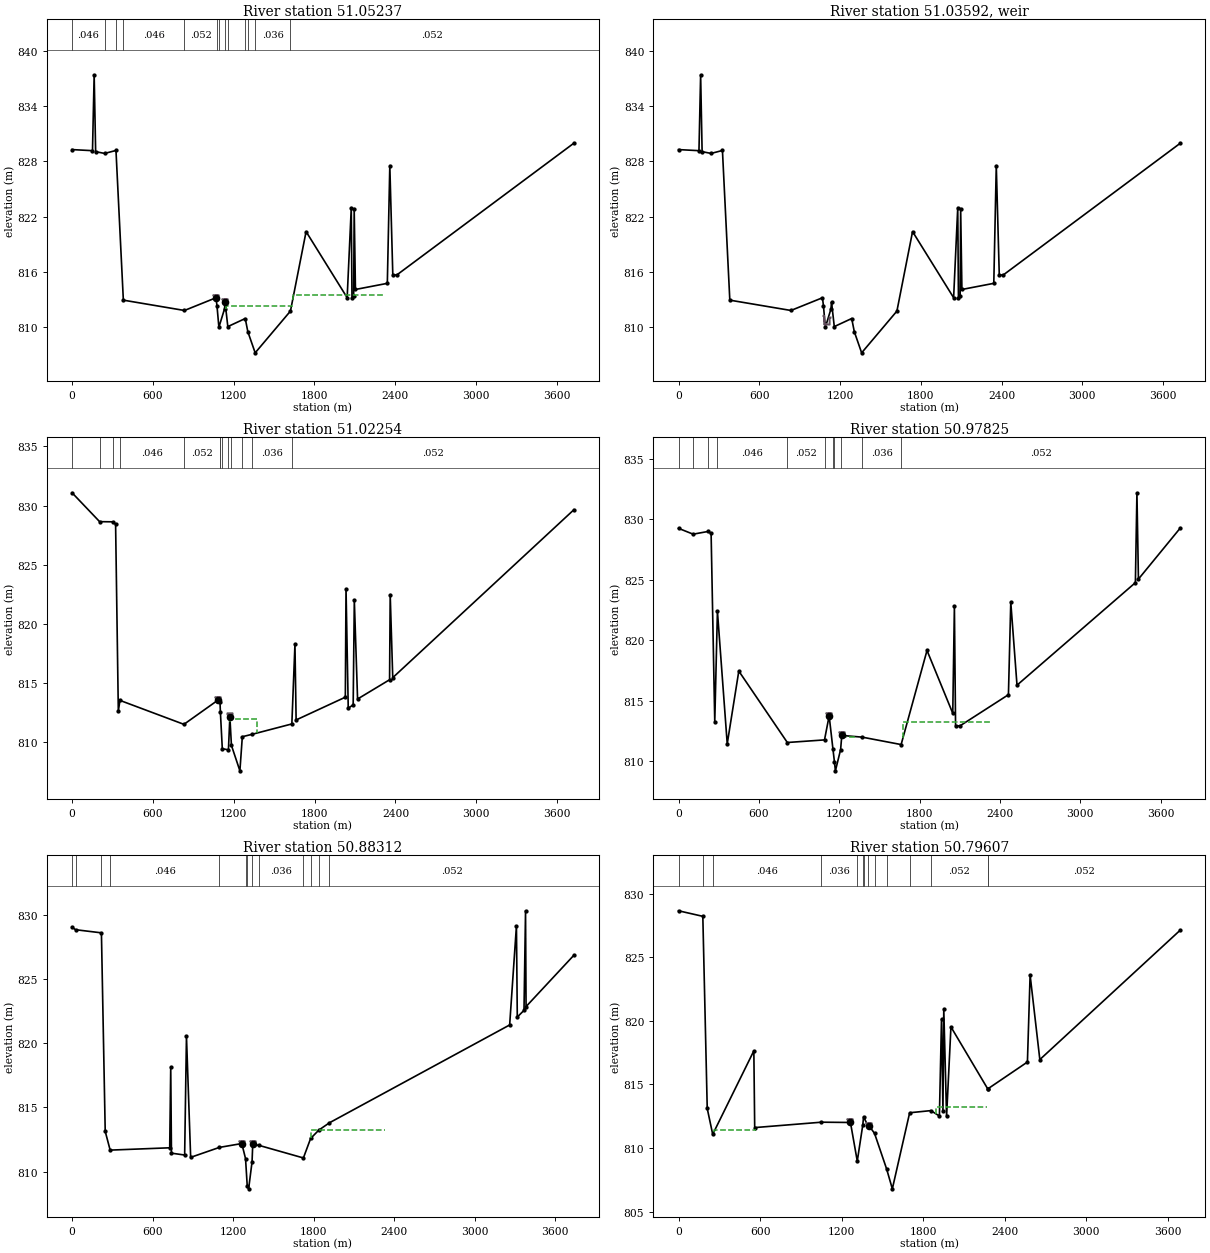
Type RM Length L Ch R = 1 ,51.05237,48.9771,47.9121,35.4601
XS GIS Cut Line= 6
       560888.42      4829839.86       561170.85      4830046.06
       561186.69      4830093.58       561677.12      4830502.85
       561785.92      4830506.68       563790.32      4832133.38
#Sta/Elev= 30
       0829.2831151.8111829.1661164.1991837.4011  175.21 829.059 242.002 828.867
326.2741 829.188381.0881812.9461835.2621811.82591069.498813.20541076.892 812.332
1091.062810.00511132.825811.99691136.864812.72851157.435810.07611286.826 810.953
1306.216809.52011360.657807.22891622.796811.7601 1739.01820.38512044.228813.2119
2074.855822.98592080.061 813.1612092.573 813.3862096.442 822.8782105.767814.1049
 2342.69  814.772361.161827.54422383.467815.65792414.401815.6921 3728.85829.9771
#Mann= 13 ,-1 , 0
       0    .046       0 242.002    .052       0326.2741    .036       0
381.0881    .046       0835.2621    .052       01076.892    .082       0
1091.062    .037       01132.825    .082       01157.435    .026       0
1286.826    .057       01306.216    .026       01360.657    .036       0
1622.796    .052       0
Levee=-1,1069.498,813.2125,-1,1136.864,812.7431,,
#XS Ineff= 4 ,-1
1142.982  1638.3 812.292  388.62  617.22811.9872  655.32 1059.18811.9872
  1638.3 2308.86813.5112
Permanent Ineff=
       T       T       T       T
Bank Sta=1069.498,1136.864
XS Rating Curve= 0 ,0
Exp/Cntr=0.5,0.3

Type RM Length L Ch R = 5 ,51.03592,,,
BEGIN DESCRIPTION:
Thurman Mill Ditch Co. (RM 51.04)
END DESCRIPTION:
IW Pilot Flow=0
#Inline Weir SE= 6
1077.468811.2313 1082.04811.2313 1082.04810.31991122.883810.29861122.883811.0606
1129.284811.0606
IW Dist,WD,Coef,Skew,MaxSub,Min_El,Is_Ogee,SpillHt,DesHd
21.336,3.6576,1.88,0,0.98,, 0 ,,,1,1,

Type RM Length L Ch R = 1 ,51.02254,72.8271,71.1488,33.5131
XS GIS Cut Line= 6
       560874.03      4829859.55       561133.27      4830054.71
       561688.82      4830552.85       561783.46      4830553.44
        561883.7      4830612.41        563773.6      4832148.34
#Sta/Elev= 30
       0 831.089 204.448  828.65300.8989 828.636323.0249828.4479343.2981812.6529
  355.27813.5538830.0801  811.531082.848 813.5761097.836813.42191100.815812.5529
1114.966809.47111160.399809.3781 1171.13812.16671182.743809.75091245.511 807.603
1263.554 810.4861337.289810.69091631.112811.56411654.124818.28991662.751811.9001
2027.961813.82392033.116822.9819 2049.63812.89222086.197 813.1782094.702822.0081
2118.798813.66822356.344 815.2972360.971822.4861 2379.92815.4732    3724 829.654
#Mann= 13 ,-1 , 0
       0    .046       0 204.448    .052       0300.8989    .036       0
  355.27    .046       0830.0801    .052       01097.836    .036       0
1100.815    .082       01114.966    .037       01160.399    .082       0
1182.743    .026       01263.554    .057       01337.289    .036       0
1631.112    .052       0
Levee=-1,1082.848,813.566,-1,1171.13,812.1975,,
#XS Ineff= 4 ,-1
1173.145  1371.6811.9872  373.38   609.6811.9872  655.32 1074.42811.9872
 1645.92 2301.24813.5112
Permanent Ineff=
       T       T       T       T
Bank Sta=1082.848,1171.13
XS Rating Curve= 0 ,0
Exp/Cntr=0.5,0.3

Type RM Length L Ch R = 1 ,50.97825,152.8011,152.802,156.9812
XS GIS Cut Line= 5
       560833.31      4829910.65        561649.1      4830628.06
       561781.88      4830623.17       561875.66      4830619.82
       563763.07      4832157.52
#Sta/Elev= 30
       0829.2361 109.055 828.754220.7319 828.978243.2831 828.814 270.564 813.232
290.4369822.3851 363.649 811.424450.1259817.4401812.4749811.53611090.171 811.751
1124.855813.73691152.755811.03411164.748   809.91171.565 809.1941210.468810.9521
1219.246812.11951370.865811.97991662.426 811.3661855.701 819.143 2048.01 813.952
2060.264822.78692069.019812.90012102.776812.91722463.799 815.4862481.307 823.131
2527.797 816.2733411.953824.74583423.453 832.1753434.672825.0399 3747.58 829.266
#Mann= 11 ,-1 , 0
       0    .046       0 109.055    .052       0220.7319    .036       0
290.4369    .046       0812.4749    .052       01090.171    .036       0
1152.755    .082       01164.748    .037       01210.468    .057       0
1370.865    .036       01662.426    .052       0
Levee=-1,1124.855,813.749,-1,1219.246,812.1152,,
#XS Ineff= 4 ,-1
  320.04  594.36811.6824  640.08 1074.42811.68241217.7951334.987811.9872
  1676.4 2331.72813.2064
Permanent Ineff=
       T       T       T       T
Bank Sta=1124.855,1219.246
XS Rating Curve= 0 ,0
Exp/Cntr=0.3,0.1

Type RM Length L Ch R = 1 ,50.88312,117.629,139.8239,123.1901
XS GIS Cut Line= 4
       560753.29      4829965.06       561632.36      4830777.79
       561882.35       4830776.1       563585.21      4832310.64
#Sta/Elev= 30
       0829.0231 26.1759828.8329218.7589  828.59247.0361 813.126283.8261811.6669
 727.635811.8479735.2751 818.132740.6929811.4291838.9861811.2841852.4759820.5329
883.7582811.10211097.161 811.8761264.825812.17911292.736811.0021 1305.45808.8669
1315.789808.65081341.349810.75891346.353812.10831391.458812.04111723.897 811.056
1777.746812.57311839.073 813.2281917.976813.79493261.049821.41493311.542829.1331
3317.913822.03093367.897822.55183379.376830.30813383.274 822.8463739.475826.8431
#Mann= 13 ,-1 , 0
       0    .046       0 26.1759    .052       0218.7589    .036       0
283.8261    .046       01097.161    .036       01292.736    .082       0
 1305.45    .037       01341.349    .057       01391.458    .036       0
1723.897    .057       01777.746    .052       01839.073    .057       0
1917.976    .052       0
Levee=-1,1264.825,812.1792,-1,1346.353,812.106,,
#XS Ineff= 3 ,-1
  297.18   609.6811.3776  655.32 1082.04811.3776 1783.08 2331.72813.2064
Permanent Ineff=
       T       T       T
Bank Sta=1264.825,1346.353
XS Rating Curve= 0 ,0
Exp/Cntr=0.3,0.1

Type RM Length L Ch R = 1 ,50.79607,42.028,53.2041,115.6719
XS GIS Cut Line= 6
       560733.55      4830045.92       561693.41      4830884.44
       561764.75      4830923.06       561801.02      4830885.91
       562080.84      4831116.63       563493.82      4832416.03
#Sta/Elev= 30
       0828.6561178.6951 828.219 211.185 813.104 251.428811.0701 554.106817.6379
560.3699 811.6011051.862812.02591264.893812.00351315.105808.96511355.717811.8101
1361.625  812.461392.638811.75011402.153811.73851442.111811.14411531.458 808.332
1573.104806.78311700.554812.76811856.355 812.9361919.423 812.5131934.968 820.132
 1945.45812.89221951.576820.91511972.175812.48712004.296819.52092275.405814.6389
2275.774814.64812566.997816.75792586.798823.60192658.346816.95093692.042827.1379
#Mann= 14 ,-1 , 0
       0    .052       0178.6951    .036       0 251.428    .046       0
1051.862    .036       01315.105    .037       01355.717    .057       0
1361.625    .037       01392.638    .057       01442.111    .036       0
1531.458    .026       01700.554    .057       01856.355    .052       0
2275.405    .046       02275.774    .052       0
Levee=-1,1264.893,812.0024,-1,1402.153,811.7403,,
#XS Ineff= 4 ,-1
  259.08   571.5811.3776  617.22 1043.94811.37761424.9551710.855811.3776
 1897.38 2270.76813.2064
Permanent Ineff=
       T       T       T       T
Bank Sta=1264.893,1402.153
XS Rating Curve= 0 ,0
Exp/Cntr=0.3,0.1