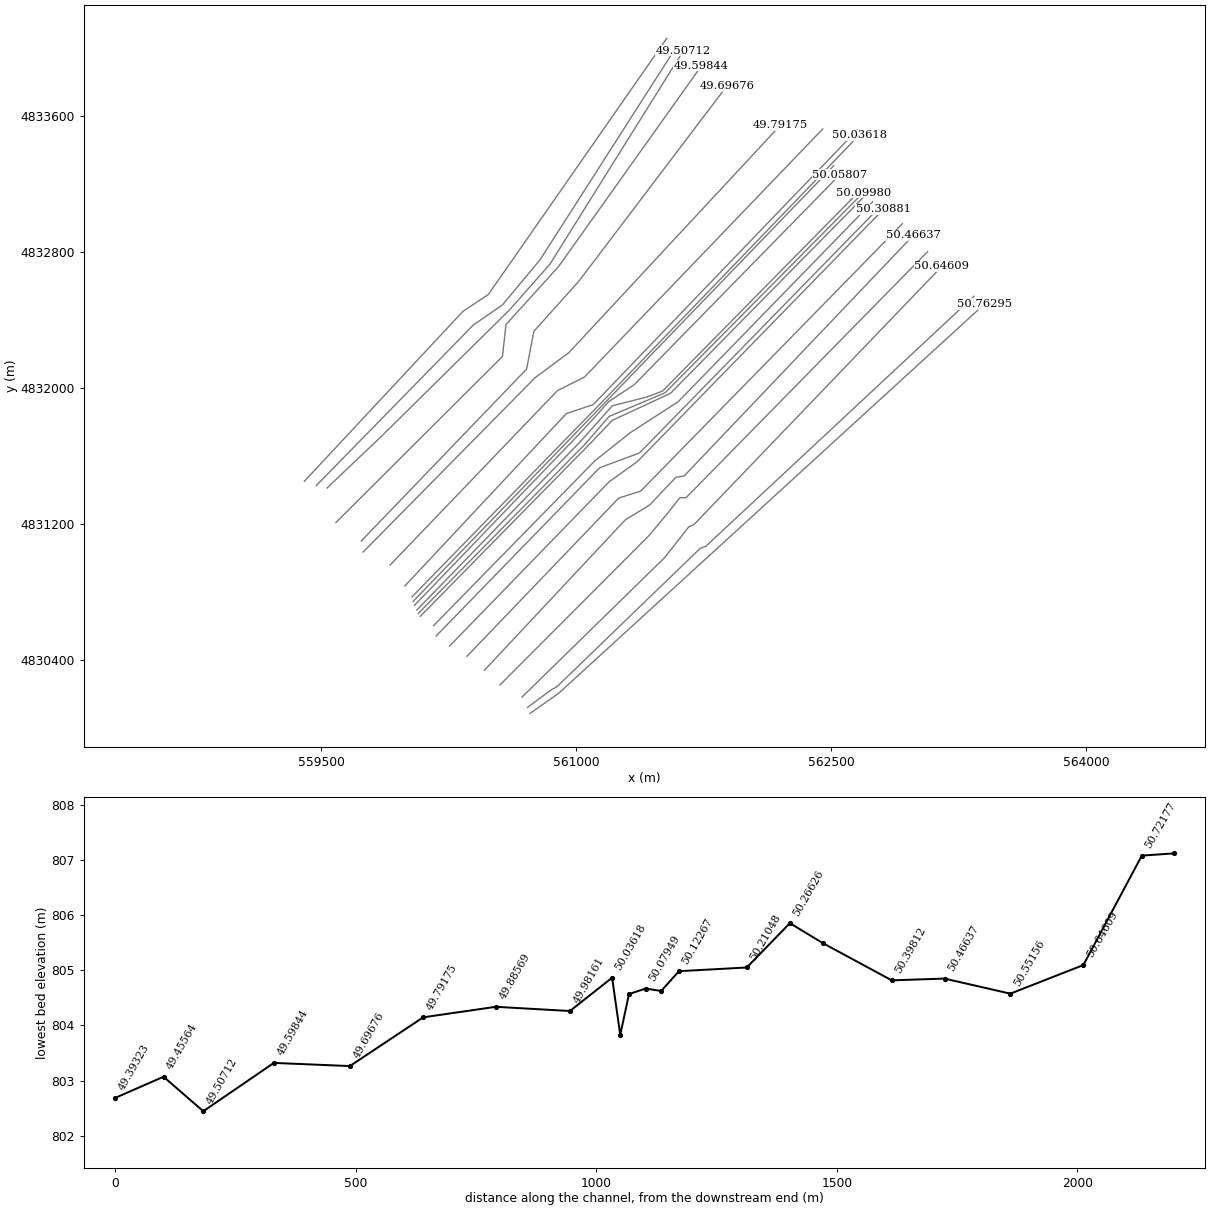
HEC-RAS study Boise2.prj: BoiseRiver_All_reaches

--- Boise2.g01 (geometry) --- (continued)

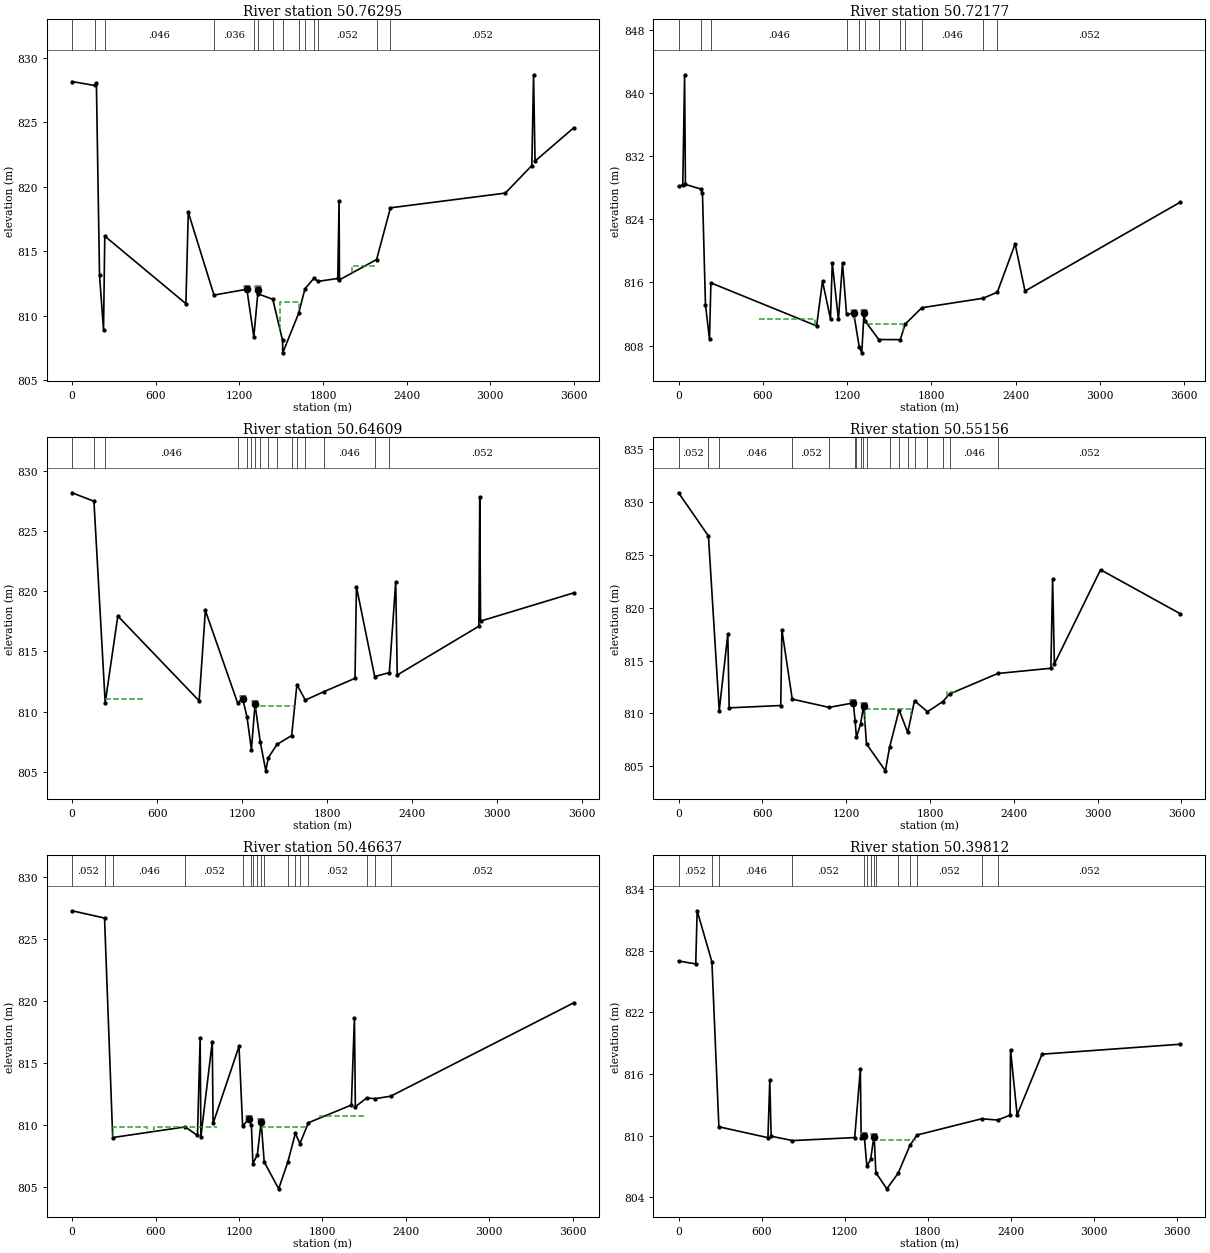
Type RM Length L Ch R = 1 ,50.76295,66.08,66.148,67.412
BEGIN DESCRIPTION:
FEMA XS "AZ"
PROJECT XS "AZ"
END DESCRIPTION:
XS GIS Cut Line= 5
       560728.86       4830088.7       560842.64      4830168.58
       560897.38      4830207.01       562004.08      4831218.64
       563401.68      4832496.18
#Sta/Elev= 30
       0828.1589161.2261827.8551 174.455 828.034196.9191 813.125225.5749808.9222
 234.642816.1682 816.369 810.929833.4409818.01791017.741811.59611253.658812.0473
1303.485 808.3531334.677812.02591336.594811.6812 1439.52811.26911509.697808.0739
 1510.94807.11491624.499  810.171670.563 812.0891733.542 812.8871766.291812.6638
1905.588 812.8831915.111818.92291917.693812.77782184.112 814.3532283.439818.3639
3106.997 819.5063297.464821.64513309.753828.6841 3320.47821.98713598.801824.5809
#Mann= 14 ,-1 , 0
       0    .052       0161.2261    .036       0 234.642    .046       0
1017.741    .036       01303.485    .037       01336.594    .057       0
 1439.52    .036       01509.697    .026       01624.499    .057       0
1670.563    .036       01733.542    .057       01766.291    .052       0
2184.112    .046       02283.439    .052       0
Levee=-1,1253.658,812.0695,-1,1334.677,812.0573,,
#XS Ineff= 5 ,-1
  236.22  541.02811.3776  586.74 1013.46811.37761379.4361403.409811.0728
1492.5231630.491811.0728 2004.06 2179.32 813.816
Permanent Ineff=
       T       T       T       T       T
Bank Sta=1253.658,1334.677
XS Rating Curve= 0 ,0
Exp/Cntr=0.3,0.1

Type RM Length L Ch R = 1 ,50.72177,116.7951,121.5649,129.2099
XS GIS Cut Line= 6
       560713.79      4830123.51       560854.13      4830227.76
       560886.44      4830245.15       561728.77      4831058.49
       561762.31      4831071.07       563338.65      4832541.29
#Sta/Elev= 30
       0828.1379 30.2371 828.319  43.085842.2739 49.1011828.3931  156.89827.8201
170.3451827.2991 191.832813.1461 220.621808.7831230.5099815.9319 983.429 810.486
1025.351816.14891082.371811.36111094.833818.46391138.775 811.2991167.798818.4529
1196.508812.00091248.147812.06621286.567807.85991305.182807.07511320.826812.0931
1329.095   811.11425.945808.76091579.261808.74411614.285810.71011732.935 812.787
2168.938813.98392270.434814.75212397.223820.85812467.708 814.8953573.798826.1501
#Mann= 12 ,-1 , 0
       0    .052       0  156.89    .036       0230.5099    .046       0
1196.508    .036       01286.567    .037       01329.095    .057       0
1425.945    .026       01579.261    .057       01614.285    .036       0
1732.935    .046       02168.938    .046       02270.434    .052       0
Levee=-1,1248.147,811.7617,-1,1320.826,812.103,,
#XS Ineff= 3 ,-1
   228.6  525.78811.3776   571.5  975.36811.37761342.7391599.584 810.768
Permanent Ineff=
       T       T       T
Bank Sta=1248.147,1320.826
XS Rating Curve= 0 ,0
Exp/Cntr=0.3,0.1

Type RM Length L Ch R = 1 ,50.64609,151.8151,151.8349,151.3009
XS GIS Cut Line= 6
       560682.05      4830185.08       561518.32      4831002.91
       561616.86       4831127.3       561662.15      4831185.89
       561691.64      4831197.88       563151.17      4832718.34
#Sta/Elev= 30
       0828.1529 154.426  827.45233.7651 810.736322.9521 817.932896.9749 810.899
940.8402818.3929 1168.47 810.7221203.923 811.0881235.057809.54691265.872806.8501
1291.374810.61591291.438810.61591327.855807.52191367.496805.09421384.879806.1749
1446.154807.28021549.932 808.0221587.121812.25091646.271810.9579  1779.8811.6711
1997.239812.7651  2007.1820.36282136.115812.91192239.538813.2415 2284.49820.7691
2295.255  813.042871.405817.08812877.699 827.8162883.431817.51293541.892819.8541
#Mann= 16 ,-1 , 0
       0    .052       0 154.426    .036       0233.7651    .046       0
 1168.47    .036       01235.057    .082       01265.872    .037       0
1291.374    .057       01327.855    .026       01384.879    .057       0
1446.154    .026       01549.932    .082       01587.121    .052       0
1646.271    .036       0  1779.8    .046       02136.115    .046       0
2239.538    .052       0
Levee=-1,1203.923,811.0881,-1,1291.438,810.6187,,
#XS Ineff= 3 ,-1
  236.22  502.92811.0728  548.64  922.02811.07281296.6191574.594810.4632
Permanent Ineff=
       T       T       T
Bank Sta=1203.923,1291.438
XS Rating Curve= 0 ,0
Exp/Cntr=0.3,0.1

Type RM Length L Ch R = 1 ,50.55156,145.083,136.8409,115.8639
XS GIS Cut Line= 6
        560552.1      4830256.11       561427.71      4831133.75
       561541.07      4831269.31       561609.41      4831356.69
       561646.45      4831357.38       563066.75      4832804.01
#Sta/Elev= 30
       0830.8479214.0671 826.763  291.29810.2639352.7301817.4949 362.377810.5281
 731.777810.7479739.6661817.9131 813.887811.3499 1077.88 810.5721251.033810.9939
1263.572809.3309 1273.27807.75811302.722808.97611322.117810.53911325.859810.6611
1345.464807.12411480.701 804.5761510.324806.78611578.926810.33091640.345808.2009
1689.193811.2011  1781.5810.15991892.126811.12311940.255811.83912285.062813.7748
2665.181 814.2682677.601822.67292690.338814.67793020.713823.57693591.733819.4161
#Mann= 18 ,-1 , 0
       0    .052       0214.0671    .036       0  291.29    .046       0
 813.887    .052       0 1077.88    .046       01263.572    .082       0
 1273.27    .037       01302.722    .082       01322.117    .057       0
1345.464    .026       01510.324    .057       01578.926    .026       0
1640.345    .082       01689.193    .052       0  1781.5    .036       0
1892.126    .052       01940.255    .046       02285.062    .052       0
Levee=-1,1251.033,811.0057,-1,1325.859,810.6644,,
#XS Ineff= 4 ,-1
  297.18  541.02810.4632  586.74 1043.94810.46321335.4291666.073810.4632
 1920.24 1996.44811.9872
Permanent Ineff=
       T       T       T       T
Bank Sta=1251.033,1325.859
XS Rating Curve= 0 ,0
Exp/Cntr=0.3,0.1

Type RM Length L Ch R = 1 ,50.46637,117.7281,109.6341,100.68
XS GIS Cut Line= 6
       560460.48      4830342.27       561289.33      4831227.18
       561431.64      4831313.71       561586.63       4831477.4
       561635.08      4831484.85       562982.92      4832900.15
#Sta/Elev= 30
       0827.3092 233.429 826.723292.2371808.9919813.2119809.8521901.6048809.1599
920.9419 817.056926.1741809.06291008.102816.73691013.737810.13011200.329816.3611
1226.313809.92711270.818810.4868 1289.45809.97881300.274 806.8871332.384807.6091
1359.082810.26821359.393810.26891381.451807.0229 1485.59804.84911552.103807.0461
1605.499809.3351 1637.97808.50311699.664810.18792008.124811.61992030.201 818.663
2036.855811.47522117.094 812.1862179.871 812.1322291.715812.33593607.863  819.88
#Mann= 17 ,-1 , 0
       0    .052       0 233.429    .036       0292.2371    .046       0
813.2119    .052       01226.313    .046       0 1289.45    .082       0
1300.274    .037       01332.384    .082       01359.082    .057       0
1381.451    .026       01552.103    .082       01605.499    .057       0
 1637.97    .082       01699.664    .052       02117.094    .046       0
2179.871    .046       02291.715    .052       0
Levee=-1,1270.818,810.4968,-1,1359.393,810.2712,,
#XS Ineff= 5 ,-1
  297.18  541.02809.8536  586.74 1043.94809.8536 1074.42  1219.2809.8536
 1363.411688.071809.8536 1783.08 2103.12 810.768
Permanent Ineff=
       T       T       T       T       T
Bank Sta=1270.818,1359.393
XS Rating Curve= 0 ,0
Exp/Cntr=0.3,0.1

Type RM Length L Ch R = 1 ,50.39812,126.1829,143.455,149.2389
XS GIS Cut Line= 4
       560358.01      4830424.59       561250.39      4831354.83
       561379.68      4831396.06       562918.51      4832968.39
#Sta/Elev= 30
       0827.0172124.2831826.7288134.4921 831.908241.0511826.9379291.4361810.8631
645.8879809.8021 659.134 815.412668.9501809.9459823.1971809.51711272.572809.8121
1313.582816.47511319.051809.73411341.153809.95421341.546809.95811360.757807.0159
1387.943807.68191410.417809.83811413.696809.86221425.279806.40121504.491804.8171
1586.584806.33591671.042809.04321722.152810.05912189.029811.6418 2306.11  811.52
  2395.2     8122398.078 818.3732445.897812.01892626.028817.93693624.819 818.907
#Mann= 14 ,-1 , 0
       0    .052       0241.0511    .036       0291.4361    .046       0
823.1971    .052       01341.546    .082       01360.757    .037       0
1387.943    .082       01410.417    .057       01425.279    .026       0
1586.584    .082       01671.042    .057       01722.152    .052       0
2189.029    .046       0 2306.11    .052       0
Levee=-1,1341.153,809.9694,-1,1413.696,809.8627,,
#XS Ineff= 5 ,-1
   304.8  548.64809.5488  594.36 1059.18809.5488 1089.66 1242.06809.5488
1415.4421715.835809.5488 1783.08 2186.94810.1584
Permanent Ineff=
       T       T       T       T       T
Bank Sta=1341.153,1413.696
XS Rating Curve= 0 ,0
Exp/Cntr=0.3,0.1

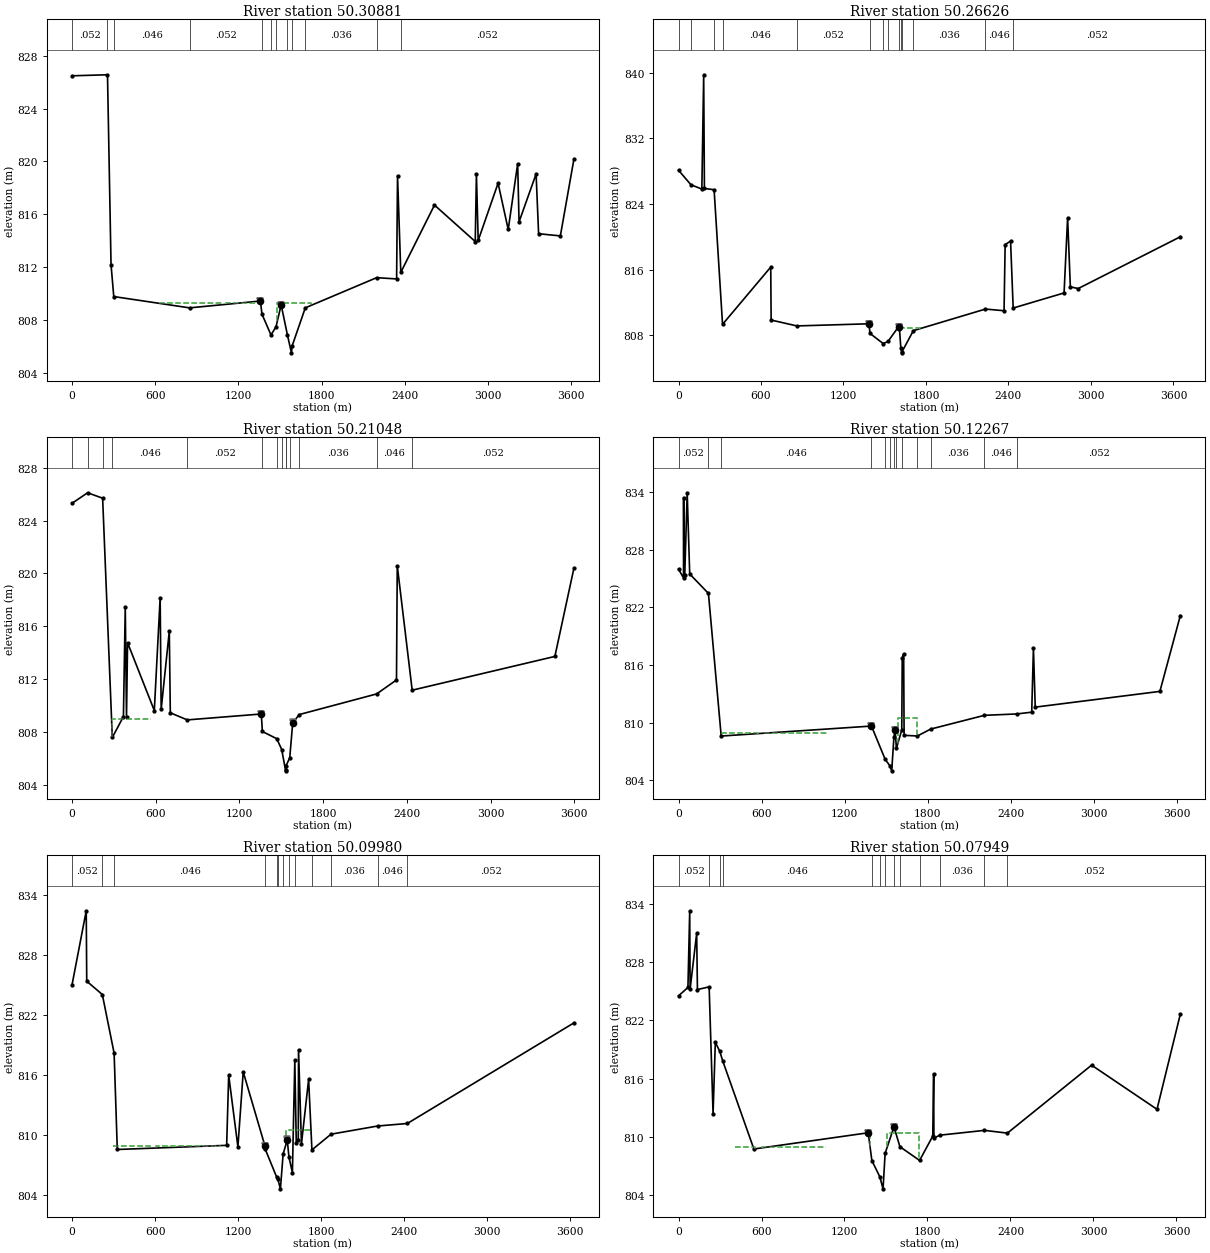
Type RM Length L Ch R = 1 ,50.30881,87.772,68.3471,53.162
BEGIN DESCRIPTION:
FEMA XS "AY"
PROJECT XS "AY"
END DESCRIPTION:
XS GIS Cut Line= 6
       560256.69      4830485.76       560478.67      4830714.34
       561192.46      4831449.31       561360.86      4831570.09
       561630.72      4831846.85       562806.25      4833052.45
#Sta/Elev= 30
       0 826.488255.6281826.5648 281.171 812.178300.8879 809.757847.9911808.9002
1359.317809.4186 1370.11 808.4281435.284806.84891471.492807.4631 1508.72809.1298
1554.046806.84191582.932805.49191588.444806.03111682.947 808.9032197.824 811.189
2341.812811.09292348.438818.91722371.985811.59092615.084816.69092909.157813.9269
2917.709819.0211 2930.49814.00713074.015 818.3483147.146814.84013215.353819.8279
3225.266815.41413348.319  819.053366.385814.51893523.323 814.3533620.798820.1461
#Mann= 12 ,-1 , 0
       0    .052       0255.6281    .036       0300.8879    .046       0
847.9911    .052       0 1370.11    .082       01435.284    .037       0
1471.492    .057       01554.046    .026       01588.444    .082       0
1682.947    .036       02197.824    .046       02371.985    .052       0
Levee=-1,1359.317,809.433,-1,1508.72,809.1252,,
#XS Ineff= 4 ,-1
  320.04  579.12 809.244  624.84 1082.04 809.244 1112.52 1341.12 809.244
1482.2031722.358 809.244
Permanent Ineff=
       T       T       T       T
Bank Sta=1359.317,1508.72
XS Rating Curve= 0 ,0
Exp/Cntr=0.3,0.1

Type RM Length L Ch R = 1 ,50.26626,64.3661,89.6021,113.0521
XS GIS Cut Line= 4
       560176.34      4830543.48       561137.97      4831533.01
       561372.34      4831620.03        562784.6      4833065.35
#Sta/Elev= 30
       0828.1239 90.5341826.3539169.6151825.8318182.9532839.7719188.2801825.9059
258.8249 825.748320.1549809.3269670.7371816.3111673.6961 809.853 860.804809.1349
1386.276809.39561392.326  808.231488.701806.98211523.747 807.2361600.276809.0307
1607.344808.78411617.201806.46081624.449805.85191625.597805.98111708.465808.5601
2232.687811.19012368.216810.98992376.052819.05792415.585819.48012434.563 811.317
2804.804813.15892830.574 822.3442850.446813.8971  2907.8813.69593650.568820.0101
#Mann= 14 ,-1 , 0
       0    .052       0 90.5341    .052       0258.8249    .036       0
320.1549    .046       0 860.804    .052       01392.326    .082       0
1488.701    .037       01523.747    .082       01607.344    .057       0
1617.201    .026       01625.597    .082       01708.465    .036       0
2232.687    .046       02434.563    .052       0
Levee=-1,1386.276,809.3934,-1,1600.276,809.0337,,
#XS Ineff= 4 ,-1
  327.66  594.36 809.244  640.08 1097.28 809.244 1127.76  1371.6 809.244
1600.9711758.729808.9392
Permanent Ineff=
       T       T       T       T
Bank Sta=1386.276,1600.276
XS Rating Curve= 0 ,0
Exp/Cntr=0.3,0.1

Type RM Length L Ch R = 1 ,50.21048,97.604,141.0511,121.71
XS GIS Cut Line= 5
       560161.79      4830605.06       561110.69      4831574.72
       561322.07      4831742.11       561600.21      4831921.71
       562743.55      4833097.18
#Sta/Elev= 30
       0825.3069111.1551 826.104219.0719825.6949288.4981807.5762368.1941809.1572
381.3661817.4419390.2141 809.106 397.899814.7512  589.56809.6149 631.509818.1561
638.7919809.7031 697.034815.6311704.2819 809.444825.9251808.90691356.698809.3542
1364.072  808.031467.672807.48191502.925806.6638 1531.02805.04991533.142805.1301
1534.231 805.4411560.481806.03691581.833808.70421629.908 809.3152183.162810.8719
2325.697811.92992331.227820.58812438.204 811.1563461.114 813.7133597.237820.3719
#Mann= 14 ,-1 , 0
       0    .052       0111.1551    .052       0219.0719    .036       0
288.4981    .046       0825.9251    .052       01364.072    .082       0
1467.672    .037       01502.925    .057       01533.142    .082       0
1534.231    .057       01560.481    .082       01629.908    .036       0
2183.162    .046       02438.204    .052       0
Levee=-1,1356.698,809.3629,-1,1581.833,808.7167,,
#XS Ineff= 3 ,-1
  289.56  563.88808.9392  601.98  1066.8808.9392 1097.28 1348.74808.9392
Permanent Ineff=
       T       T       T
Bank Sta=1356.698,1581.833
XS Rating Curve= 0 ,0
Exp/Cntr=0.3,0.1

Type RM Length L Ch R = 1 ,50.12267,20.944,36.7369,33.549
XS GIS Cut Line= 6
       560083.24      4830659.35       561018.39      4831610.69
       561065.17       4831657.7       561212.89      4831812.19
       561554.37      4831970.78       562702.73      4833137.29
#Sta/Elev= 30
       0825.9711 36.0149 825.075 36.7839833.4399 38.6819 825.342 44.8471825.3469
 62.5511833.9328 80.7769825.4801216.1989823.4541308.3369808.60521394.643809.6445
1394.771809.64391493.439806.19111527.175 805.5161541.098804.9829 1556.92 808.457
1565.395809.22361575.057 807.3251613.773 809.2441617.136 816.6791627.402817.1581
  1630.7808.68011727.049808.61211822.815809.33092210.957810.76192445.656810.9061
2553.169811.08982565.586 817.7722578.611811.61513479.759813.25483627.492821.1462
#Mann= 13 ,-1 , 0
       0    .052       0216.1989    .036       0308.3369    .046       0
1394.771    .082       01493.439    .057       01527.175    .037       0
 1556.92    .057       01575.057    .082       01617.136    .046       0
1727.049    .052       01822.815    .036       02210.957    .046       0
2445.656    .052       0
Levee=-1,1394.643,809.6433,-1,1565.395,809.2593,,
#XS Ineff= 4 ,-1
   304.8   571.5808.9392  617.22 1082.04808.9392 1112.52 1379.22808.9392
 1584.96 1722.12810.4632
Permanent Ineff=
       T       T       T       T
Bank Sta=1394.643,1565.395
XS Rating Curve= 0 ,0
Exp/Cntr=0.3,0.1

Type RM Length L Ch R = 1 ,50.09980,30.17,32.6151,32.5661
XS GIS Cut Line= 5
       560072.84       4830677.5       561047.12       4831666.4
       561193.36      4831834.65       561523.04      4831974.07
       562688.47      4833151.32
#Sta/Elev= 30
       0825.0171 102.382 832.399105.9479 825.364218.6251824.0359 303.828818.1741
326.7599808.55521116.925808.96911131.633815.97491198.237 808.8161236.607816.3029
1392.976808.94251395.142808.60691479.256805.76411487.233 805.572 1505.48804.6251
1524.939808.1019  1554.8809.50981566.997 807.799 1591.95 806.2531609.416817.4581
1619.971809.22811634.271 809.5181636.329818.50291657.384809.1138 1709.15815.5509
 1733.05808.51621871.187 810.0842208.008810.90092422.282 811.1523625.626821.1979
#Mann= 13 ,-1 , 0
       0    .052       0218.6251    .036       0 303.828    .046       0
1395.142    .082       01479.256    .057       01487.233    .037       0
1524.939    .057       01566.997    .082       01609.416    .046       0
 1733.05    .052       01871.187    .036       02208.008    .046       0
2422.282    .052       0
Levee=-1,1392.976,808.9453,-1,1554.8,809.6219,,
#XS Ineff= 4 ,-1
  297.18  563.88808.9392   609.6 1074.42808.9392  1104.9  1371.6808.9392
 1546.86 1722.12810.4632
Permanent Ineff=
       T       T       T       T
Bank Sta=1392.976,1554.8
XS Rating Curve= 0 ,0
Exp/Cntr=0.5,0.3

Type RM Length L Ch R = 1 ,50.07949,34.9371,34.4061,33.8819
BEGIN DESCRIPTION:
Veterans Memorial Parkway Bridge Upstream
END DESCRIPTION:
XS GIS Cut Line= 6
       560062.99       4830696.8       561027.27      4831689.84
       561212.29       4831897.4       561414.61      4831948.76
       561508.43       4831984.4       562671.13      4833164.92
#Sta/Elev= 30
       0 824.523 68.0021825.3792  80.797833.2681 83.7639825.2149 131.125 830.943
136.6309825.1649 221.325825.4438 249.701812.3911265.9651819.7379297.8881818.8221
320.7401817.7769544.7291 808.7671371.569810.43521397.977807.57491454.941805.9229
1478.778804.66891493.764808.31491556.214810.98281556.896 811.0821600.798 809.001
1743.026807.5911 1838.22810.09191844.693 816.5011846.534 809.8781888.883810.1879
2212.163810.68292377.976810.40012986.652817.38893459.581812.85013628.281 822.636
#Mann= 13 ,-1 , 0
       0    .052       0 221.325    .036       0297.8881    .046       0
320.7401    .046       01397.977    .082       01454.941    .037       0
1493.764    .057       01556.896    .082       01600.798    .046       0
1743.026    .052       01888.883    .036       02212.163    .046       0
2377.976    .052       0
Levee=-1,1371.569,810.4388,-1,1556.214,811.0789,,
#XS Ineff= 5 ,-1
  411.48  556.26808.9392  601.98  1066.8808.9392 1097.28  1371.6808.9392
  1371.6 1386.84810.1584 1508.76 1737.36810.4632
Permanent Ineff=
       T       T       T       T       T
Bank Sta=1371.569,1556.214
XS Rating Curve= 0 ,0
Exp/Cntr=0.5,0.3

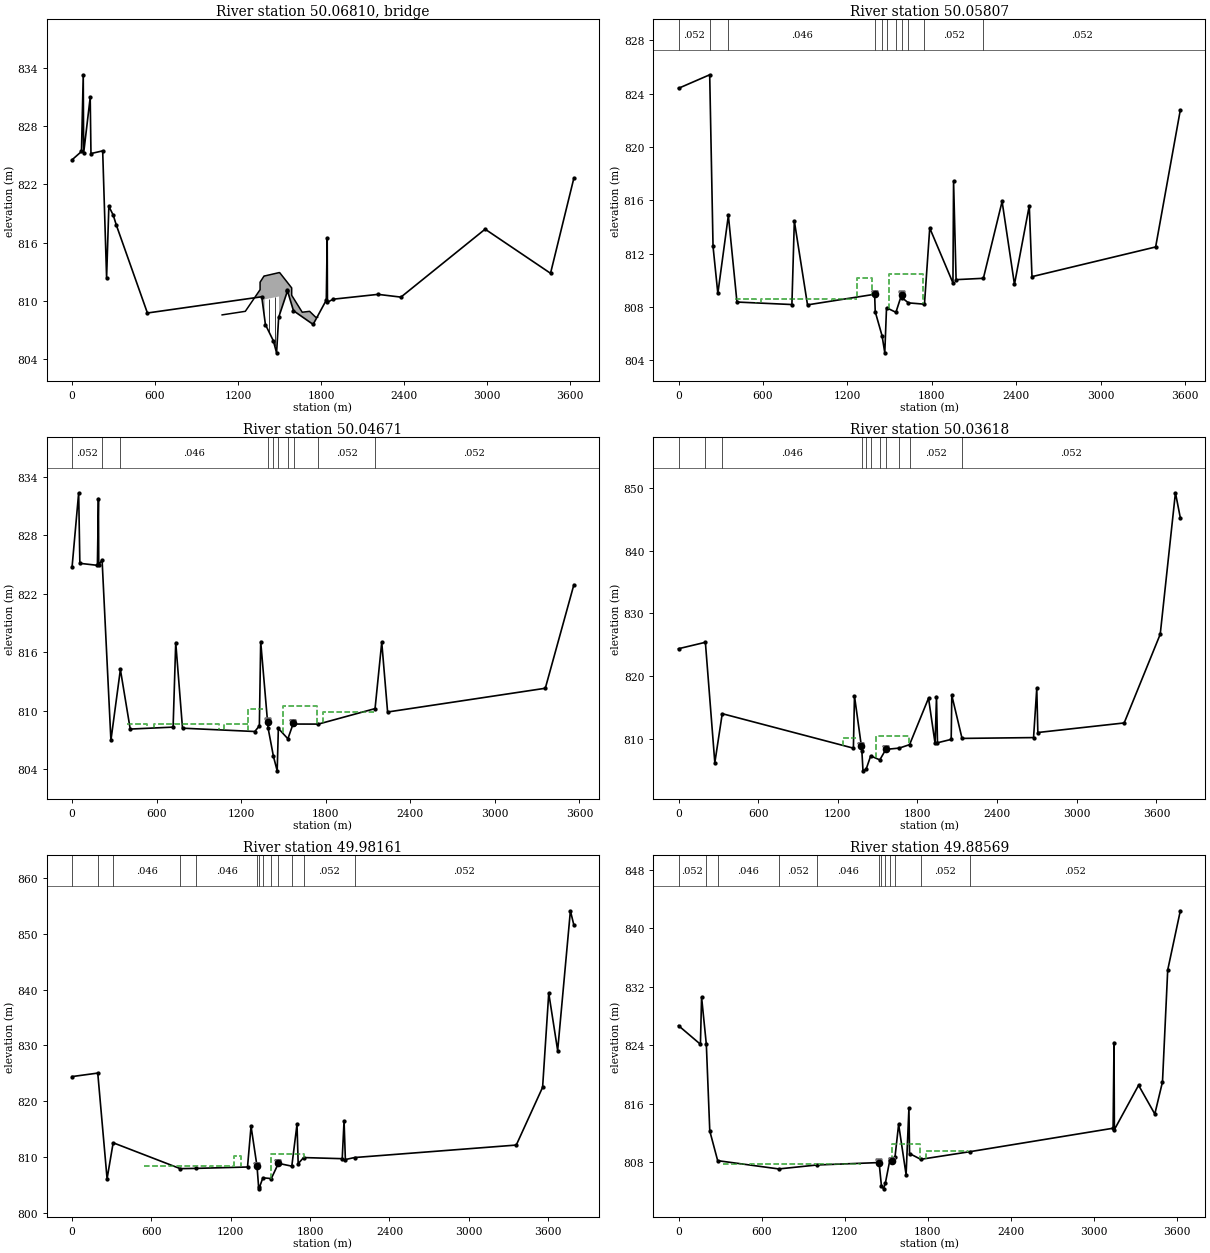
Type RM Length L Ch R = 3 ,50.06810,,,
BEGIN DESCRIPTION:
Veterans Memorial Parkway Bridge
END DESCRIPTION:
Bridge Culvert--1,0,-1,-1, 0
Deck Dist Width WeirC Skew NumUp NumDn MinLoCord MaxHiCord MaxSubmerge Is_Ogee
6.096,20.7264,1.44,0, 20, 20, , , 0.95, 0, 0,0,,
1085.0881252.7281359.4081359.4081388.3641392.9361392.9361496.5681496.568 1501.14
 1569.72 1569.721575.8161575.8161588.0081588.0081664.2081717.5481761.744 1775.46
808.5734808.9392811.1642811.9354812.5785812.5785812.5785812.9199812.9199812.9199
811.6793811.6793811.5666811.5666811.3471810.5851808.8477808.9392808.3296808.3296
 804.672 804.672 804.672 804.672 804.672 804.672810.1706810.4632 804.672 804.672
 804.672808.1467808.1467 804.672 804.672 804.672 804.672 804.672 804.672 804.672
1085.0881252.7281359.4081359.4081388.3641392.9361392.9361496.5681496.568 1501.14
 1569.72 1569.721575.8161575.8161588.0081588.0081664.2081717.5481761.744 1775.46
808.5734808.9392811.1642811.9354812.5785812.5785812.5785812.9199812.9199812.9199
811.6793811.6793811.5666811.5666811.3471810.5851808.8477808.9392808.3296808.3296
 804.672 804.672 804.672 804.672 804.672 804.672810.1706810.4632 804.672 804.672
 804.672808.1467808.1467 804.672 804.672 804.672 804.672 804.672 804.672 804.672
Pier Skew, UpSta & Num, DnSta & Num=  ,1423.416, 2 ,1423.416, 2 , 0 , 0 , 0 ,,
   .6096   .6096
804.0624 810.768
   .6096   .6096
804.0624 810.768
Pier Skew, UpSta & Num, DnSta & Num=  ,1466.088, 2 ,1466.088, 2 , 0 , 0 , 0 ,,
   .6096   .6096
804.0624 810.768
   .6096   .6096
804.0624 810.768
Pier Skew, UpSta & Num, DnSta & Num=  ,1572.768, 2 ,1572.768, 2 , 0 , 0 , 0 ,,
   .3048   .3048
 804.672 810.768
   .3048   .3048
 804.672 810.768
BR Coef=-1 , 0 , 0 ,1.25, 0 ,,,0.8,-1,2,0,
WSPro=,,,, 1 ,,,, 0 ,,,, 0 ,,,,-1 ,-1 ,-1 , 0 , 0 , 0 , 0 , 0
BC Design=,, 0 ,, 0 ,,,,,,
BC Use User HTab Curves=0
BC User HTab FreeFlow(D)= 0

Type RM Length L Ch R = 1 ,50.05807,18.64,18.2481,16.672
BEGIN DESCRIPTION:
Veterans Memorial Parkway Bridge Downstream
END DESCRIPTION:
XS GIS Cut Line= 6
       560049.16      4830723.91       561007.18      4831720.18
       561112.53      4831833.92       561190.63      4831921.45
       561341.58      4832021.56       562550.88      4833256.87
#Sta/Elev= 30
       0824.4069221.3439  825.42245.1131812.5459279.1989809.0209353.9371814.8721
414.9699808.3771805.2801  808.19822.5461814.4531 916.142 808.1651392.902808.9598
1397.215807.64691446.046805.83611465.046804.56811477.412 807.9521544.065 807.606
1584.795808.93621588.619808.69111632.816808.31591746.875808.21591784.351813.9251
1949.171  809.811953.612 817.4521971.543 810.0562165.326810.15812298.392  815.92
2386.126809.70482491.365815.60222510.661810.28093388.971812.50813564.322 822.782
#Mann= 11 ,-1 , 0
       0    .052       0221.3439    .036       0353.9371    .046       0
1397.215    .082       01446.046    .037       01477.412    .057       0
1544.065    .082       01588.619    .046       01632.816    .036       0
1746.875    .052       02165.326    .052       0
Levee=-1,1392.902,808.9606,-1,1584.795,808.9453,,
#XS Ineff= 6 ,-1
  403.86  548.64808.6344  586.74 1051.56808.6344 1089.66 1264.92808.6344
 1264.92  1371.6810.1584 1493.52 1737.36810.4632 1775.46 2156.46809.8536
Permanent Ineff=
       T       T       T       F       F       T
Bank Sta=1392.902,1584.795
XS Rating Curve= 0 ,0
Exp/Cntr=0.5,0.3

Type RM Length L Ch R = 1 ,50.04671,16.5561,16.921,15.909
BEGIN DESCRIPTION:
FEMA XS "AX"
PROJECT XS "AX"
END DESCRIPTION:
XS GIS Cut Line= 4
       560041.27      4830747.36        560292.8      4831007.89
       561304.12      4832055.43       562513.94      4833308.58
#Sta/Elev= 30
       0824.7291 46.8459 832.346  55.266825.1119179.6952 824.905187.0981 831.755
189.2829824.9241212.8909825.4771 275.641806.9629342.8329814.2242412.5599 808.115
716.8162808.3149 735.486 816.988 783.524808.2059 1296.45807.86511328.821  808.45
1338.243817.08811386.837 808.8651390.555808.23721428.648805.31521455.243803.8319
1463.536 808.1831531.177 807.118 1570.22808.7325 1576.39 808.6311747.272808.6249
2149.558 810.2122197.077817.01392238.594809.86493357.442812.29993560.049822.9079
#Mann= 10 ,-1 , 0
       0    .052       0212.8909    .036       0342.8329    .046       0
1390.555    .082       01428.648    .037       01463.536    .057       0
1531.177    .082       0 1576.39    .036       01747.272    .052       0
2149.558    .052       0
Levee=-1,1386.837,808.9056,-1,1570.22,808.7106,,
#XS Ineff= 6 ,-1
  388.62   533.4808.6344  579.12 1043.94808.6344 1074.42 1249.68808.6344
 1249.68 1356.36810.1584 1493.52 1737.36810.4632 1783.08 2141.22809.8536
Permanent Ineff=
       T       T       T       F       F       T
Bank Sta=1386.837,1570.22
XS Rating Curve= 0 ,0
Exp/Cntr=0.5,0.3

Type RM Length L Ch R = 1 ,50.03618,102.1601,87.651,63.8169
XS GIS Cut Line= 4
       560034.06      4830773.33       560993.76      4831757.88
       561125.85      4831892.72       562663.63      4833488.75
#Sta/Elev= 30
       0824.3499 202.229825.3719273.3529  806.16 329.237813.9839 1317.21 808.482
1325.345816.8079 1377.23808.82481381.207807.97691389.563804.86491412.959805.1109
1447.357807.24391516.153806.6129 1561.89808.28911562.036808.28941662.438808.4929
1740.306809.04191883.226816.46291932.596809.22811943.236816.71311950.719809.3439
2053.924 809.8812058.493 816.9072135.692810.03892674.402  810.172698.572 818.025
2706.711810.98023356.957812.50593628.589826.66093743.109849.22713779.986845.2369
#Mann= 11 ,-1 , 0
       0    .052       0 202.229    .036       0 329.237    .046       0
1381.207    .082       01412.959    .037       01447.357    .057       0
1516.153    .082       0 1561.89    .036       01662.438    .046       0
1740.306    .052       02135.692    .052       0
Levee=-1,1377.23,808.8264,-1,1562.036,808.2809,,
#XS Ineff= 6 ,-1
  373.38  518.16808.3296  563.88 1036.32808.3296 1059.18 1242.06808.3296
 1767.84 2125.98809.8536 1242.06  1333.5810.1584  1485.9 1737.36810.4632
Permanent Ineff=
       T       T       T       T       F       F
Bank Sta=1377.23,1562.036
XS Rating Curve= 0 ,0
Exp/Cntr=0.3,0.1

Type RM Length L Ch R = 1 ,49.98161,149.69,154.0761,159.105
XS GIS Cut Line= 4
       559993.29      4830838.72       560942.44      4831851.81
       561100.15      4831904.48       562652.37      4833519.52
#Sta/Elev= 30
       0 824.412194.2811825.0381 264.742 806.072310.7741  812.53 818.106807.8861
938.0141807.93491326.781808.17991353.416815.49521398.673   808.31398.858808.2798
1411.673 804.2621417.266804.55491443.069806.24111506.438806.10491560.265808.8286
  1560.7 808.8381661.635808.32991700.939815.84111709.874808.77491750.807809.8759
2042.897 809.6742056.801816.47692066.693809.52012135.955809.87893359.125812.1201
3558.196822.48613604.666 839.3923672.042829.09113768.437854.17093794.556  851.61
#Mann= 13 ,-1 , 0
       0    .052       0194.2811    .036       0310.7741    .046       0
 818.106    .052       0938.0141    .046       01398.673    .082       0
1417.266    .037       01443.069    .057       01506.438    .082       0
  1560.7    .036       01661.635    .046       01750.807    .052       0
2135.955    .052       0
Levee=-1,1398.858,808.3052,-1,1560.265,808.8447,,
#XS Ineff= 6 ,-1
  350.52  502.92808.3296  541.02 1013.46808.3296 1043.94 1226.82808.3296
 1775.46 2125.98809.5488 1226.82 1280.16810.1584 1501.14  1752.6810.4632
Permanent Ineff=
       T       T       T       T       F       F
Bank Sta=1398.858,1560.265
XS Rating Curve= 0 ,0
Exp/Cntr=0.3,0.1

Type RM Length L Ch R = 1 ,49.88569,146.66,150.8879,155.943
XS GIS Cut Line= 4
       559905.53      4830960.77        560888.7      4831985.57
       561050.19      4832067.85       562449.81      4833525.33
#Sta/Elev= 30
       0826.6581157.9532824.1109 166.394 830.551200.6639824.1061225.5639812.2481
282.5231808.1931723.3318807.0601 999.697807.60211448.117807.93261448.474807.7792
1464.411 804.7781479.796 804.3381493.026 805.1281525.625808.30881539.237 808.181
1562.208 808.6351588.734813.16411642.578 806.2741663.047815.35191667.549 809.166
1748.383 808.3762100.451809.41113136.895812.62793143.451824.34593146.082 812.438
3320.698818.50683437.921 814.5713493.295818.9641 3531.01834.26683622.091842.3709
#Mann= 12 ,-1 , 0
       0    .052       0200.6639    .036       0282.5231    .046       0
723.3318    .052       0 999.697    .046       01448.474    .082       0
1464.411    .037       01493.026    .082       01525.625    .036       0
1562.208    .046       01748.383    .052       02100.451    .052       0
Levee=-1,1448.117,807.9578,-1,1539.237,808.1772,,
#XS Ineff= 5 ,-1
  320.04  480.06  807.72  518.16   990.6  807.72 1013.46 1318.26  807.72
 1783.08 2087.88809.5488 1539.24 1744.98810.4632
Permanent Ineff=
       T       T       T       T       F
Bank Sta=1448.117,1539.237
XS Rating Curve= 0 ,0
Exp/Cntr=0.3,0.1

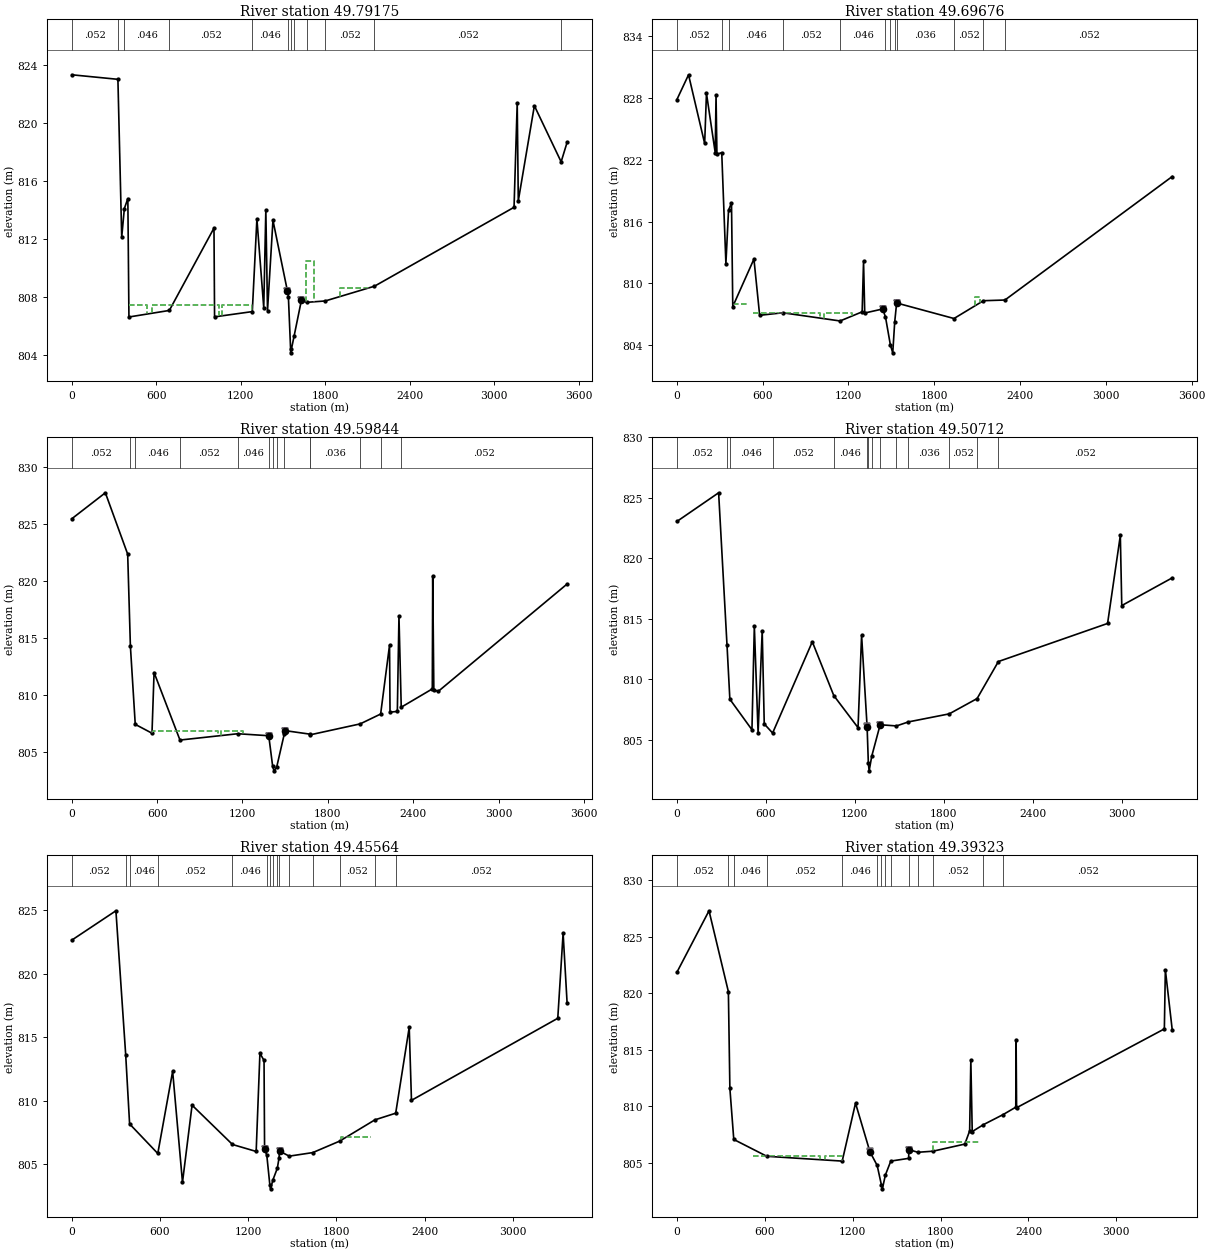
Type RM Length L Ch R = 1 ,49.79175,130.5129,152.5951,184.8191
XS GIS Cut Line= 4
       559747.12      4831037.38       560757.78      4832061.98
       560958.34      4832211.23       562202.49      4833549.19
#Sta/Elev= 30
       0823.3129327.7109822.9999354.7229812.1201373.4221 814.093398.2319814.7801
405.9509 806.619692.6931807.06981009.667812.74711013.867806.62791281.659  806.99
1314.378813.37191362.962807.25921377.759 813.9941389.696807.05311428.353813.2798
1530.666808.4272 1537.99807.99711553.454804.44011554.074804.14811578.778  805.32
1630.765807.79551667.387807.62881799.245 807.7232149.108808.7411 3139.76 814.179
3162.242821.37293169.905814.62493283.979821.17993474.016817.31293516.209818.6511
#Mann= 12 ,-1 , 0
       0    .052       0327.7109    .036       0373.4221    .046       0
692.6931    .052       01281.659    .046       0 1537.99    .082       0
1553.454    .037       01578.778    .082       01667.387    .046       0
1799.245    .052       02149.108    .052       03474.016    .036       0
Levee=-1,1530.666,808.4211,-1,1630.765,807.7993,,
#XS Ineff= 5 ,-1
  403.86   533.4807.4152   571.5 1043.94807.4152  1066.8 1280.16807.4152
    1905 2125.98808.6344 1661.16 1722.12810.4632
Permanent Ineff=
       T       T       T       T       F
Bank Sta=1530.666,1630.765
XS Rating Curve= 0 ,0
Exp/Cntr=0.3,0.1

Type RM Length L Ch R = 1 ,49.69676,155.5221,157.9269,161.245
XS GIS Cut Line= 5
       559736.28       4831102.5       560708.38      4832113.19
       560751.27      4832335.64        561016.8      4832631.27
       561885.44       4833777.3
#Sta/Elev= 30
       0 827.838 81.3261830.2402194.0591823.5739206.6901 828.437 267.846822.6899
273.6689828.2339279.8899822.5491313.5151822.6838 342.636811.9311360.9762 817.092
 381.752 817.819390.7091807.7581 538.684 812.363578.6909806.9059740.6579807.1519
1141.126806.35691295.536 807.243  1305.3 812.1631313.659807.12811439.006807.5199
1458.789 806.7381493.095804.02011509.504803.26511523.234 806.2531536.744 808.115
1539.176808.09221937.905 806.5952143.682 808.3222294.031808.38813464.256 820.371
#Mann= 12 ,-1 , 0
       0    .052       0313.5151    .036       0360.9762    .046       0
740.6579    .052       01141.126    .046       01458.789    .082       0
1493.095    .037       01523.234    .082       01536.744    .036       0
1937.905    .052       02143.682    .046       02294.031    .052       0
Levee=-1,1439.006,807.5219,-1,1539.176,808.0919,,
#XS Ineff= 4 ,-1
  396.24   495.3808.0248   533.4  998.22807.1104  1028.7 1226.82807.1104
 2087.88 2118.36808.6344
Permanent Ineff=
       T       T       T       T
Bank Sta=1439.006,1539.176
XS Rating Curve= 0 ,0
Exp/Cntr=0.3,0.1

Type RM Length L Ch R = 1 ,49.59844,166.597,146.681,111.8589
XS GIS Cut Line= 5
       559586.88      4831210.81       560566.38      4832187.35
       560587.35      4832375.34        560896.7      4832716.61
       561736.94       4833897.1
#Sta/Elev= 30
       0 825.478236.2499827.7661 393.188822.3708 412.256814.2869446.3781807.4091
564.0251806.6309578.6841811.9658 760.793806.02891167.478806.58491384.527806.4094
1384.748806.41091412.255803.73111421.614803.32291440.458803.64211494.079806.5651
1501.204806.85521674.441 806.5481677.575806.49292027.505  807.452171.307808.3159
2233.923814.37022237.377808.47892288.714808.5491 2300.13816.91492316.153808.9161
2534.485 810.5252537.432820.44692545.294810.41992576.775 810.3133481.889 819.744
#Mann= 14 ,-1 , 0
       0    .052       0 412.256    .036       0446.3781    .046       0
 760.793    .052       01167.478    .046       01384.748    .082       0
1412.255    .037       01440.458    .082       01494.079    .036       0
1674.441    .057       01677.575    .036       02027.505    .052       0
2171.307    .046       02316.153    .052       0
Levee=-1,1384.527,806.4246,-1,1501.204,806.8665,,
#XS Ineff= 4 ,-1
   457.2  518.16806.8056  563.88  1028.7806.8056 1051.56 1203.96806.8056
 2042.16 2087.88807.4152
Permanent Ineff=
       T       T       T       T
Bank Sta=1384.527,1501.204
XS Rating Curve= 0 ,0
Exp/Cntr=0.3,0.1

Type RM Length L Ch R = 1 ,49.50712,86.362,82.7011,75.3551
BEGIN DESCRIPTION:
FEMA XS "AW"
PROJECT XS "AW"
END DESCRIPTION:
XS GIS Cut Line= 6
       559534.96      4831414.07       559858.95      4831722.03
       560605.72      4832459.14        560845.9      4832730.37
        560859.7      4832752.46       561630.98      4833986.51
#Sta/Elev= 30
       0823.0521281.2609 825.421337.6611812.8629 357.032808.3641505.9729805.8422
 522.056814.4052547.4141 805.573575.1241814.0159588.8971 806.324645.2631805.5709
  912.94813.11191057.737 808.6671221.229 806.0151245.225813.64721282.177 806.147
1282.339806.1074 1290.86803.06821296.131802.44781313.906803.66711369.677 806.223
1370.015 806.2561480.565806.15791560.722806.49021836.261807.15492023.962 808.418
2167.577811.47822903.857814.62492989.785 821.892 2999.57816.10293339.873 818.392
#Mann= 14 ,-1 , 0
       0    .052       0337.6611    .036       0 357.032    .046       0
645.2631    .052       01057.737    .046       01282.177    .082       0
 1290.86    .037       01313.906    .082       01370.015    .036       0
1480.565    .057       01560.722    .036       01836.261    .052       0
2023.962    .046       02167.577    .052       0
Levee=-1,1282.339,806.1381,-1,1369.677,806.2478,,
#XS Ineff= 4 ,-1
  358.14  411.48807.1104   457.2   914.4 806.196  944.88 1082.04806.5008
 1844.04 1935.48807.1104
Permanent Ineff=
       T       T       T       T
Bank Sta=1282.339,1369.677
XS Rating Curve= 0 ,0
Exp/Cntr=0.3,0.1

Type RM Length L Ch R = 1 ,49.45564,101.1311,100.2481,99.5599
XS GIS Cut Line= 5
       559471.47       4831428.1       560395.53      4832372.82
       560566.98      4832491.16       560788.74      4832757.66
       561592.51      4834013.74
#Sta/Elev= 30
       0822.6299300.3219824.9409  366.75 813.624393.3551808.1769 584.981805.8519
686.0231 812.314752.9441803.5881818.0851809.65221092.839806.55991253.897806.0119
1279.397813.73711307.407813.16581311.061806.20781326.226 805.7081347.106803.3531
1351.903803.07211367.986 803.7821397.959804.69791409.409805.5121 1412.58806.0403
1478.785 805.6441638.417 805.922 1820.95 806.8222061.072808.49692202.518809.0209
2294.477 815.7712309.792810.03193304.553 816.4863340.812 823.1743367.763817.7242
#Mann= 15 ,-1 , 0
       0    .052       0  366.75    .036       0393.3551    .046       0
 584.981    .052       01092.839    .046       01326.226    .082       0
1347.106    .037       01367.986    .057       01397.959    .082       0
1409.409    .036       01478.785    .057       01638.417    .036       0
 1820.95    .052       02061.072    .046       02202.518    .052       0
Levee=-1,1311.061,806.2051,-1,1412.58,806.0344,,
#XS Ineff= 4 ,-1
  388.62  441.96 806.196  487.68  944.88805.8912  982.98  1104.9805.8912
  1828.8 2034.54807.1104
Permanent Ineff=
       T       T       T       T
Bank Sta=1311.061,1412.58
XS Rating Curve= 0 ,0
Exp/Cntr=0.3,0.1

Type RM Length L Ch R = 1 ,49.39323,126.602,144.595,154.1809
XS GIS Cut Line= 4
       559401.73      4831453.84        560334.1      4832452.91
       560483.65      4832552.15       561532.93      4834058.43
#Sta/Elev= 30
       0821.8411219.1771 827.279 351.364820.1269361.6199811.5712 388.225807.0571
 613.787805.5681 1128.49805.14291219.422810.2669 1317.83805.96591367.241804.7579
1395.648803.06511402.771802.68991423.378 803.9131460.239805.14421581.644 805.384
1584.326806.15491644.883805.92291747.688806.01711965.677 806.6481998.577807.8121
2006.636814.08792016.183807.75292092.288808.36322227.896 809.2622313.462809.9109
2315.753 815.8842319.044809.86223327.895816.83293334.713822.0569 3381.75816.7408
#Mann= 14 ,-1 , 0
       0    .052       0 351.364    .036       0 388.225    .046       0
 613.787    .052       0 1128.49    .046       01367.241    .082       0
1395.648    .037       01423.378    .057       01460.239    .036       0
1581.644    .057       01644.883    .036       01747.688    .052       0
2092.288    .046       02227.896    .052       0
Levee=-1,1317.83,805.9979,-1,1584.326,806.1442,,
#XS Ineff= 4 ,-1
  411.48  472.44 806.196  518.16  975.36805.5864 1013.46 1127.76805.5864
 1744.98 2072.64806.8056
Permanent Ineff=
       T       T       T       T
Bank Sta=1317.83,1584.326
XS Rating Curve= 0 ,0
Exp/Cntr=0.3,0.1