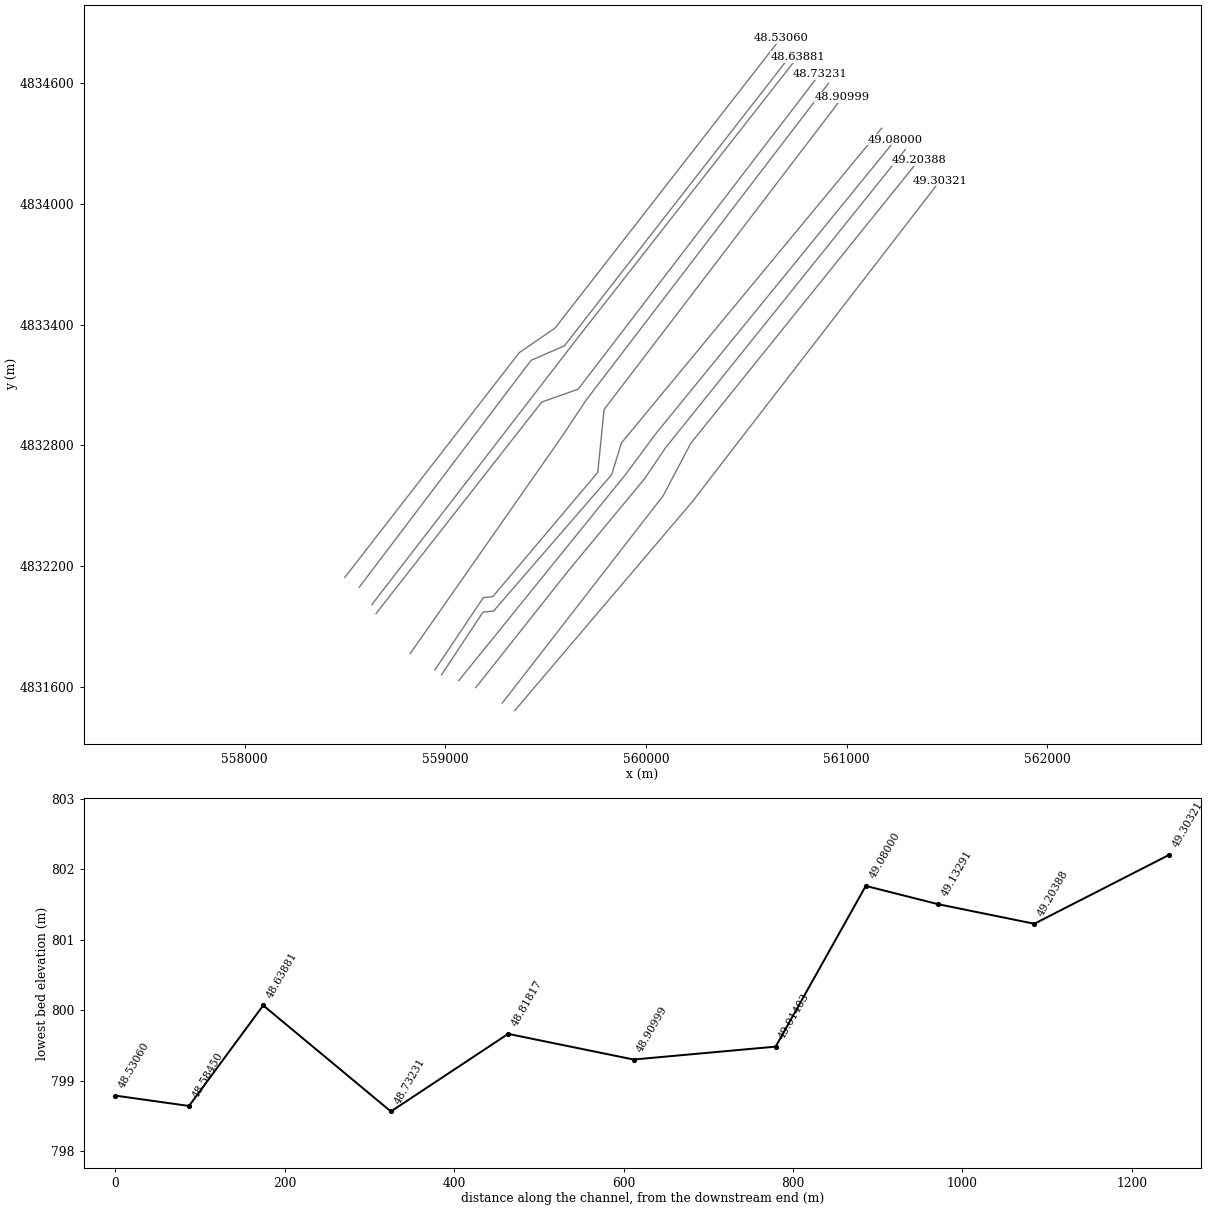
HEC-RAS study Boise2.prj: BoiseRiver_All_reaches

--- Boise2.g01 (geometry) --- (continued)

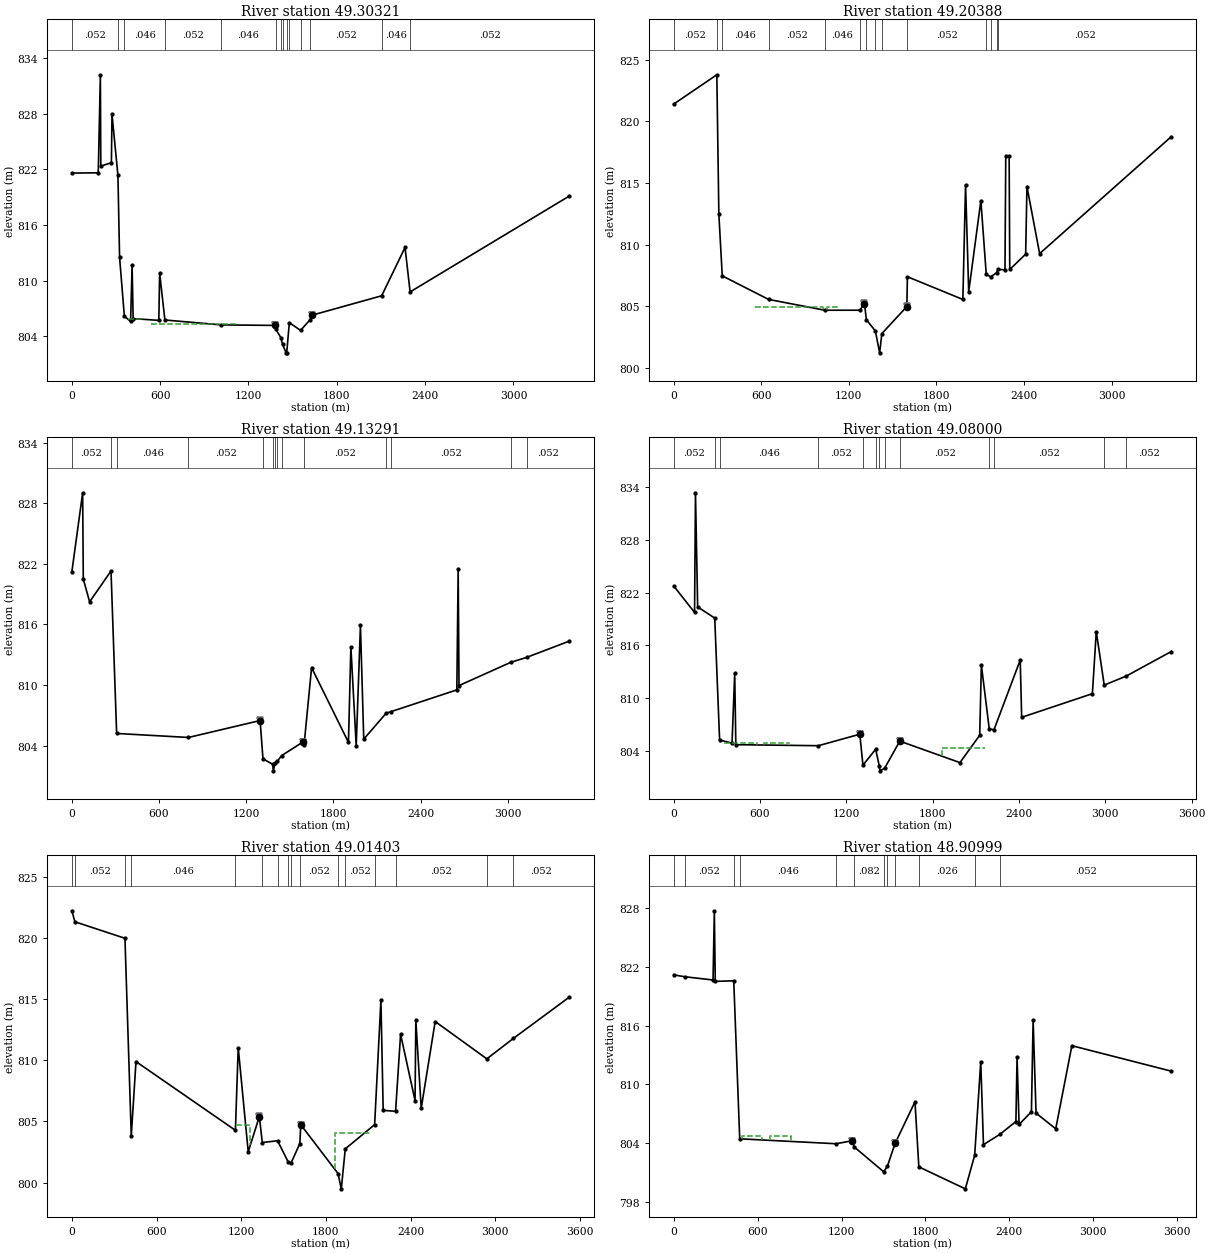
Type RM Length L Ch R = 1 ,49.30321,149.4489,159.5591,168.1131
XS GIS Cut Line= 4
       559346.37      4831481.95        560234.9      4832525.12
       560383.99      4832718.94       561464.75      4834115.24
#Sta/Elev= 30
       0 821.593179.3769821.6219193.7339832.1951196.6841822.3431 268.619822.7141
 272.692827.9191 313.036821.3439 324.224812.5029 356.645806.1591399.1801 805.594
409.2449811.6541416.4672805.9009590.9581 805.704 596.311810.7891 632.157805.7479
1014.832805.21911378.525805.16411385.337804.74521420.156803.84391431.312 803.116
1455.862 802.2051459.708 802.2251477.625805.46121553.686 804.6261618.931 805.783
1628.662806.25172104.711 808.3582263.667813.56792298.077808.77623380.519 819.125
#Mann= 14 ,-1 , 0
       0    .052       0 313.036    .036       0 356.645    .046       0
 632.157    .052       01014.832    .046       01385.337    .082       0
1420.156    .057       01431.312    .037       01459.708    .057       0
1477.625    .082       01553.686    .057       01618.931    .052       0
2104.711    .046       02298.077    .052       0
Levee=-1,1378.525,805.1901,-1,1628.662,806.26,,
#XS Ineff= 4 ,-1
     381  487.68805.8912  541.02  998.22805.2816  1028.7 1112.52805.2816
 1668.78 2011.68805.2816
Permanent Ineff=
       T       T       T       T
Bank Sta=1378.525,1628.662
XS Rating Curve= 0 ,0
Exp/Cntr=0.3,0.1

Type RM Length L Ch R = 1 ,49.20388,121.87,113.9921,102.1229
XS GIS Cut Line= 4
       559283.77      4831518.72       560085.71      4832549.77
       560222.69      4832809.74       561358.64      4834217.28
#Sta/Elev= 30
       0821.4031 295.542823.7812309.4961  812.46332.6981  807.47 650.057 805.559
1035.591804.68121274.888804.68291307.092805.22051320.225803.90911381.583802.9998
1411.059 801.2251426.243802.78891597.487804.98021601.109   807.41981.077805.5559
1999.563814.86212021.105806.17322104.452813.57312141.403 807.5812172.764 807.396
2211.965807.72222220.828807.99922269.665 807.9552275.014817.21212298.157817.1621
2302.315807.98612411.369809.23122420.173814.71092507.049809.27393408.792 818.759
#Mann= 14 ,-1 , 0
       0    .052       0 295.542    .036       0332.6981    .046       0
 650.057    .052       01035.591    .046       01274.888    .052       0
1320.225    .082       01381.583    .037       01426.243    .082       0
1601.109    .052       02141.403    .046       02172.764    .052       0
2211.965    .046       02220.828    .052       0
Levee=-1,1307.092,805.2298,-1,1597.487,804.986,,
#XS Ineff= 4 ,-1
  350.52  502.92805.2816  556.26 1021.08804.9768 1051.56 1127.76804.9768
 1645.92  2133.6 804.672
Permanent Ineff=
       T       T       T       T
Bank Sta=1307.092,1597.487
XS Rating Curve= 0 ,0
Exp/Cntr=0.3,0.1

Type RM Length L Ch R = 1 ,49.13291,90.123,84.995,81.028
BEGIN DESCRIPTION:
FEMA XS "AV"
PROJECT XS "AV"
END DESCRIPTION:
XS GIS Cut Line= 6
       559152.21      4831596.07       559615.82      4832179.94
       559994.72      4832636.49       560097.73      4832788.67
       560389.67      4833151.02       561291.19      4834269.92
#Sta/Elev= 30
       0821.2089 74.3361829.0349 78.7119820.4982122.1709 818.235 269.534821.2922
308.2351805.2051802.4381 804.8081295.671806.48321315.478802.69381382.604802.1489
1386.403801.50391400.071802.32811414.113802.44391443.567803.00811588.325804.3385
1598.369 804.067    1650811.72391903.906 804.3231920.482813.79321957.229 803.992
 1986.35 815.9062009.116804.64392163.124807.20492194.975 807.3562649.876809.5201
2658.963 821.476 2664.85809.94683020.701812.2469 3129.61 812.7333424.833814.3522
#Mann= 14 ,-1 , 0
       0    .052       0 269.534    .036       0308.2351    .046       0
802.4381    .052       01315.478    .082       01382.604    .037       0
1400.071    .057       01414.113    .037       01443.567    .082       0
1598.369    .052       02163.124    .046       02194.975    .052       0
3020.701    .036       0 3129.61    .052       0
Levee=-1,1295.671,806.5344,-1,1588.325,804.3733,,
#XS Ineff= 4 ,-1
  335.28  541.02804.9768  594.36 1051.56804.3672 1082.04 1234.44804.3672
  1714.5 2156.46804.3672
Permanent Ineff=
       T       T       T       T
Bank Sta=1295.671,1588.325
XS Rating Curve= 0 ,0
Exp/Cntr=0.3,0.1

Type RM Length L Ch R = 1 ,49.08000,73.5089,106.3789,81.3249
XS GIS Cut Line= 4
       559066.93      4831630.26       559900.72      4832658.55
        560049.9      4832859.16       561242.11      4834318.49
#Sta/Elev= 30
       0822.7579145.1131 819.752 151.464833.3421166.6439820.3811285.3071819.1088
319.1982805.2582 405.637804.9171424.1591812.8782431.9019 804.7331005.663804.6171
1293.526805.92091315.523802.40611403.709 804.212  1429.3802.30311433.267 801.762
1465.958802.0571 1571.78 805.1421571.948805.13381989.446802.69512126.949   805.8
2138.454 813.791 2193.23806.53192226.083806.42312408.493814.34212418.576807.8389
2910.092 810.5262937.157 817.5722992.435 811.4983145.981  812.533458.261815.3102
#Mann= 13 ,-1 , 0
       0    .052       0285.3071    .036       0319.1982    .046       0
1005.663    .052       01315.523    .082       01403.709    .057       0
  1429.3    .037       01465.958    .082       0 1571.78    .052       0
 2193.23    .046       02226.083    .052       02992.435    .036       0
3145.981    .052       0
Levee=-1,1293.526,805.9308,-1,1571.948,805.1506,,
#XS Ineff= 4 ,-1
  350.52  579.12804.9768  624.84   800.1804.9768 1112.52 1249.68804.3672
  1866.9 2164.08804.3672
Permanent Ineff=
       T       T       T       T
Bank Sta=1293.526,1571.948
XS Rating Curve= 0 ,0
Exp/Cntr=0.3,0.1

Type RM Length L Ch R = 1 ,49.01403,86.0841,167.7741,187.7781
XS GIS Cut Line= 6
       558980.86      4831658.65       559188.05      4831971.17
       559240.23      4831976.14       559828.61      4832653.97
       559877.62      4832812.08       561174.11      4834376.36
#Sta/Elev= 30
       0822.2111 21.5091 821.311376.2329819.9629421.0142803.8201454.4659809.8841
1159.022 804.2661178.925 811.0211249.797 802.5071328.748805.3922 1349.43 803.269
1458.034803.41111531.729  801.711552.885801.57621615.649803.18611622.261804.7217
1886.452800.72911909.379799.4819 1937.58 802.7532145.619 804.7252190.176814.9059
2206.281805.89912294.067805.81592329.505812.11492432.099806.69322437.568813.2679
2475.704806.06592574.708  813.16 2940.75810.1078 3128.69811.77593526.079815.1611
#Mann= 16 ,-1 , 0
       0    .036       0 21.5091    .052       0376.2329    .036       0
421.0142    .046       01159.022    .052       0 1349.43    .082       0
1458.034    .057       01531.729    .037       01552.885    .082       0
1615.649    .052       01886.452    .026       0 1937.58    .052       0
2145.619    .046       02294.067    .052       0 2940.75    .036       0
 3128.69    .052       0
Levee=-1,1328.748,805.4249,-1,1622.261,804.7269,,
#XS Ineff= 4 ,-1
  441.96  632.46 804.672  678.18   838.2 804.672 1165.86 1264.92 804.672
1864.245 2118.36804.0624
Permanent Ineff=
       T       T       T       T
Bank Sta=1328.748,1622.261
XS Rating Curve= 0 ,0
Exp/Cntr=0.3,0.1

Type RM Length L Ch R = 1 ,48.90999,213.727,148.0661,129.8329
XS GIS Cut Line= 6
        558948.5      4831684.27       559189.43      4832042.89
       559236.64      4832047.86       559759.62      4832665.59
       559791.07      4832977.98       560978.75      4834530.36
#Sta/Elev= 30
       0 821.191 78.2641 821.002281.4209820.6679 290.642827.7499297.4062 820.525
429.3861820.5859472.0749804.41811161.156 803.9131278.066804.22551291.003 803.582
 1501.96801.03781527.574801.59991584.849 804.0271585.338804.02081725.199 808.205
1752.761 801.5462085.218 799.2992151.909802.73192195.454812.30692214.777803.8188
2332.628804.87712446.819806.18812455.008812.77292469.437805.88512557.646807.1881
2569.876816.56292590.808807.04612731.454805.44012846.871813.94493557.461811.3401
#Mann= 12 ,-1 , 0
       0    .036       0 78.2641    .052       0429.3861    .036       0
472.0749    .046       01161.156    .052       01291.003    .082       0
 1501.96    .037       01527.574    .082       01584.849    .052       0
1752.761    .026       02151.909    .046       02332.628    .052       0
Levee=-1,1278.066,804.23,-1,1585.338,804.0258,,
#XS Ineff= 3 ,-1
  487.68  632.46 804.672   685.8   838.2 804.6721737.031  2209.8803.7576
Permanent Ineff=
       T       T       T
Bank Sta=1278.066,1585.338
XS Rating Curve= 0 ,0
Exp/Cntr=0.3,0.1

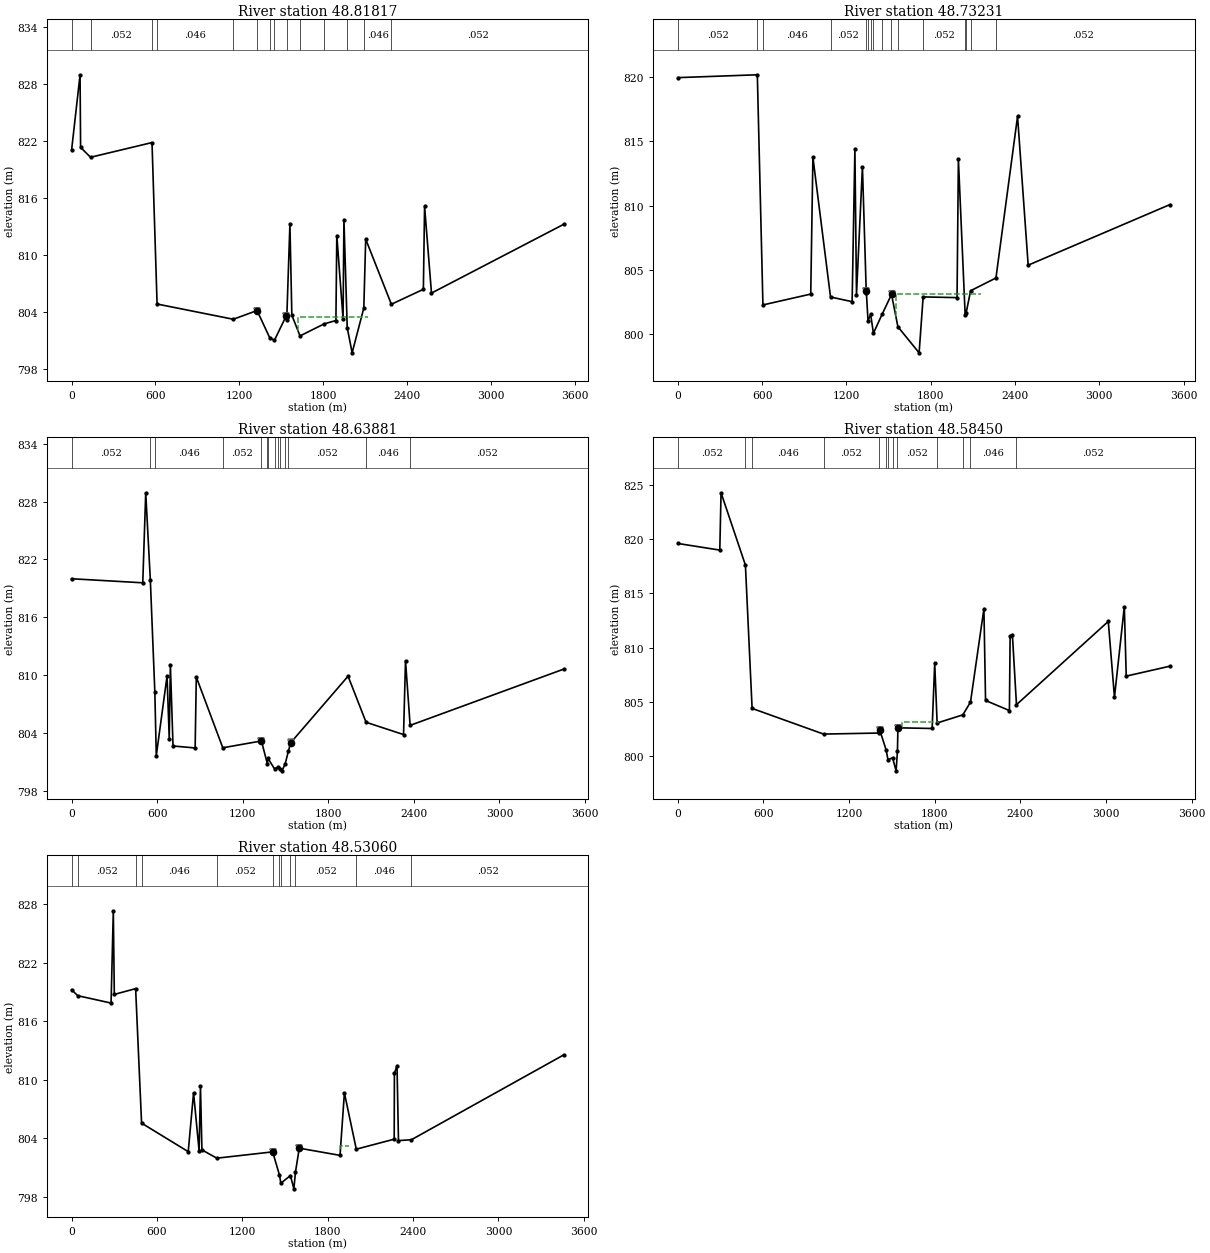
Type RM Length L Ch R = 1 ,48.81817,183.9752,138.446,100.4231
XS GIS Cut Line= 4
       558824.98      4831764.36       559581.74      4832844.68
       559701.55      4833024.68         560909.       4834599.5
#Sta/Elev= 30
       0821.0419 60.5601828.9951 64.4189821.3351135.5071820.2921575.1131821.8442
 611.366804.81191156.562 803.2051325.033804.1191 1326.21 804.1231417.369801.2378
1450.806800.99491535.293803.57481538.446803.17791561.227813.25211575.037 803.636
1633.477801.44821805.236802.7109 1890.17 803.074 1896.49  812.041941.249803.2611
1947.476813.70511971.013802.32992006.118799.66292089.625 804.3942103.125811.6541
2286.727804.78812515.571806.36492524.172815.11112573.517 805.9653519.666813.2259
#Mann= 14 ,-1 , 0
       0    .036       0135.5071    .052       0575.1131    .036       0
 611.366    .046       01156.562    .052       0 1326.21    .082       0
1417.369    .037       01450.806    .082       01538.446    .052       0
1633.477    .026       01805.236    .052       01971.013    .026       0
2089.625    .046       02286.727    .052       0
Levee=-1,1325.033,804.1264,-1,1535.293,803.59,,
#XS Ineff= 1 ,-1
1619.915 2118.36803.4528
Permanent Ineff=
       T
Bank Sta=1325.033,1535.293
XS Rating Curve= 0 ,0
Exp/Cntr=0.3,0.1

Type RM Length L Ch R = 1 ,48.73231,62.9631,150.78,161.099
XS GIS Cut Line= 4
       558655.22      4831963.92        559480.4      4833014.98
       559661.75      4833078.93       560864.78        4834645.
#Sta/Elev= 30
       0 819.937565.7969 820.158 605.736 802.282945.9691 803.126961.4111 813.749
1086.751 802.8991240.573802.53591260.284814.37411271.683 803.0841313.901812.9979
1340.913803.36311342.148 803.212 1353.71801.05651372.278 801.5491392.247 800.086
1454.257801.56091520.821 803.0951521.059803.09481566.365 800.5881717.397 798.562
1746.089 802.9061987.373802.85111996.902813.59012045.279 801.4642051.585801.6359
2083.816803.38332264.241 804.3772418.073816.9302 2493.64805.37093503.389  810.08
#Mann= 16 ,-1 , 0
       0    .052       0565.7969    .036       0 605.736    .046       0
1086.751    .052       01342.148    .082       0 1353.71    .037       0
1372.278    .082       01392.247    .037       01454.257    .082       0
1520.821    .052       01566.365    .026       01746.089    .052       0
2045.279    .026       02051.585    .052       02083.816    .046       0
2264.241    .052       0
Levee=-1,1340.913,803.3644,-1,1521.059,803.0931,,
#XS Ineff= 1 ,-1
1552.746 2156.46 803.148
Permanent Ineff=
       T
Bank Sta=1340.913,1521.059
XS Rating Curve= 0 ,0
Exp/Cntr=0.3,0.1

Type RM Length L Ch R = 1 ,48.63881,157.1561,87.569,62.1109
BEGIN DESCRIPTION:
FEMA XS "AU"
PROJECT XS "AU"
END DESCRIPTION:
XS GIS Cut Line= 6
       558634.04      4832008.35       559166.38      4832696.33
       559444.35      4833055.56       559652.43      4833325.25
       559926.78      4833674.65       560755.83      4834730.52
#Sta/Elev= 30
       0819.9949 499.088 819.574 519.866 828.913 552.229 819.855583.6371808.2949
593.9071801.6411 669.431   809.9684.7811803.4058692.6711811.0759711.3428 802.646
866.4169802.4399874.4791809.7991 1060.28802.45921331.218803.16691331.263803.1645
1372.635800.81111377.122801.36181423.026800.27011448.912800.47611463.063800.2899
 1475.86800.06711497.922800.80191520.011802.09191535.982802.97751938.809809.8859
2064.992805.10512327.713803.83112341.513811.49312373.896 804.7833451.433810.6229
#Mann= 14 ,-1 , 0
       0    .052       0 552.229    .036       0583.6371    .046       0
 1060.28    .052       01331.218    .082       01372.635    .037       0
1377.122    .082       01423.026    .037       01448.912    .082       0
1463.063    .037       01497.922    .082       01520.011    .052       0
2064.992    .046       02373.896    .052       0
Levee=-1,1331.263,803.1572,-1,1535.982,803.0109,,
#XS Ineff= 1 ,-1
 1569.72 2065.02 803.148
Permanent Ineff=
       T
Bank Sta=1331.263,1535.982
XS Rating Curve= 0 ,0
Exp/Cntr=0.3,0.1

Type RM Length L Ch R = 1 ,48.58450,67.5019,86.9131,91.6189
XS GIS Cut Line= 4
       558571.78      4832095.22       559427.13       4833222.3
       559593.28      4833294.63       560733.34      4834754.61
#Sta/Elev= 30
       0819.5819293.9881 818.972302.7801824.2512 473.476817.5931 520.375804.3892
1020.749802.02611406.289802.12081414.629802.40631459.396800.5609  1472.5799.6528
1504.226799.84611529.297  798.641538.711800.46611541.944802.60321781.683802.5411
1799.757808.54991816.658803.04621996.668803.79512050.465804.97012144.489813.5718
2155.961805.1201 2323.16 804.1922328.092 811.0642343.972811.19012372.552 804.733
3015.788 812.4023059.122 805.4243128.269 813.7663141.561807.36313448.477 808.283
#Mann= 13 ,-1 , 0
       0    .052       0 473.476    .036       0 520.375    .046       0
1020.749    .052       01406.289    .082       01459.396    .037       0
  1472.5    .082       01504.226    .037       01538.711    .052       0
1816.658    .046       01996.668    .052       02050.465    .046       0
2372.552    .052       0
Levee=-1,1414.629,802.4256,-1,1541.944,802.6177,,
#XS Ineff= 1 ,-1
 1569.72  1828.8 803.148
Permanent Ineff=
       T
Bank Sta=1414.629,1541.944
XS Rating Curve= 0 ,0
Exp/Cntr=0.3,0.1

Type RM Length L Ch R = 1 ,48.53060,45.043,170.4871,172.0971
XS GIS Cut Line= 4
       558499.46      4832143.62       559368.61      4833260.69
       559546.82      4833382.82       560671.35      4834823.76
#Sta/Elev= 30
       0819.2149 43.2401 818.608277.4811 817.851 293.263827.3211300.2701 818.737
450.0451 819.332491.9009  805.53 819.727 802.603857.2141808.6249896.1221802.7161
 905.811809.3181915.9858802.7871 1020.47 801.9331412.876802.57891413.091802.5829
1461.175800.19121470.515799.36081537.969 800.1461562.287798.78691573.253 800.491
1600.203802.95981886.586 802.2221917.349808.63292000.813802.85782267.327 803.882
2268.734 810.6362287.055811.43012297.407 803.7392387.896803.82323459.221812.5361
#Mann= 12 ,-1 , 0
       0    .036       0 43.2401    .052       0450.0451    .036       0
491.9009    .046       0 1020.47    .052       01413.091    .082       0
1461.175    .037       01470.515    .082       01537.969    .037       0
1573.253    .052       02000.813    .046       02387.896    .052       0
Levee=-1,1412.876,802.5902,-1,1600.203,802.959,,
#XS Ineff= 2 ,-1
 1592.58 1859.28802.2336 1889.76 1950.72 803.148
Permanent Ineff=
       T       T
Bank Sta=1412.876,1600.203
XS Rating Curve= 0 ,0
Exp/Cntr=0.3,0.1