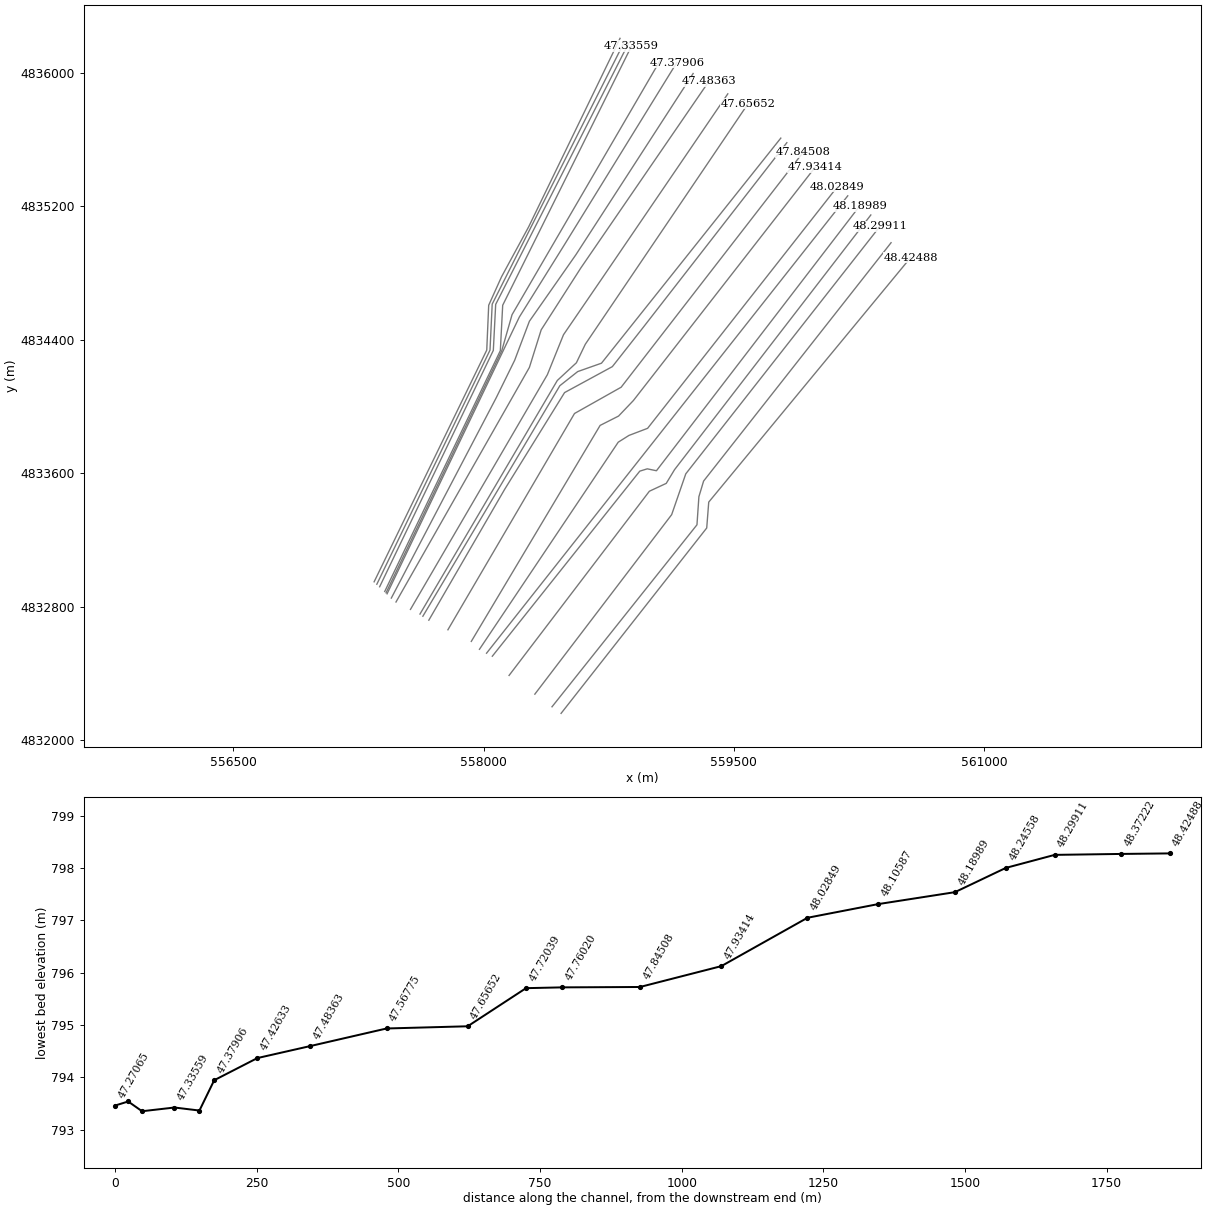
HEC-RAS study Boise2.prj: BoiseRiver_All_reaches

--- Boise2.g01 (geometry) --- (continued)

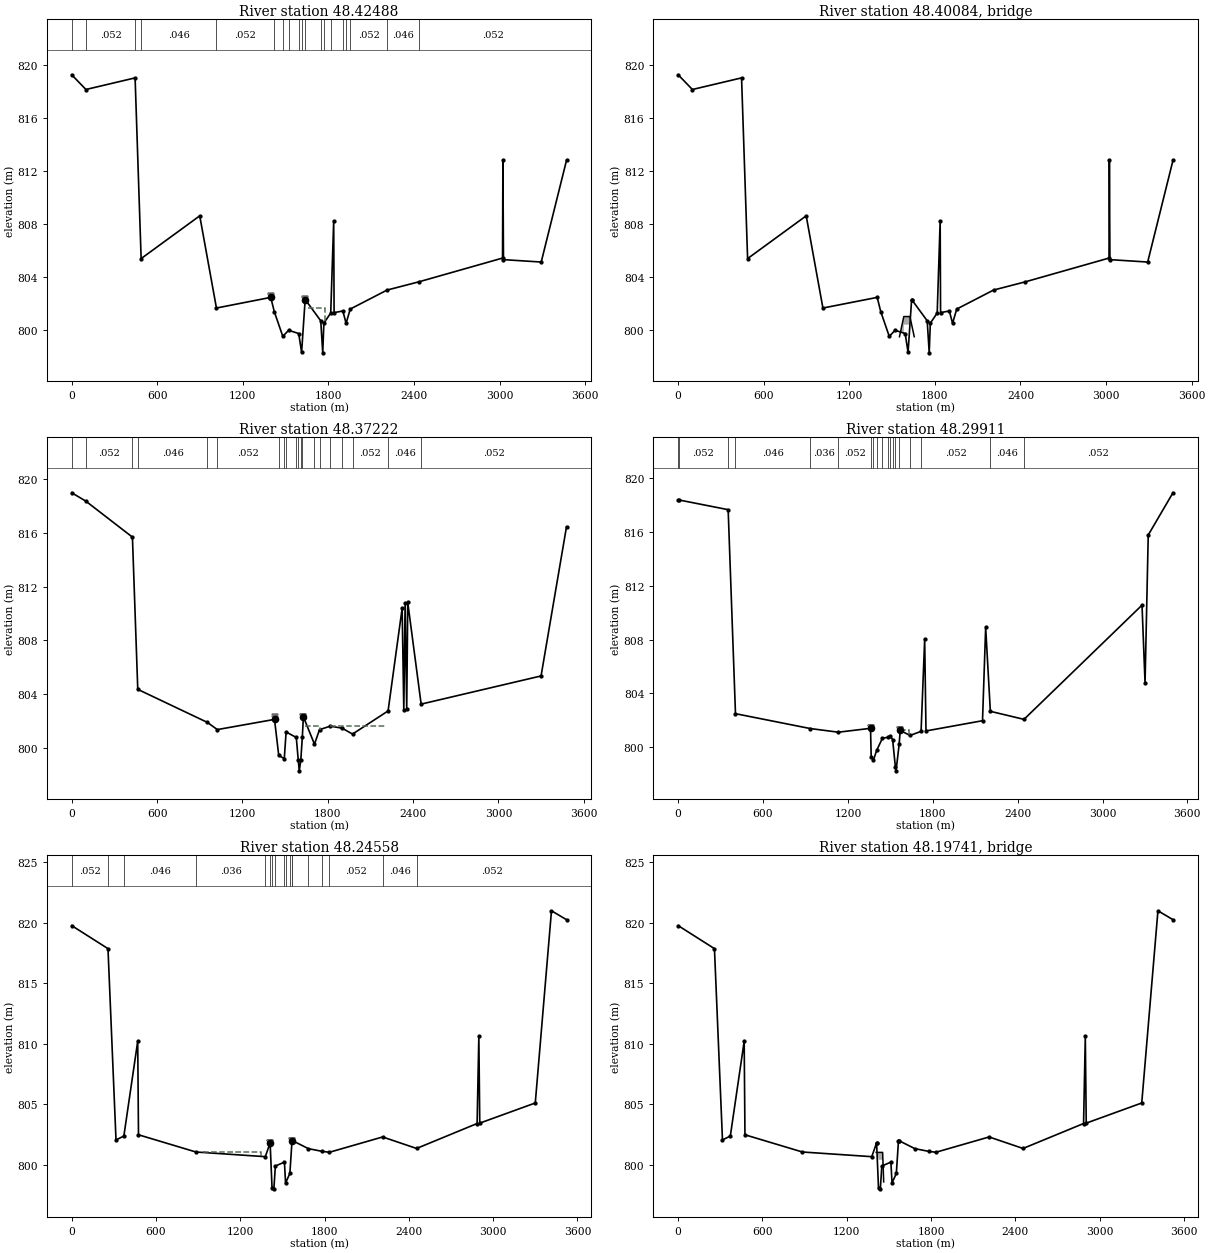
Type RM Length L Ch R = 1 ,48.42488,62.965,84.9161,94.965
XS GIS Cut Line= 5
       558464.43      4832160.24       559337.25      4833271.27
        559349.3      4833426.41       559436.23      4833531.69
       560559.31      4834891.97
#Sta/Elev= 30
       0 819.254 99.5599818.1429444.3789819.0198486.7001 805.387  897.55 808.613
1014.682801.65691395.354  802.461420.208801.38681479.875  799.521520.809 799.979
1591.576 799.7331611.697798.30681636.673802.29911636.864802.29881745.947800.6949
1760.009 798.2771767.802800.51211816.013801.28421836.776808.23391839.565801.3101
1901.011 801.4351923.559800.50511953.046801.58012210.793 803.0122434.543 803.636
3020.573805.4261 3023.12812.84193027.121805.30813291.715 805.1273468.999812.7949
#Mann= 19 ,-1 , 0
       0    .036       0 99.5599    .052       0444.3789    .036       0
486.7001    .046       01014.682    .052       01420.208    .082       0
1479.875    .037       01520.809    .082       01591.576    .037       0
1611.697    .082       01636.673    .052       01745.947    .026       0
1767.802    .036       01816.013    .052       01901.011    .036       0
1923.559    .026       01953.046    .052       02210.793    .046       0
2434.543    .052       0
Levee=-1,1395.354,802.6,-1,1636.864,802.3098,,
#XS Ineff= 2 ,-1
 1653.541773.125 801.624 1821.18  2095.5801.9288
Permanent Ineff=
       T       T
Bank Sta=1395.354,1636.864
XS Rating Curve= 0 ,0
Exp/Cntr=0.3,0.1

Type RM Length L Ch R = 3 ,48.40084,,,
BEGIN DESCRIPTION:
Greenbelt Pathway Walk Bridge (RM 48.40)
END DESCRIPTION:
Bridge Culvert--1,0,-1,-1, 0
Deck Dist Width WeirC Skew NumUp NumDn MinLoCord MaxHiCord MaxSubmerge Is_Ogee
33.528,4.572,1.44,0, 6, 6, , , 0.95, 0, 0,0,,
1551.4321581.9121581.9121624.5841624.5841655.064
799.4904801.0144801.0144801.0144801.0144799.4904
799.4904799.4904800.4048800.4048799.4904799.4904
1551.4321581.9121581.9121624.5841624.5841655.064
799.4904801.0144801.0144801.0144801.0144799.4904
799.4904799.4904800.4048800.4048799.4904799.4904
BR Coef=-1 , 0 , 0 ,1.25, 0 ,,,0.8,-1,2,0,
WSPro=,,,, 1 ,,,, 0 ,,,, 0 ,,,,-1 ,-1 ,-1 , 0 , 0 , 0 , 0 , 0
BC Design=,, 0 ,, 0 ,,,,,,
BC Use User HTab Curves=0
BC User HTab FreeFlow(D)= 0

Type RM Length L Ch R = 1 ,48.37222,163.9589,117.9079,116.946
XS GIS Cut Line= 5
       558410.05      4832199.72       559278.82      4833290.43
       559290.35      4833458.68       559318.54      4833552.51
       560442.07      4834980.95
#Sta/Elev= 30
       0 818.994  98.786 818.374426.8051815.6881464.3649 804.341 953.775 801.877
1023.691801.34111425.626 802.1021455.359799.41481494.317799.17711507.187801.1649
1578.842800.75291592.408799.08721599.577 798.2671610.495799.05521621.278  800.79
1628.726802.29771706.499800.25391741.978 801.3351817.807 801.5991901.984801.4429
1973.987801.00712224.083802.73112322.953810.38482334.597 802.8062343.935810.7939
  2355.1802.88192362.431810.8159 2456.44803.24013299.518805.3401 3478.39816.4601
#Mann= 20 ,-1 , 0
       0    .036       0  98.786    .052       0426.8051    .036       0
464.3649    .046       0 953.775    .036       01023.691    .052       0
1455.359    .037       01494.317    .082       01507.187    .057       0
1578.842    .082       01592.408    .037       01610.495    .082       0
1621.278    .052       01706.499    .026       01741.978    .036       0
1817.807    .052       01901.984    .036       01973.987    .052       0
2224.083    .046       0 2456.44    .052       0
Levee=-1,1425.626,802.3,-1,1628.726,802.2885,,
#XS Ineff= 2 ,-1
  1638.31743.989 801.624 1813.56  2209.8 801.624
Permanent Ineff=
       T       T
Bank Sta=1425.626,1628.726
XS Rating Curve= 0 ,0
Exp/Cntr=0.3,0.1

Type RM Length L Ch R = 1 ,48.29911,198.8561,86.309,77.7341
XS GIS Cut Line= 4
       558307.27      4832275.47       559127.19      4833351.23
       559211.75      4833595.83       560376.37      4835080.25
#Sta/Elev= 30
       0818.3758   2.799818.3959353.3141 817.669405.0871802.4991932.6091 801.396
1132.353 801.1221359.816801.40991364.631799.30991380.023 799.0241403.111799.7659
1444.389800.67911484.968800.7432 1500.01800.82911516.101800.57311535.691 798.522
 1540.31 798.2491562.277800.2162 1569.68801.25371638.886800.8809 1717.25801.1821
1742.748808.03311752.004 801.2152151.658801.97612173.901808.91392206.987802.6749
2444.862 802.0773279.371810.56993300.761804.7921 3323.35 815.7853498.156 818.925
#Mann= 19 ,-1 , 0
       0    .036       0   2.799    .052       0353.3141    .036       0
405.0871    .046       0932.6091    .036       01132.353    .052       0
1364.631    .082       01380.023    .037       01403.111    .082       0
1444.389    .057       01484.968    .082       0 1500.01    .057       0
1516.101    .082       01535.691    .037       01562.277    .052       0
1638.886    .036       0 1717.25    .052       02206.987    .046       0
2444.862    .052       0
Levee=-1,1359.816,801.4259,-1,1569.68,801.2582,,
#XS Ineff= 2 ,-1
 1584.96 1630.68801.3192 1722.12 2194.56801.0144
Permanent Ineff=
       T       T
Bank Sta=1359.816,1569.68
XS Rating Curve= 0 ,0
Exp/Cntr=0.3,0.1

Type RM Length L Ch R = 1 ,48.24558,129.1081,89.8029,88.976
XS GIS Cut Line= 5
       558152.72       4832387.6       558993.54      4833491.52
       559094.69      4833538.69       559144.49      4833620.98
       560320.77      4835147.18
#Sta/Elev= 30
       0819.7761258.1878817.8719315.2769802.0419371.2559 802.371469.7809810.2068
475.3569802.4719884.1099 801.0481378.296800.66111412.394801.80451412.462 801.806
  1426.2798.05111439.134797.99991449.799 799.8871514.258800.21011522.368798.4861
1553.004799.2731 1568.15801.95721569.687 801.9841570.264801.9941 1684.74801.3259
1783.366   801.11834.792 801.0262213.445802.29212455.078  801.34 2885.98803.4041
2898.299810.61412904.885 803.4363300.042 805.1033415.369821.00413522.351 820.268
#Mann= 18 ,-1 , 0
       0    .052       0258.1878    .036       0371.2559    .046       0
884.1099    .036       01378.296    .052       01412.462    .082       0
  1426.2    .037       01449.799    .082       01514.258    .082       0
1522.368    .037       01553.004    .082       0 1568.15    .052       0
1570.264    .036       0 1684.74    .052       01783.366    .036       0
1834.792    .052       02213.445    .046       02455.078    .052       0
Levee=-1,1412.394,801.8251,-1,1569.687,801.9867,,
#XS Ineff= 2 ,-1
 1661.16 2202.18801.0144  937.261344.778801.0144
Permanent Ineff=
       T       T
Bank Sta=1412.394,1569.687
XS Rating Curve= 0 ,0
Exp/Cntr=0.3,0.1

Type RM Length L Ch R = 3 ,48.19741,,,
BEGIN DESCRIPTION:
Greenbelt Pathway Walk Bridge (RM 48.20)
END DESCRIPTION:
Bridge Culvert--1,0,-1,-1, 0
Deck Dist Width WeirC Skew NumUp NumDn MinLoCord MaxHiCord MaxSubmerge Is_Ogee
76.2,4.572,1.44,0, 5, 5, , , 0.95, 0, 0,0,,
  1409.7  1409.7 1455.42 1455.42 1463.04
801.0144801.0144801.0144801.0144 798.576
 798.576800.4048800.4048 798.576 798.576
1481.3281481.3281517.9041517.9041520.952
801.0144801.0144801.0144801.0144801.0144
 798.576800.4048800.4048 798.576 798.576
BR Coef=-1 , 0 , 0 ,1.25, 0 ,,,0.8,-1,2,0,
WSPro=,,,, 1 ,,,, 0 ,,,, 0 ,,,,-1 ,-1 ,-1 , 0 , 0 , 0 , 0 , 0
BC Design=,, 0 ,, 0 ,,,,,,
BC Use User HTab Curves=0
BC User HTab FreeFlow(D)= 0

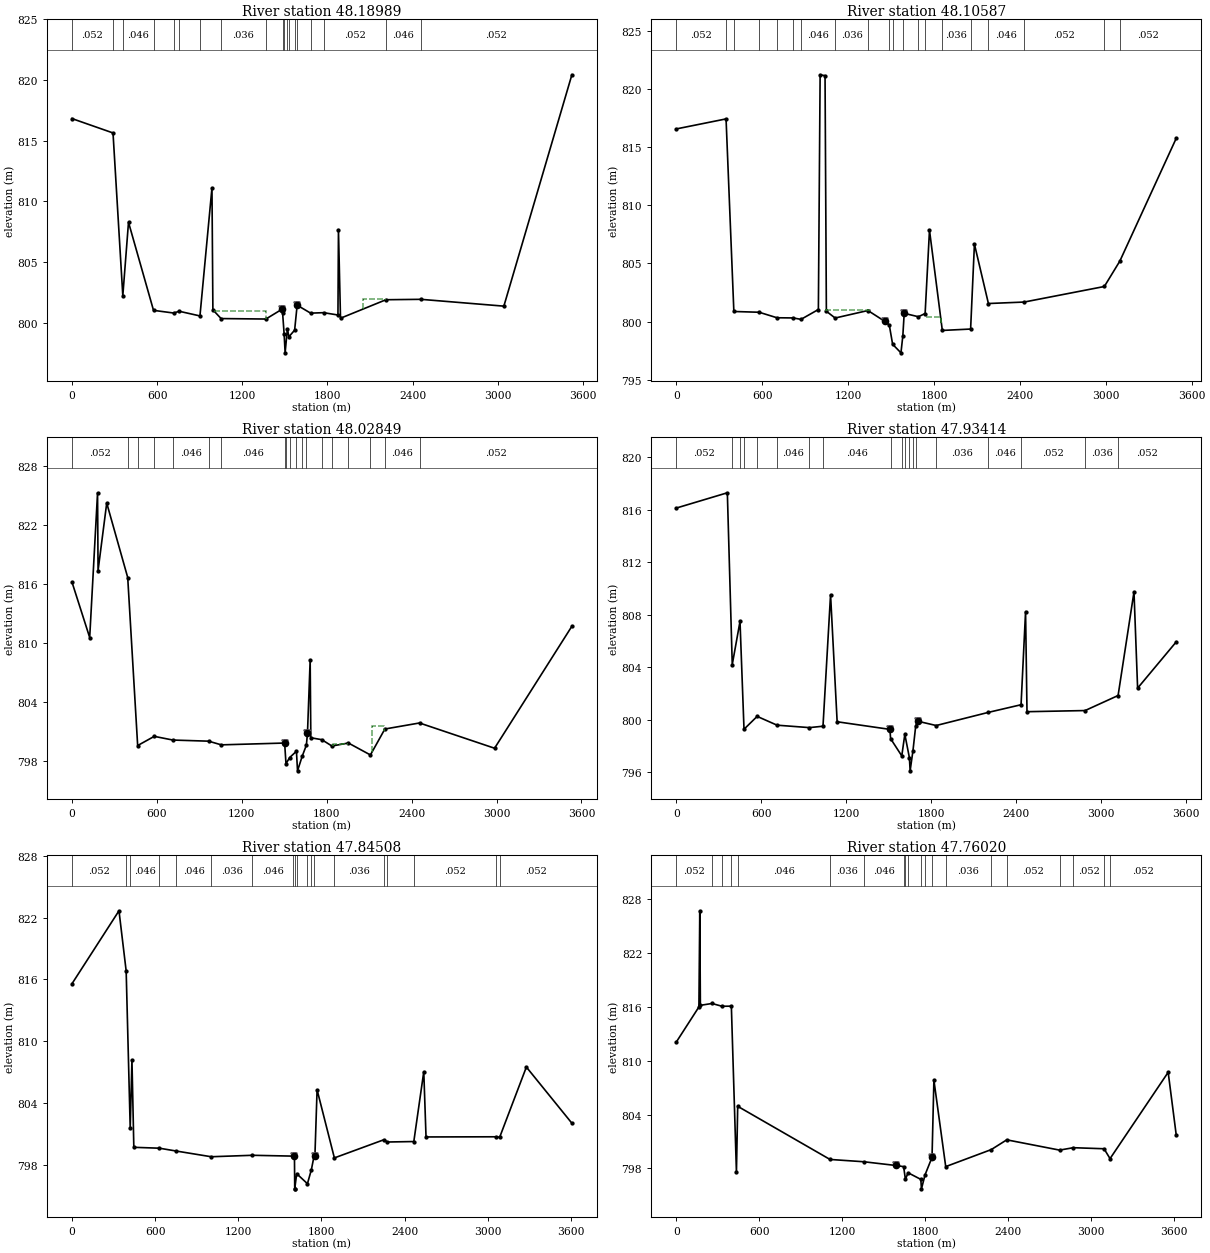
Type RM Length L Ch R = 1 ,48.18989,49.4739,135.4879,123.8771
XS GIS Cut Line= 5
       558052.29      4832502.79       558936.03      4833611.94
       558980.92       4833625.8       559035.95       4833614.4
       560254.12      4835201.42
#Sta/Elev= 30
       0 816.821 289.157815.6381358.1878  802.24 398.259808.2851574.4388801.0348
 716.376800.8141  755.47 800.959901.6332800.5749986.2858 811.117992.7848801.0759
1050.614800.35781366.186800.32011480.862801.13521483.821800.84191494.739799.0841
1501.689797.53691517.632 799.5091528.198  798.861568.701799.40291586.311 801.449
1586.807801.45741681.405800.80411772.625 800.8441873.874800.65111877.424 807.678
1891.899 800.3852212.171 801.9092458.007801.94193042.784 801.3813522.004820.4271
#Mann= 19 ,-1 , 0
       0    .052       0 289.157    .036       0358.1878    .046       0
574.4388    .036       0 716.376    .046       0  755.47    .036       0
901.6332    .046       01050.614    .036       01366.186    .046       0
1483.821    .082       01494.739    .037       01517.632    .082       0
1528.198    .037       01568.701    .082       01586.311    .052       0
1681.405    .036       01772.625    .052       02212.171    .046       0
2458.007    .052       0
Levee=-1,1480.862,801.1546,-1,1586.807,801.435,,
#XS Ineff= 3 ,-1
  1600.2 1996.44800.7096 2049.78 2202.18801.9288 1005.84 1363.98801.0144
Permanent Ineff=
       T       T       T
Bank Sta=1480.862,1586.807
XS Rating Curve= 0 ,0
Exp/Cntr=0.3,0.1

Type RM Length L Ch R = 1 ,48.10587,174.9079,124.783,101.7099
BEGIN DESCRIPTION:
FEMA XS "AT"
PROJECT XS "AT"
END DESCRIPTION:
XS GIS Cut Line= 4
       558017.74      4832520.86       558343.52      4832933.38
       559318.73      4834168.28       560182.44      4835261.96
#Sta/Elev= 30
       0816.5549 347.184817.4151401.6709800.8629578.4071800.7971703.0989800.3237
815.2181800.3091870.7529800.1868992.1859 801.0331004.398821.20741038.745 821.127
1048.049800.88311109.311800.30081338.438800.94611456.209800.01521487.581 799.705
1510.982798.04291569.141 797.3091582.235 798.7641591.778 800.7051690.861800.4124
1738.014800.68791768.488807.84891858.166799.23412055.858799.35382082.533806.6532
2180.201801.54782429.936 801.674 2990.18803.01123098.457805.19293492.792 815.757
#Mann= 20 ,-1 , 0
       0    .052       0 347.184    .036       0401.6709    .046       0
578.4071    .036       0703.0989    .046       0815.2181    .036       0
870.7529    .046       01109.311    .036       01338.438    .046       0
1487.581    .082       01510.982    .037       01582.235    .052       0
1690.861    .036       01738.014    .052       01858.166    .036       0
2055.858    .052       02180.201    .046       02429.936    .052       0
 2990.18    .036       03098.457    .052       0
Levee=-1,1456.209,800.0146,-1,1591.778,800.734,,
#XS Ineff= 4 ,-1
 1607.82  1676.4   800.1 1744.98 1851.66800.4048 2072.64  2171.7801.9288
 1036.32 1356.36801.0144
Permanent Ineff=
       T       T       T       T
Bank Sta=1456.209,1591.778
XS Rating Curve= 0 ,0
Exp/Cntr=0.3,0.1

Type RM Length L Ch R = 1 ,48.02849,149.4081,152.137,163.8449
XS GIS Cut Line= 5
       557975.26      4832544.35       558806.92      4833785.49
       558871.21      4833826.02       558983.03      4833868.65
       560121.23      4835317.38
#Sta/Elev= 30
       0816.2361125.1759 810.601180.7199 825.313 184.315 817.405 245.506824.2679
393.8251   816.7464.1129799.6191581.3771 800.553713.1229800.1771 965.312800.0641
 1055.38799.68911502.539799.87411502.618799.85661512.075797.77281537.859798.3959
1585.895799.03991593.614 797.0481626.867798.54191656.183799.65591663.967800.8799
1682.879808.31321687.626800.40911764.971800.21621836.677799.56991952.876799.8769
2108.639798.66192210.717   801.32455.489 801.9132985.761799.34593532.062811.7449
#Mann= 19 ,-1 , 0
       0    .052       0393.8251    .036       0464.1129    .046       0
581.3771    .036       0713.1229    .046       0 965.312    .036       0
 1055.38    .046       01502.539    .082       01512.075    .037       0
1537.859    .082       01585.895    .037       01626.867    .082       0
1656.183    .052       01764.971    .036       01836.677    .052       0
1952.876    .036       02108.639    .052       02210.717    .046       0
2455.489    .052       0
Levee=-1,1502.618,799.8745,-1,1663.967,800.8925,,
#XS Ineff= 3 ,-1
 1668.781755.648   800.1 1844.04 1950.72799.7952 2118.36 2202.18 801.624
Permanent Ineff=
       T       T       T
Bank Sta=1502.618,1663.967
XS Rating Curve= 0 ,0
Exp/Cntr=0.3,0.1

Type RM Length L Ch R = 1 ,47.93414,139.531,143.6151,127.1879
XS GIS Cut Line= 5
        557926.4      4832591.65       558698.44      4833886.12
       558808.85      4833942.03       558897.61      4834034.98
       559986.54       4835432.6
#Sta/Elev= 30
       0816.1248360.0831817.2861 394.794804.2151449.5291807.4969477.7789799.2902
570.6511800.2689 711.195799.5989 939.667799.41391035.717  799.521089.162 809.533
1135.681799.85891508.236799.28011513.496798.57111592.242 797.2621613.783798.9052
1646.271797.1129  1651.2796.12421671.343797.66581690.765799.55411703.594799.9049
1835.193 799.573 2202.09800.5691  2434.8801.15462466.695808.24612476.767800.6248
2887.153 800.7123120.216 801.8563232.559809.7421 3258.08802.41713531.254 805.943
#Mann= 19 ,-1 , 0
       0    .052       0 394.794    .046       0449.5291    .036       0
477.7789    .046       0570.6511    .036       0 711.195    .046       0
 939.667    .036       01035.717    .046       01513.496    .082       0
1592.242    .037       01613.783    .082       01646.271    .037       0
1671.343    .082       01690.765    .052       01835.193    .036       0
 2202.09    .046       0  2434.8    .052       02887.153    .036       0
3120.216    .052       0
Levee=-1,1508.236,799.2831,-1,1703.594,799.9171,,
#XS Ineff= 1 ,-1
 1706.88 1798.32799.1856
Permanent Ineff=
       T
Bank Sta=1508.236,1703.594
XS Rating Curve= 0 ,0
Exp/Cntr=0.3,0.1

Type RM Length L Ch R = 1 ,47.84508,139.1659,136.8829,135.643
XS GIS Cut Line= 4
       557786.13      4832661.26        558544.9      4833957.47
       558824.44      4834114.95       559916.81      4835524.97
#Sta/Elev= 30
       0815.5859339.1699822.6522 390.941 816.824 420.154 801.624432.7099808.2022
446.2351799.7471630.4111 799.662751.5881 799.3881004.402798.83391300.854 798.975
1593.339798.89511605.016798.90751606.954795.72611607.043795.72711621.108797.1931
1698.648796.22381726.778797.56321746.253 798.8821752.563798.89541768.263805.3178
1893.036798.72112250.077800.48012274.601 800.2612466.104 800.3062538.001807.0681
2554.261800.75023062.252800.76693085.335 800.716 3278.17807.5192 3606.47802.0818
#Mann= 19 ,-1 , 0
       0    .052       0 390.941    .036       0 420.154    .046       0
630.4111    .036       0751.5881    .046       01004.402    .036       0
1300.854    .046       01593.339    .082       01607.043    .037       0
1621.108    .082       01698.648    .037       01726.778    .082       0
1746.253    .052       01893.036    .036       02250.077    .046       0
2274.601    .036       02466.104    .052       03062.252    .036       0
3085.335    .052       0
Levee=-1,1605.016,798.9204,-1,1752.563,798.8961,,
#XS Ineff= 1 ,-1
 1767.84 1874.52799.1856
Permanent Ineff=
       T
Bank Sta=1605.016,1752.563
XS Rating Curve= 0 ,0
Exp/Cntr=0.3,0.1

Type RM Length L Ch R = 1 ,47.76020,59.0821,64.19,54.0871
BEGIN DESCRIPTION:
FEMA XS "AS"
PROJECT XS "AS"
END DESCRIPTION:
XS GIS Cut Line= 6
       557671.89      4832718.83       558125.44      4833501.58
       558485.32      4834082.75       558771.83      4834238.43
       558958.56      4834476.02       559817.39      4835580.38
#Sta/Elev= 30
       0812.0881163.0369815.9871 169.331826.7051173.6759816.1691257.7849816.3751
329.7329816.0651397.7039816.0761434.4031797.5768443.6208804.9171 1111.04798.9951
1356.532 798.7361584.905798.32641643.602798.19411656.618796.7759 1675.78797.5101
1767.975 796.774 1772.53795.71911799.068797.30291848.981799.22541849.324799.4401
1862.549 807.8261948.026798.19592277.398 800.0932389.478801.17992771.274800.0351
  2870.7 800.3033093.052 800.1863136.438799.08593556.876808.70783615.492801.6788
#Mann= 20 ,-1 , 0
       0    .052       0257.7849    .036       0329.7329    .052       0
397.7039    .036       0443.6208    .046       0 1111.04    .036       0
1356.532    .046       01643.602    .082       01656.618    .037       0
 1675.78    .082       01767.975    .037       01799.068    .082       0
1849.324    .052       01948.026    .036       02277.398    .046       0
2389.478    .052       02771.274    .036       0  2870.7    .052       0
3093.052    .036       03136.438    .052       0
Levee=-1,1584.905,798.384,-1,1848.981,799.1765,,
#XS Ineff= 1 ,-1
 1859.28 1935.48798.8808
Permanent Ineff=
       T
Bank Sta=1584.905,1848.981
XS Rating Curve= 0 ,0
Exp/Cntr=0.3,0.1

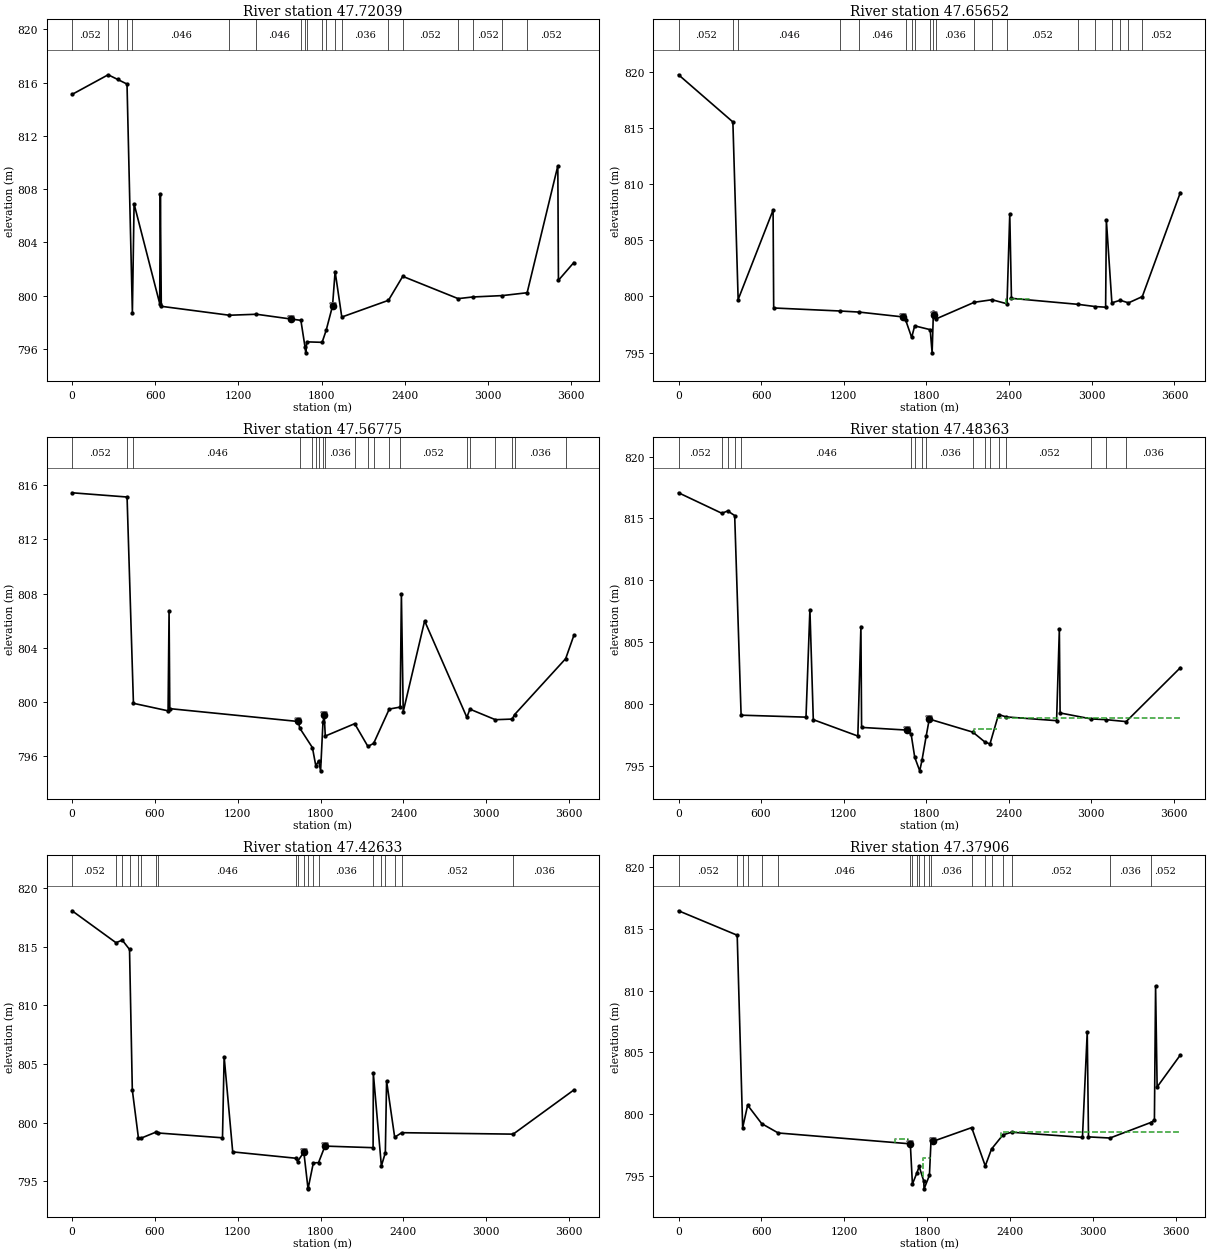
Type RM Length L Ch R = 1 ,47.72039,37.0951,102.9959,130.1429
XS GIS Cut Line= 5
       557636.17      4832742.53         558457.      4834124.02
       558563.92      4834208.58       558706.49      4834258.89
       559781.21      4835607.87
#Sta/Elev= 30
       0815.1208260.2199 816.597329.7092816.2431396.3019 815.899 435.027798.7101
 447.269 806.897 631.933  799.41636.7891807.6082 643.598   799.21134.256798.5291
1329.692798.60311579.583798.24391650.353 798.1451680.393796.12421685.258795.7039
 1693.06796.52891803.445796.49391832.399797.38511878.482799.22171897.182801.8151
1945.318798.39312281.903799.6501 2385.05801.45092784.609799.7769 2888.48   799.9
3104.184800.00613282.248800.22013503.539809.75213507.913 801.1543619.195802.4908
#Mann= 20 ,-1 , 0
       0    .052       0260.2199    .036       0329.7092    .052       0
396.3019    .036       0 435.027    .046       01134.256    .036       0
1329.692    .046       01650.353    .082       01680.393    .037       0
 1693.06    .082       01803.445    .037       01832.399    .082       0
1897.182    .052       01945.318    .036       02281.903    .046       0
 2385.05    .052       02784.609    .036       0 2888.48    .052       0
3104.184    .036       03282.248    .052       0
Levee=-1,1579.583,798.2498,-1,1878.482,799.1887,,
Bank Sta=1579.583,1878.482
XS Rating Curve= 0 ,0
Exp/Cntr=0.3,0.1

Type RM Length L Ch R = 1 ,47.65652,84.6341,143.1441,141.3961
XS GIS Cut Line= 5
       557618.83      4832755.44        558441.9      4834155.47
       558556.16      4834261.35       558609.63      4834372.46
       559584.69      4835813.52
#Sta/Elev= 30
       0819.7279 394.545 815.529432.7971 799.722 686.423807.6831690.7941798.9689
1171.612798.70091311.142798.60411632.241798.1693 1648.49797.90911692.571796.3431
 1714.43797.37821827.001797.03981841.123 794.9761850.316 798.5941856.119798.3816
1868.896 797.9922147.591799.47792275.827799.70312384.755799.34292404.776 807.339
2417.038799.82812899.521799.29413024.479799.09693100.746 799.0393106.144806.7761
3146.158799.42793206.267799.65593266.743799.42493366.927799.98113643.073809.2401
#Mann= 20 ,-1 , 0
       0    .052       0 394.545    .036       0432.7971    .046       0
1171.612    .036       01311.142    .046       0 1648.49    .082       0
1692.571    .037       0 1714.43    .082       01827.001    .037       0
1850.316    .082       01868.896    .036       02147.591    .052       0
2275.827    .046       02384.755    .052       02899.521    .036       0
3024.479    .052       03146.158    .036       03206.267    .052       0
3266.743    .036       03366.927    .052       0
Levee=-1,1632.241,798.2042,-1,1856.119,798.387,,
#XS Ineff= 1 ,-1
 2377.44 2545.08799.7952
Permanent Ineff=
       T
Bank Sta=1632.241,1856.119
XS Rating Curve= 0 ,0
Exp/Cntr=0.3,0.1

Type RM Length L Ch R = 1 ,47.56775,126.6331,135.6601,133.8959
XS GIS Cut Line= 5
       557561.73       4832783.3       558382.33      4834190.22
       558478.77      4834429.22       558714.26      4834773.42
       559463.56      4835873.18
#Sta/Elev= 30
       0815.4312 398.316 815.119444.4718 799.911695.3579799.3578 702.517 806.701
 707.827 799.5191636.432798.57321650.323 798.0631740.817796.6439 1765.53795.2908
1785.518795.67891800.026 794.9341817.137798.50981826.328799.02671833.854 797.497
2046.823798.40992142.768796.73112184.198  796.962297.224799.48712376.088799.6334
2385.183 807.9872398.421799.2932 2553.46805.98512859.083 798.8822881.615  799.48
3065.873 798.7043187.257798.74913205.066799.08113575.033803.20413634.274804.9171
#Mann= 20 ,-1 , 0
       0    .052       0 398.316    .036       0444.4718    .046       0
1650.323    .082       01740.817    .057       0 1765.53    .082       0
1785.518    .037       01817.137    .082       01833.854    .036       0
2046.823    .052       02142.768    .026       02184.198    .052       0
2297.224    .046       02376.088    .052       02859.083    .036       0
2881.615    .052       03065.873    .036       03187.257    .052       0
3205.066    .036       03575.033    .052       0
Levee=-1,1636.432,798.5668,-1,1826.328,799.0607,,
#XS Ineff= 3 ,-1
 2049.78    2286798.2712 2377.44 2484.12799.4904 2689.86 2758.44799.4904
Permanent Ineff=
       T       T       T
Bank Sta=1636.432,1826.328
XS Rating Curve= 0 ,0
Exp/Cntr=0.3,0.1

Type RM Length L Ch R = 1 ,47.48363,95.987,92.4001,93.3889
BEGIN DESCRIPTION:
FEMA XS "AR"
PROJECT XS "AR"
END DESCRIPTION:
XS GIS Cut Line= 6
       557475.12      4832827.78       558150.69      4834015.85
       558274.53      4834233.64       558345.19      4834458.81
       558583.17      4834830.24       559349.58      4835947.19
#Sta/Elev= 30
       0817.0731315.2711815.4141 357.599815.6061408.3202815.2291455.0271 799.095
  926.97798.9359955.3221807.6301 979.972798.73211303.953797.40891326.206806.2631
1331.191798.10691663.851797.88781691.665797.54211717.572795.69381753.911794.5959
1770.118795.43681801.134797.41991823.396798.78052140.124 797.7252225.875 796.945
2264.553796.76492326.951 799.1492382.781798.95482749.183 798.6512769.217806.0311
2774.694799.27493000.552798.79213111.115798.73113254.886 798.5763648.974 802.931
#Mann= 17 ,-1 , 0
       0    .052       0315.2711    .036       0 357.599    .052       0
408.3202    .036       0455.0271    .046       01691.665    .082       0
1717.572    .037       01770.118    .082       01801.134    .036       0
2140.124    .052       02225.875    .026       02264.553    .052       0
2326.951    .046       02382.781    .052       03000.552    .036       0
3111.115    .052       03254.886    .036       0
Levee=-1,1663.851,797.9177,-1,1823.396,798.8138,,
#XS Ineff= 2 ,-1
 2148.84 2316.48797.9664 2316.483648.974798.8808
Permanent Ineff=
       T       T
Bank Sta=1663.851,1823.396
XS Rating Curve= 0 ,0
Exp/Cntr=0.3,0.1

Type RM Length L Ch R = 1 ,47.42633,79.9091,76.2189,86.8671
XS GIS Cut Line= 6
       557447.07      4832851.26       558075.25      4834050.83
       558186.25      4834276.38       558274.51      4834510.28
       558553.26      4834909.02        559255.8      4835994.91
#Sta/Elev= 30
       0  818.05318.4559  815.33363.5341815.5509416.2458814.7582 436.512802.7828
480.5919798.7159 501.677 798.694610.0099799.2118619.0979799.13021089.797 798.715
 1101.67805.62511163.769797.51591620.997796.97611633.357796.69691678.948797.4872
1679.162797.49091708.609794.46311709.587794.3691 1747.87796.57711785.678796.6031
1832.128798.0096 2180.83 797.8742182.524804.20692240.822796.31712269.541 797.447
2278.528803.55622337.158798.76312388.417799.15093195.825 799.0283635.283802.7889
#Mann= 20 ,-1 , 0
       0    .052       0318.4559    .036       0363.5341    .052       0
416.2458    .036       0480.5919    .046       0 501.677    .052       0
610.0099    .036       0619.0979    .046       01620.997    .082       0
1633.357    .046       01679.162    .082       01708.609    .037       0
 1747.87    .082       01785.678    .036       0 2180.83    .052       0
2240.822    .026       02269.541    .052       02337.158    .046       0
2388.417    .052       03195.825    .036       0
Levee=-1,1678.948,797.5031,-1,1832.128,798.0273,,
#XS Ineff= 2 ,-1
 2179.32  2324.1797.6616  2324.13635.283798.8808
Permanent Ineff=
       T       T
Bank Sta=1678.948,1832.128
XS Rating Curve= 0 ,0
Exp/Cntr=0.3,0.1

Type RM Length L Ch R = 1 ,47.37906,18.6599,26.0781,44.8339
XS GIS Cut Line= 5
       557421.54      4832876.79         558106.      4834309.77
       558214.07      4834535.21       558483.13      4834966.71
       559157.73      4836060.31
#Sta/Elev= 30
       0 816.455 424.523814.4759464.1071798.8921500.0591800.7191 601.741799.2249
721.5811798.46811677.028797.58861677.394797.59911692.646 794.3321725.693 795.254
1741.308795.75511774.355794.58891777.093793.94611815.754 795.0411827.375797.8929
1844.058797.80072121.528798.90222219.941 795.7992264.972 797.1662347.771798.3142
2410.232  798.532923.218798.11212957.832806.65012966.892 798.1523122.371 798.059
3416.159799.30993443.978 799.4983452.469810.38093463.637802.18913631.509804.7799
#Mann= 20 ,-1 , 0
       0    .052       0 424.523    .036       0464.1071    .057       0
500.0591    .052       0 601.741    .036       0721.5811    .046       0
1677.394    .082       01692.646    .037       01725.693    .036       0
1741.308    .082       01774.355    .026       01815.754    .082       0
1827.375    .036       02121.528    .052       02219.941    .026       0
2264.972    .052       02347.771    .046       02410.232    .052       0
3122.371    .036       03416.159    .052       0
Levee=-1,1677.028,797.5823,-1,1844.058,797.7988,,
#XS Ineff= 4 ,-1
 1569.72 1661.16797.96641766.0751825.487796.4424  2133.6 2331.72 797.052
 2331.723631.509 798.576
Permanent Ineff=
       T       T       T       T
Bank Sta=1677.028,1844.058
XS Rating Curve= 0 ,0
Exp/Cntr=0.3,0.1

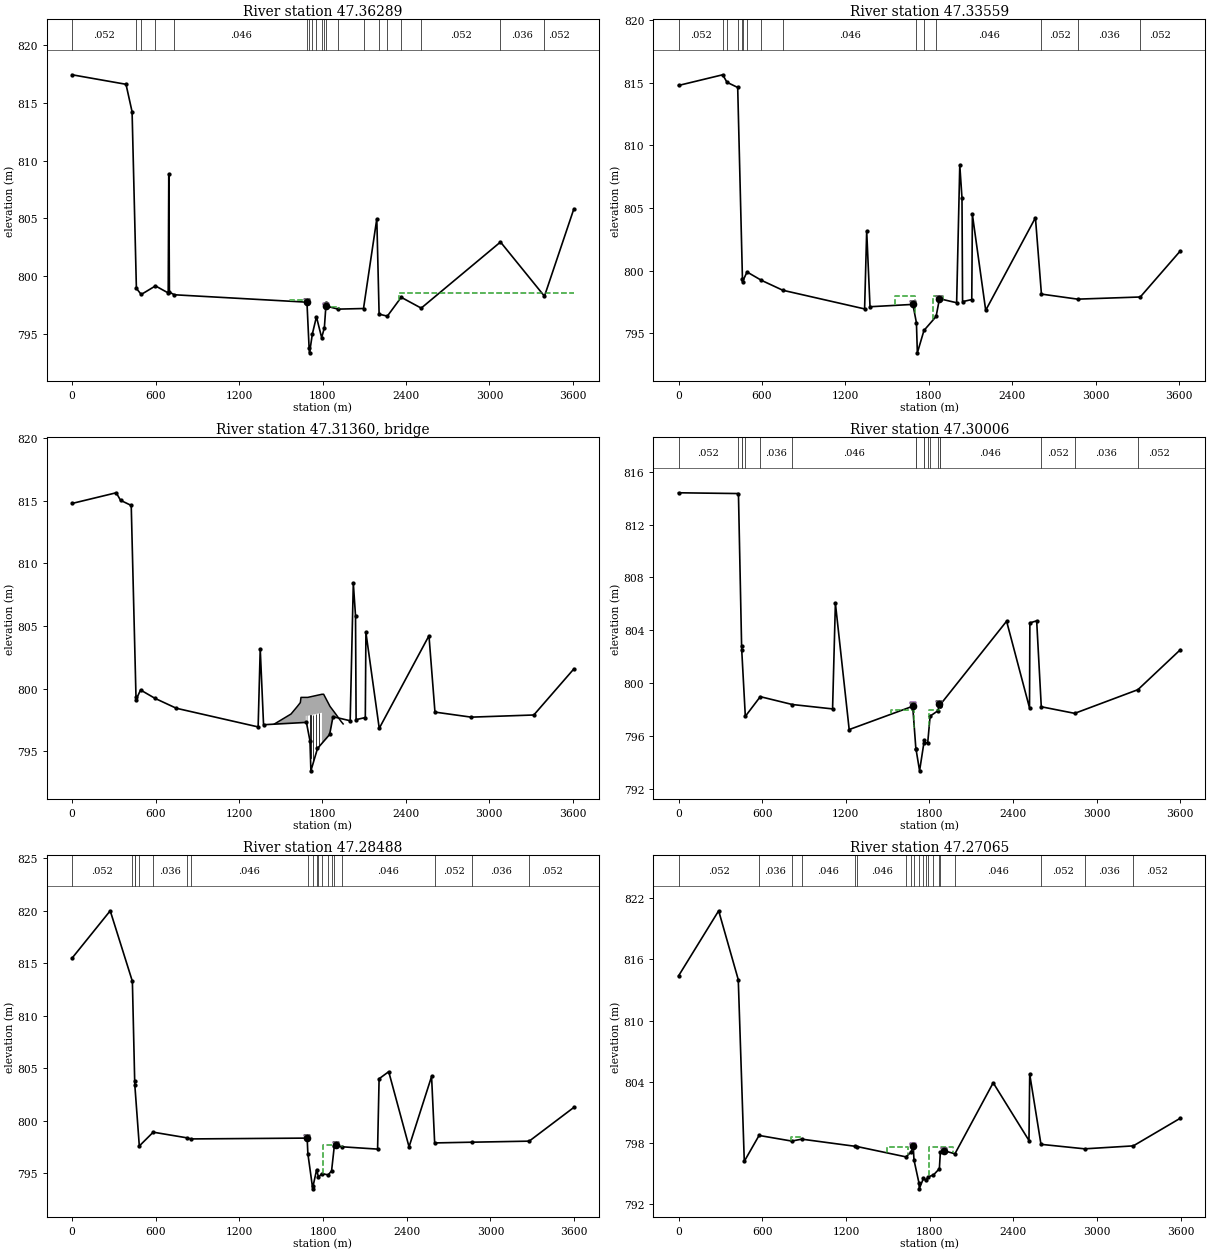
Type RM Length L Ch R = 1 ,47.36289,32.5679,44.025,58.3399
XS GIS Cut Line= 4
       557415.53       4832882.8        558108.7      4834332.58
       558170.55      4834549.58       559063.42      4836082.31
#Sta/Elev= 30
       0817.4221387.6279816.5992431.3499 814.222462.3469 798.943496.9691 798.415
 599.392799.1569 691.048798.5488 695.157808.8599 699.605798.6208734.6342 798.391
1687.227797.7506 1688.54797.64081703.687 793.7551706.665793.3669 1727.49795.0281
1756.341796.48691793.849794.67491813.323795.53891825.955797.70791828.392797.4105
1911.419 797.1492094.626 797.2012190.189 804.9642206.787 796.7142265.933796.5408
2365.475798.17222509.368797.23493079.187802.95423395.113798.26513606.452805.8211
#Mann= 20 ,-1 , 0
       0    .052       0462.3469    .057       0496.9691    .052       0
 599.392    .036       0734.6342    .046       0 1688.54    .082       0
1703.687    .037       0 1727.49    .036       01756.341    .082       0
1793.849    .026       01813.323    .082       01825.955    .046       0
1911.419    .036       02094.626    .052       02206.787    .026       0
2265.933    .052       02365.475    .046       02509.368    .052       0
3079.187    .036       03395.113    .052       0
Levee=-1,1687.227,797.7805,-1,1828.392,797.3751,,
#XS Ineff= 4 ,-1
 1569.72 1668.78797.9664 1859.28 1920.24797.3568 2103.12 2346.96797.3568
 2346.963606.452 798.576
Permanent Ineff=
       T       T       T       T
Bank Sta=1687.227,1828.392
XS Rating Curve= 0 ,0
Exp/Cntr=0.5,0.3

Type RM Length L Ch R = 1 ,47.33559,51.9169,57.285,48.095
BEGIN DESCRIPTION:
Glenwood Bridge Upstream
END DESCRIPTION:
XS GIS Cut Line= 4
       557407.56      4832890.77       558100.36      4834333.85
       558114.51      4834606.27       558886.69       4836159.5
#Sta/Elev= 30
       0814.7932 317.516 815.646348.5461815.0449 425.399814.6329459.6759 799.303
460.0371 799.113492.5099 799.887 596.425 799.217749.7699 798.4261337.922796.9349
1352.951 803.1661376.861 797.1091685.056797.29611710.617 795.8241717.268793.4249
1764.739795.21311852.056 796.3291876.193797.75021999.691797.42812022.285808.4272
2038.178805.80892042.329797.51592108.499797.68382112.939804.48122208.698796.8219
 2566.28804.22212609.403798.1191 2869.55797.71583320.205797.88813608.134801.5701
#Mann= 15 ,-1 , 0
       0    .052       0 317.516    .036       0348.5461    .052       0
 425.399    .036       0459.6759    .052       0460.0371    .057       0
492.5099    .052       0 596.425    .036       0749.7699    .046       0
1710.617    .037       01764.739    .036       01852.056    .046       0
2609.403    .052       0 2869.55    .036       03320.205    .052       0
Levee=-1,1685.056,797.2928,-1,1876.193,797.7653,,
#XS Ineff= 4 ,-1
 1554.48 1699.26797.9664  1828.8    1905797.9664    1905 2392.68797.3568
 2392.683608.134 798.576
Permanent Ineff=
       T       T       T       T
Bank Sta=1685.056,1876.193
XS Rating Curve= 0 ,0
Exp/Cntr=0.5,0.3

Type RM Length L Ch R = 3 ,47.31360,,,
BEGIN DESCRIPTION:
Glenwood Street Bridge
END DESCRIPTION:
Bridge Culvert--1,0,-1,-1, 0
Deck Dist Width WeirC Skew NumUp NumDn MinLoCord MaxHiCord MaxSubmerge Is_Ogee
9.144,26.2128,1.44,0, 18, 18, , , 0.95, 0, 0,0,,
 1455.421574.2921620.0121641.348 1645.921680.9721680.9721685.5441685.5441694.688
1694.6881796.7961796.7961808.9881854.7081895.856 1935.481949.196
797.1739797.9664 798.576798.8808799.2953799.2953799.2953799.2953799.2953799.2953
799.2953799.5452799.5452799.5452 798.576797.9664797.3568797.1739
793.6992793.6992793.6992793.6992793.6992793.6992797.8262797.8262793.6992793.6992
797.8262798.0701793.6992793.6992793.6992793.6992793.6992793.6992
 1455.421574.2921620.0121641.348 1645.921680.9721680.9721685.5441685.5441694.688
1694.6881796.7961796.7961808.9881854.7081895.856 1935.481949.196
797.1739797.9664 798.576798.8808799.2953799.2953799.2953799.2953799.2953799.2953
799.2953799.5452799.5452799.5452 798.576797.9664797.3568797.1739
793.6992793.6992793.6992793.6992793.6992793.6992797.8262797.8262793.6992793.6992
797.8262798.0701793.6992793.6992793.6992793.6992793.6992793.6992
Pier Skew, UpSta & Num, DnSta & Num=  ,1714.5, 2 ,1714.5, 2 , 0 , 0 , 0 ,,
  1.2192  1.2192
793.6992 798.576
  1.2192  1.2192
793.6992 798.576
Pier Skew, UpSta & Num, DnSta & Num=  ,1735.074, 2 ,1735.074, 2 , 0 , 0 , 0 ,,
  1.2192  1.2192
793.6992 798.576
  1.2192  1.2192
793.6992 798.576
Pier Skew, UpSta & Num, DnSta & Num=  ,1755.648, 2 ,1755.648, 2 , 0 , 0 , 0 ,,
  1.2192  1.2192
793.6992 798.576
  1.2192  1.2192
793.6992 798.576
Pier Skew, UpSta & Num, DnSta & Num=  ,1776.222, 2 ,1776.222, 2 , 0 , 0 , 0 ,,
  1.2192  1.2192
793.6992 798.576
  1.2192  1.2192
793.6992 798.576
BR Coef=-1 , 0 , 0 ,1.25, 0 ,,,0.8,-1,2,0,
WSPro=,,,, 1 ,,,, 0 ,,,, 0 ,,,,-1 ,-1 ,-1 , 0 , 0 , 0 , 0 , 0
BC Design=,, 0 ,, 0 ,,,,,,
BC Use User HTab Curves=0
BC User HTab FreeFlow(D)= 0

Type RM Length L Ch R = 1 ,47.30006,23.8079,24.47,32.5191
BEGIN DESCRIPTION:
Glenwood Bridge Downstream
END DESCRIPTION:
XS GIS Cut Line= 4
       557377.09      4832919.12       558058.36       4834335.7
       558072.51       4834611.4       558867.29      4836173.08
#Sta/Elev= 30
       0814.4079 429.868814.3491 452.549802.7999 453.269802.5342 479.191 797.479
586.4781798.9698 816.533798.37521105.191798.04291125.429806.04391224.358 796.479
1680.161798.2444 1702.91795.0129 1703.27795.03521729.406793.35381763.034795.6512
1763.754795.44821787.875 795.4931805.156 797.497 1861.68797.90611870.637798.4307
1872.481 798.2991872.841 798.2992353.779804.68422518.181 798.121  2520.8804.5549
2569.525804.71312602.608 798.2052842.384797.70613296.013799.49993600.231 802.524
#Mann= 19 ,-1 , 0
       0    .052       0 429.868    .036       0 452.549    .052       0
 453.269    .057       0 479.191    .052       0586.4781    .036       0
 816.533    .046       0 1702.91    .082       0 1703.27    .037       0
1763.034    .082       01763.754    .037       01787.875    .082       0
1805.156    .046       0 1861.68    .082       01872.481    .057       0
1872.841    .046       02602.608    .052       02842.384    .036       0
3296.013    .052       0
Levee=-1,1680.161,798.3657,-1,1870.637,798.4266,,
#XS Ineff= 3 ,-1
    1524 1691.64797.9664 1798.32 1874.52797.9664 2392.683600.231798.2712
Permanent Ineff=
       T       T       T
Bank Sta=1680.161,1870.637
XS Rating Curve= 0 ,0
Exp/Cntr=0.5,0.3

Type RM Length L Ch R = 1 ,47.28488,26.3561,22.9581,24.74
XS GIS Cut Line= 4
       557360.21      4832934.23       558038.47      4834337.17
       558051.57      4834612.86       558845.37      4836188.42
#Sta/Elev= 30
       0815.4741273.6141 819.976 432.542 813.267449.0951 803.789 449.815803.4509
482.2021797.6141  581.88798.9272826.5801798.3831850.6901798.28491685.916798.3646
1690.944796.89291725.802793.54011729.088793.85311753.918 795.3641767.233794.6349
1790.263794.99181837.044794.86511861.154795.25791880.226797.56591890.104797.6865
1932.765797.54092191.036797.31682201.816 804.0072270.852804.67812416.609 797.532
 2578.13804.2231 2600.29797.90522870.898797.97583278.252 798.0743598.521 801.282
#Mann= 20 ,-1 , 0
       0    .052       0 432.542    .036       0449.0951    .052       0
 449.815    .057       0482.2021    .052       0  581.88    .036       0
826.5801    .052       0850.6901    .046       01690.944    .082       0
1729.088    .037       01753.918    .082       01767.233    .037       0
1790.263    .082       01837.044    .026       01861.154    .082       0
1880.226    .057       01932.765    .046       0 2600.29    .052       0
2870.898    .036       03278.252    .052       0
Levee=-1,1685.916,798.3961,-1,1890.104,797.7195,,
#XS Ineff= 3 ,-1
 1508.76 1668.78797.6616 1798.32 1935.48797.6616 2392.683598.521798.2712
Permanent Ineff=
       F       F       T
Bank Sta=1685.916,1890.104
XS Rating Curve= 0 ,0
Exp/Cntr=0.5,0.3

Type RM Length L Ch R = 1 ,47.27065,153.2611,130.0609,94.937
BEGIN DESCRIPTION:
FEMA XS "AQ"
PROJECT XS "AQ"
END DESCRIPTION:
XS GIS Cut Line= 6
       557344.01      4832948.74       558018.95      4834337.47
        558030.6      4834606.12       558107.47      4834776.55
       558270.13      4835076.26       558817.75      4836205.81
#Sta/Elev= 30
       0814.3842287.6081820.7819 428.084814.0151471.2449 796.166577.1949798.7089
 811.669 798.155 882.874 798.3451261.917  797.651282.056 797.6111629.811796.6031
1666.852797.07091682.219 797.6291687.351796.30281722.954 794.0511725.227 793.463
 1754.96794.48711772.222794.31491789.844794.64811826.885 794.823 1869.32795.4399
1876.513797.09011900.675797.22031980.803796.90392255.061803.88282511.536798.2109
2516.767804.73512597.557797.83512910.788 797.3943259.263797.68383596.232 800.402
#Mann= 20 ,-1 , 0
       0    .052       0577.1949    .036       0 811.669    .052       0
 882.874    .046       01261.917    .052       01282.056    .046       0
1629.811    .082       01666.852    .046       01687.351    .082       0
1722.954    .037       0 1754.96    .082       01772.222    .037       0
1789.844    .082       01826.885    .026       0 1869.32    .082       0
1876.513    .057       01980.803    .046       02597.557    .052       0
2910.788    .036       03259.263    .052       0
Levee=-1,1682.219,797.619,-1,1900.675,797.2166,,
#XS Ineff= 4 ,-1
  807.72   876.3 798.576 1493.52 1645.92797.6006 1798.32 1965.96797.6006
 2392.683596.232798.2712
Permanent Ineff=
       T       T       T       F
Bank Sta=1682.219,1900.675
XS Rating Curve= 0 ,0
Exp/Cntr=0.3,0.1