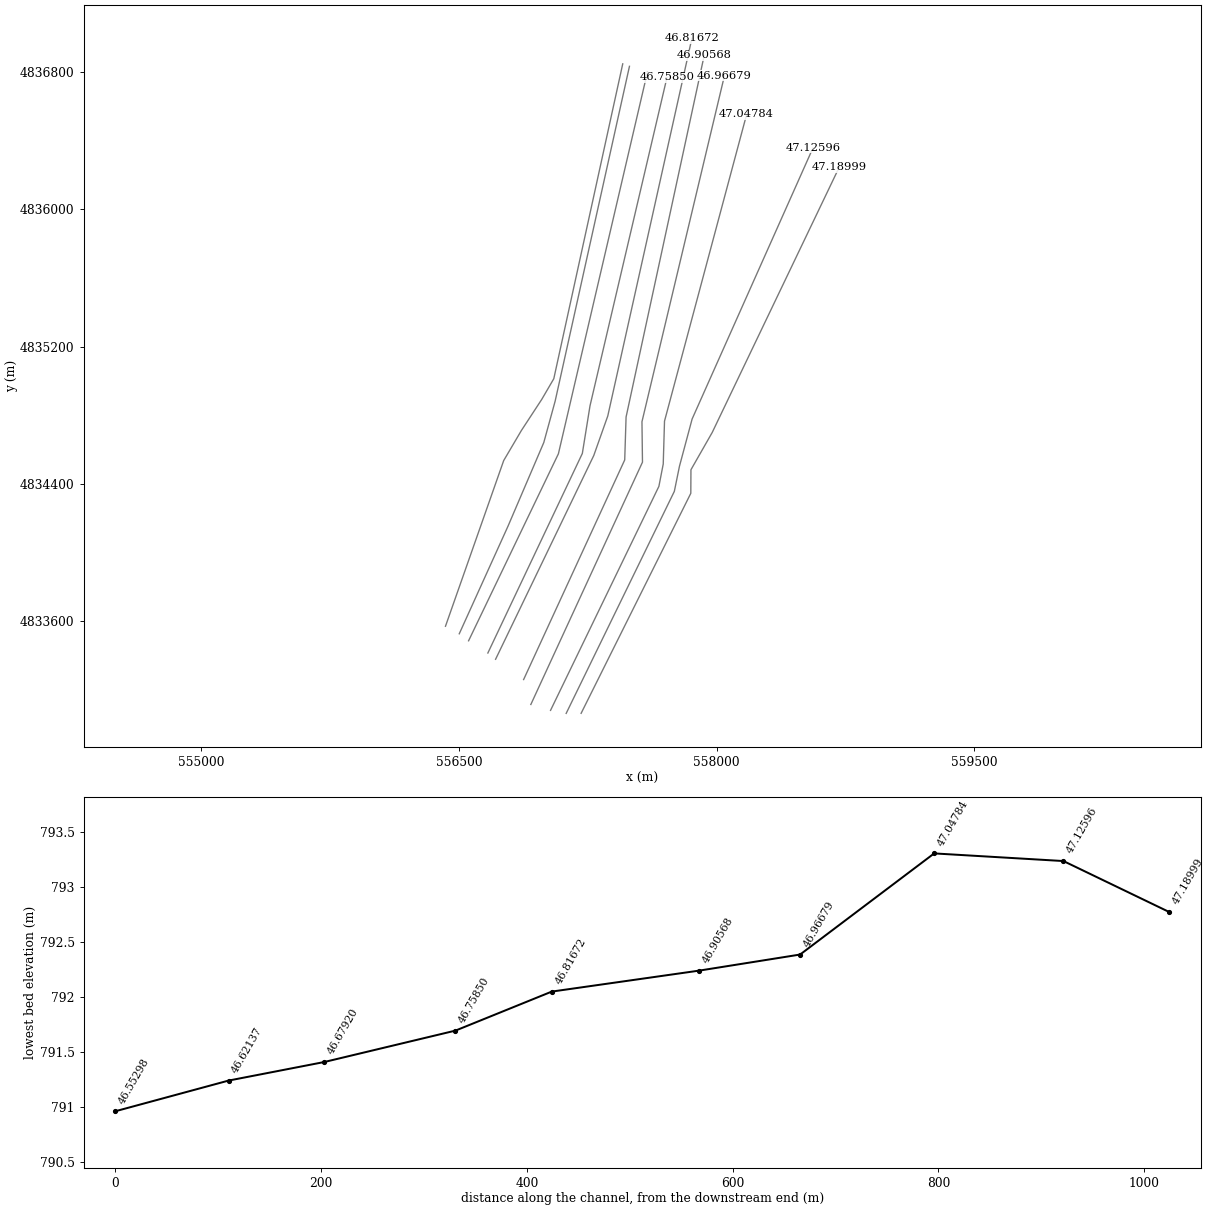
HEC-RAS study Boise2.prj: BoiseRiver_All_reaches

--- Boise2.g01 (geometry) --- (continued)

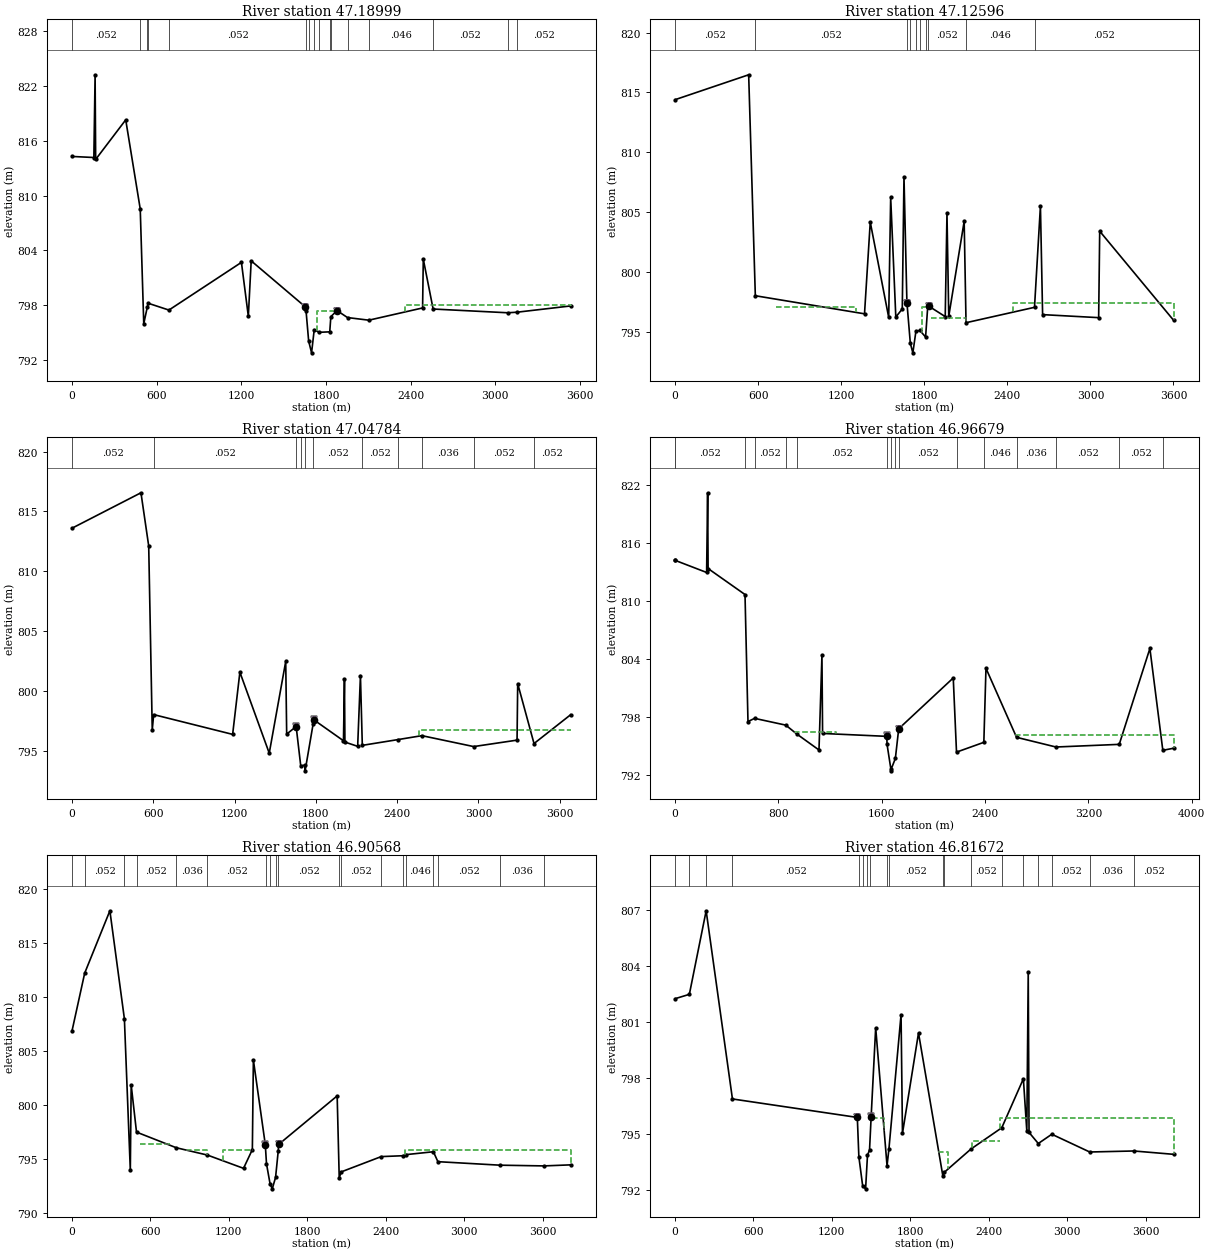
Type RM Length L Ch R = 1 ,47.18999,93.3179,102.9931,122.5171
XS GIS Cut Line= 5
       557211.49      4833064.92       557850.33      4834346.33
       557851.17      4834483.64       557975.08      4834700.77
       558715.42      4836246.98
#Sta/Elev= 30
       0 814.296 155.494 814.179 164.275823.2471168.2749 813.969381.2981818.3082
484.0822808.5411508.9871 795.959534.2571797.7969  540.97 798.202687.2551 797.458
1201.004 802.6851249.952796.78111270.217802.85211650.983 797.8481659.305 797.305
1677.325794.06591698.001792.7698  1716.9 795.3181751.174795.0199 1826.79 795.072
1834.564 796.7351878.293 797.4011952.581796.63682103.812796.34922484.641797.6899
2489.551803.04192559.273 797.5723087.523 797.1623152.891797.22213533.443  797.91
#Mann= 16 ,-1 , 0
       0    .052       0484.0822    .057       0534.2571    .052       0
  540.97    .036       0687.2551    .052       01659.305    .082       0
1677.325    .037       0  1716.9    .082       01751.174    .026       0
 1826.79    .082       01834.564    .057       01952.581    .036       0
2103.812    .046       02559.273    .052       03087.523    .036       0
3152.891    .052       0
Levee=-1,1650.983,797.8414,-1,1878.293,797.4086,,
#XS Ineff= 4 ,-1
 1737.36 1889.76797.3568  678.18 1325.88797.3568 1402.08 1539.24797.3568
  2362.23533.443797.9664
Permanent Ineff=
       F       T       T       T
Bank Sta=1650.983,1878.293
XS Rating Curve= 0 ,0
Exp/Cntr=0.3,0.1

Type RM Length L Ch R = 1 ,47.12596,116.1002,125.6651,138.9181
XS GIS Cut Line= 5
       557124.47      4833064.53       557754.43      4834357.68
       557784.34      4834504.18       557858.03      4834779.18
       558561.95      4836358.31
#Sta/Elev= 30
       0 814.389 532.108 816.473580.2139798.00511368.704796.49391410.153804.1608
1543.406796.19611557.636 806.2171594.749796.22811641.401796.90111653.769807.9489
1675.016797.37861675.454 797.3791699.584794.0299 1717.76793.23281739.922795.0251
1768.735 795.1011809.793794.55381824.919 797.0351833.259797.13241951.591 796.262
1964.241804.87981977.053796.28212088.413804.22492101.881795.75082596.377 797.037
2639.144 805.5022654.893796.4268 3059.68796.17383067.212   803.43601.578795.9432
#Mann= 10 ,-1 , 0
       0    .052       0580.2139    .052       01675.454    .082       0
1699.584    .037       01739.922    .057       01768.735    .082       0
1809.793    .057       01824.919    .052       02101.881    .046       0
2596.377    .052       0
Levee=-1,1675.016,797.3934,-1,1833.259,797.1343,,
#XS Ineff= 5 ,-1
  731.52 1310.64 797.052 1386.84 1554.48 797.052 1783.08 1851.66 797.052
 1851.66 2103.12796.1376  2438.43601.578797.3568
Permanent Ineff=
       T       T       T       T       F
Bank Sta=1675.016,1833.259
XS Rating Curve= 0 ,0
Exp/Cntr=0.3,0.1

Type RM Length L Ch R = 1 ,47.04784,124.8741,130.37,128.6079
XS GIS Cut Line= 5
       557033.39      4833082.05       557664.47      4834386.74
       557689.74      4834516.97       557697.19      4834766.86
       558175.39      4836552.68
#Sta/Elev= 30
       0 813.595509.5909816.5629566.7531812.1131 592.946796.7219603.2681 798.007
1186.238796.35191239.661 801.5561456.352794.78091578.024802.45491585.078796.3768
1653.299796.99261655.949 796.9161689.075793.70011716.681  793.781721.085793.3021
1780.357797.22911790.139797.53142004.265795.81912011.521 800.958 2014.91 795.709
2109.026795.35092129.443801.27412143.274795.43412403.868795.91112583.119796.2449
2965.176 795.3323285.363795.87093290.084800.59813410.542 795.5853680.704797.9951
#Mann= 11 ,-1 , 0
       0    .052       0603.2681    .052       01655.949    .082       0
1689.075    .037       01716.681    .082       01780.357    .052       0
2143.274    .052       02403.868    .046       02583.119    .036       0
2965.176    .052       03410.542    .052       0
Levee=-1,1653.299,797.0398,-1,1790.139,797.5976,,
#XS Ineff= 5 ,-1
  640.08  731.52797.3568  807.72  1295.4 797.052  1371.6 1569.72796.4424
  1981.2  2133.6795.8328 2560.323680.704796.7472
Permanent Ineff=
       T       T       T       T       F
Bank Sta=1653.299,1790.139
XS Rating Curve= 0 ,0
Exp/Cntr=0.3,0.1

Type RM Length L Ch R = 1 ,46.96679,100.4249,98.2879,96.3299
XS GIS Cut Line= 4
       556918.64      4833116.35       557568.84      4834527.68
       557565.84      4834763.18       558046.14      4836777.86
#Sta/Elev= 30
       0 814.154   .3859814.1699244.8321812.9119 252.774821.1589256.4151813.3171
542.0219 810.629565.0279797.4839 616.145797.8162857.4302797.1151944.6779796.1782
1114.703794.54191137.622804.33611142.585796.25311639.754795.95281641.508795.1351
1673.348792.38491675.481792.6251 1705.98 793.6661731.697796.72141731.845 796.739
2154.084801.99712179.284 794.3212390.842 795.3352407.385802.99592644.095795.8529
2949.079794.85113438.982795.12413676.309805.04513776.396794.50823860.557 794.726
#Mann= 16 ,-1 , 0
       0    .036       0   .3859    .052       0542.0219    .046       0
 616.145    .052       0857.4302    .036       0944.6779    .052       0
1641.508    .082       01675.481    .037       0 1705.98    .082       0
1731.845    .052       02179.284    .052       02390.842    .046       0
2644.095    .036       02949.079    .052       03438.982    .052       0
3776.396    .052       0
Levee=-1,1639.754,796.0522,-1,1731.697,796.738,,
#XS Ineff= 6 ,-1
  640.08  807.72 797.052  929.64 1249.68796.4424 1325.88 1539.24795.8328
 1737.36 1874.52 795.528 1965.96 2148.84 795.528  2628.93860.557796.1376
Permanent Ineff=
       T       T       T       T       T       F
Bank Sta=1639.754,1731.697
XS Rating Curve= 0 ,0
Exp/Cntr=0.3,0.1

Type RM Length L Ch R = 1 ,46.90568,158.7511,143.1021,131.637
XS GIS Cut Line= 4
       556876.59      4833261.58        557465.4      4834540.75
       557473.32      4834790.63       557928.48      4836897.33
#Sta/Elev= 30
       0806.8431  97.625 812.243290.2699818.0259401.1799808.0111446.4811793.9659
453.1001801.8721 493.847797.5009797.7829796.05011036.126795.37011312.077794.1409
1379.511795.88011387.352 804.192 1478.39796.34921487.644794.56091515.101792.6921
1531.616792.2389 1557.05 793.2991577.642 795.7851580.062796.35352027.886 800.858
2043.651793.28992060.812793.81992364.748 795.2292533.304795.31012551.605795.4079
2763.639795.6789 2797.96794.75813272.741794.43293609.472794.36493812.768794.4631
#Mann= 19 ,-1 , 0
       0    .036       0  97.625    .052       0401.1799    .046       0
 493.847    .052       0797.7829    .036       01036.126    .052       0
1487.644    .082       01515.101    .037       0 1557.05    .082       0
1577.642    .052       02043.651    .026       02060.812    .052       0
2364.748    .052       02533.304    .046       02551.605    .046       0
2763.639    .052       0 2797.96    .052       03272.741    .036       0
3609.472    .052       0
Levee=-1,1478.39,796.3815,-1,1580.062,796.3937,,
#XS Ineff= 8 ,-1
  518.16  746.76796.4424  868.68 1036.32795.8328 1158.24 1386.84795.8328
 1584.96 1691.64 795.528 1798.32 2011.68795.2232 2011.68  2362.2 794.004
  2362.2 2499.36794.9184 2545.083812.768795.8328
Permanent Ineff=
       T       T       T       T       T       T       T       F
Bank Sta=1478.39,1580.062
XS Rating Curve= 0 ,0
Exp/Cntr=0.3,0.1

Type RM Length L Ch R = 1 ,46.81672,82.492,93.6449,100.4481
XS GIS Cut Line= 4
       556713.28       4833379.7       557285.08      4834566.18
       557366.71      4834796.68       557856.69      4836996.27
#Sta/Elev= 30
       0802.2351109.8749802.4689238.4441806.9461439.4999 796.864 1394.82795.8746
 1406.63793.76591436.007 792.1951458.168 792.0491472.632793.84491488.274 794.132
1500.655795.91751535.322 800.6811622.184 793.2921636.682794.18991729.423801.3838
1740.197 795.0151862.895800.39812049.858792.71282060.922792.93912264.267 794.182
2500.041 795.3222665.235797.94512691.521795.13782702.305803.67012708.546795.0708
2779.306794.47712882.696794.97383172.645794.02293510.662794.07713815.108793.8979
#Mann= 19 ,-1 , 0
       0    .026       0109.8749    .036       0238.4441    .046       0
439.4999    .052       0 1406.63    .082       01436.007    .037       0
1472.632    .082       01488.274    .052       01622.184    .026       0
1636.682    .052       02049.858    .026       02060.922    .052       0
2264.267    .052       02500.041    .046       02665.235    .052       0
2779.306    .036       02882.696    .052       03172.645    .036       0
3510.662    .052       0
Levee=-1,1394.82,795.9059,-1,1500.655,795.9426,,
#XS Ineff= 8 ,-1
   457.2  701.04796.1376  777.24   914.4795.8328 1005.84 1310.64795.2232
 1508.76  1600.2795.8328 1691.64 1935.48794.9184 2015.562085.436 794.004
 2270.76 2484.12794.6136 2484.123815.108795.8328
Permanent Ineff=
       T       T       T       T       T       T       T       F
Bank Sta=1394.82,1500.655
XS Rating Curve= 0 ,0
Exp/Cntr=0.3,0.1

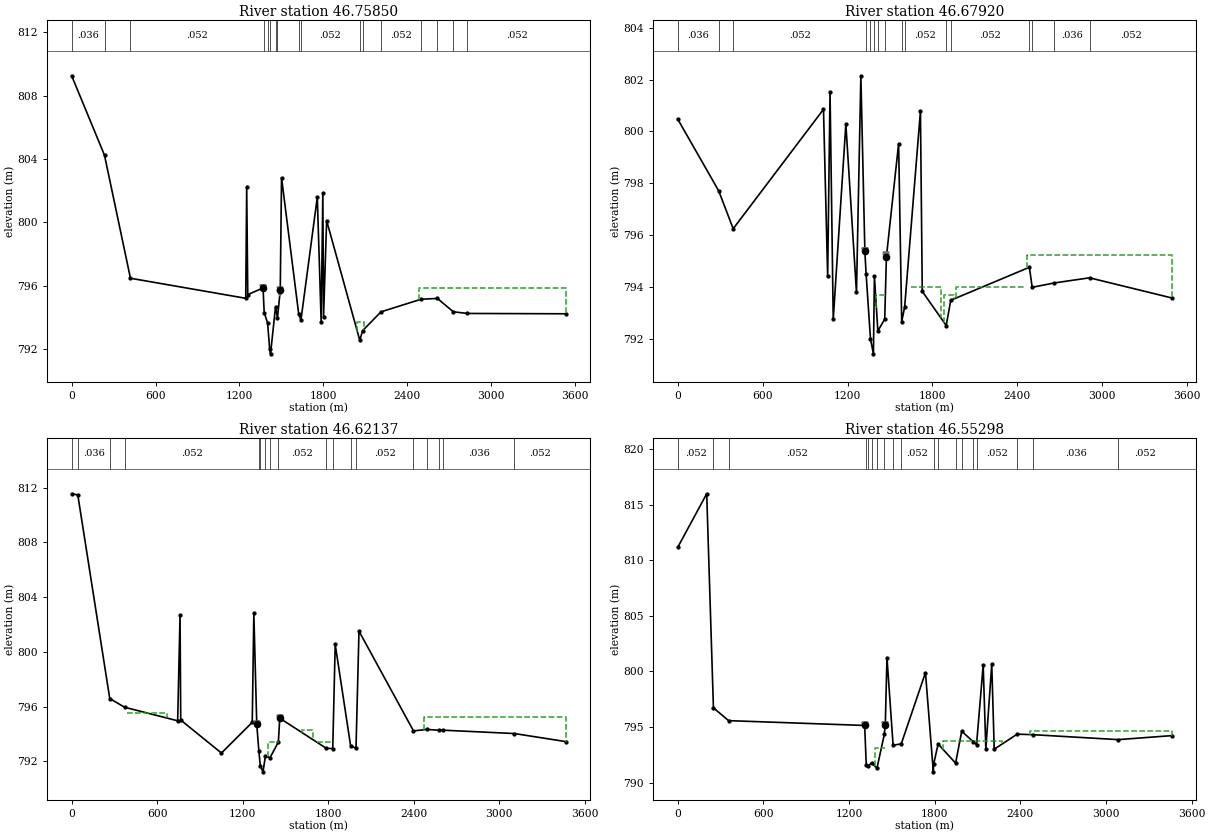
Type RM Length L Ch R = 1 ,46.75850,129.447,127.5539,124.1149
XS GIS Cut Line= 4
        556668.3      4833416.14       557218.53      4834578.33
       557263.26      4834856.01       557711.63      4836768.76
#Sta/Elev= 30
       0809.2519  234.86  804.23 420.275 796.4681244.703795.20181251.554 802.254
1259.213 795.4361368.543795.85281376.666794.29911401.035793.64591415.515 792.027
1422.031791.69511457.896794.68311471.669 793.9551491.505795.71561500.674802.8201
 1623.18794.23291639.426793.82511756.463801.58811784.047793.71591796.005801.8481
1801.145  794.051823.204800.10612060.054 792.5542080.538793.15912211.918794.3469
2498.694795.14312615.241 795.1932729.316794.34912830.323794.24513531.724794.2241
#Mann= 17 ,-1 , 0
       0    .036       0  234.86    .046       0 420.275    .052       0
1376.666    .057       01401.035    .082       01415.515    .037       0
1457.896    .082       01471.669    .052       0 1623.18    .026       0
1639.426    .052       02060.054    .026       02080.538    .052       0
2211.918    .052       02498.694    .046       02615.241    .052       0
2729.316    .036       02830.323    .052       0
Levee=-1,1368.543,795.8542,-1,1491.505,795.5616,,
#XS Ineff= 8 ,-1
  441.96   685.8795.8328  746.76  883.92 795.528  944.88 1280.16794.9184
 1493.52  1600.2 795.528 1691.64 1889.76794.61362043.7182087.484793.6992
  2209.8 2468.88794.3088 2484.123531.724795.8328
Permanent Ineff=
       T       T       T       T       T       T       T       F
Bank Sta=1368.543,1491.505
XS Rating Curve= 0 ,0
Exp/Cntr=0.3,0.1

Type RM Length L Ch R = 1 ,46.67920,94.7251,93.017,91.4601
BEGIN DESCRIPTION:
FEMA XS "AP"
PROJECT XS "AP"
END DESCRIPTION:
XS GIS Cut Line= 5
       556556.04      4833487.34       556852.08      4834103.72
       557079.15      4834576.49       557148.85      4834875.33
       557597.31      4836797.93
#Sta/Elev= 30
       0800.4801 289.963797.7039392.2011 796.2431030.142 800.8551059.592794.4039
1076.339 801.528 1098.97792.73691188.139800.28291263.163793.78391294.185 802.151
1322.521795.36591331.179 794.4991362.234791.98191382.921791.41021389.799 794.417
1414.225792.29281462.726792.75091474.631795.1525 1560.88799.53091582.759792.6541
1603.695 793.2251715.022 800.7831728.009793.82291897.148792.5041 1929.25793.4792
2484.751794.7541 2504.64793.97992659.915794.14782909.751794.34693489.329793.5709
#Mann= 16 ,-1 , 0
       0    .036       0 289.963    .046       0392.2011    .052       0
1331.179    .082       01362.234    .037       01389.799    .082       0
1414.225    .026       01462.726    .052       01582.759    .026       0
1603.695    .052       01897.148    .026       0 1929.25    .052       0
2484.751    .046       0 2504.64    .052       02659.915    .036       0
2909.751    .052       0
Levee=-1,1322.521,795.397,-1,1474.631,795.211,,
#XS Ineff= 10 ,-1
  411.48  655.32 795.528  716.28  807.72 795.528  868.68 1234.44795.2232
 1404.041469.535793.6992 1478.281560.354794.91841560.3541620.274793.6992
 1645.92 1859.28 794.0041883.929 1951.04793.6992 1965.96 2453.64 794.004
 2468.883489.329795.2232
Permanent Ineff=
       T       T       T       T       T       T       T       T       T       F
Bank Sta=1322.521,1474.631
XS Rating Curve= 0 ,0
Exp/Cntr=0.3,0.1

Type RM Length L Ch R = 1 ,46.62137,125.1871,110.006,85.4729
XS GIS Cut Line= 5
       556501.72      4833528.14       556785.37      4834154.26
       556994.05      4834642.04       557060.17      4834883.14
         557493.      4836833.29
#Sta/Elev= 30
       0811.5511 42.9719811.4691267.1901796.5939371.5039795.9599743.7089794.9711
760.4129802.6749765.2458795.02391050.849 792.6161267.093794.85721278.197 802.831
1298.744 794.7031313.433792.76891323.484791.68381342.584791.24191359.178792.3721
1392.101792.28311450.322793.41691459.943795.16051786.824  792.961831.876792.9409
1849.162 800.5491957.328793.14111995.102792.97112016.002801.51922398.489 794.232
2492.058 794.3392579.736794.27922604.341 794.2853106.494794.03913465.524793.4542
#Mann= 18 ,-1 , 0
       0    .052       0 42.9719    .036       0267.1901    .046       0
371.5039    .052       01313.433    .082       01323.484    .037       0
1359.178    .082       01392.101    .026       01450.322    .052       0
1786.824    .026       01831.876    .052       01957.328    .026       0
1995.102    .052       02398.489    .046       02492.058    .036       0
2579.736    .052       02604.341    .036       03106.494    .052       0
Levee=-1,1298.744,794.6959,-1,1459.943,795.0983,,
#XS Ineff= 7 ,-1
  388.62  670.56 795.5281377.385  1458.2793.3944 1463.04 1554.48794.3088
 1615.44 1691.64794.30881722.9731839.943793.3944 1874.52 2270.76 794.004
 2468.883465.524795.2232
Permanent Ineff=
       T       T       T       T       T       T       F
Bank Sta=1298.744,1459.943
XS Rating Curve= 0 ,0
Exp/Cntr=0.3,0.1

Type RM Length L Ch R = 1 ,46.55298,126.357,118.6519,106.637
XS GIS Cut Line= 6
       556421.43      4833571.98       556760.52      4834537.06
       556863.58      4834712.17       556982.02      4834893.18
       557052.25      4835013.53       557453.86      4836847.62
#Sta/Elev= 30
       0811.1441203.2821  815.97250.4538796.7189357.0009795.56791309.665795.1347
1320.766 791.6111332.874791.49211359.511791.77721395.488791.27211447.377794.3311
1454.228795.20021465.827801.23911508.953793.35511566.032  793.48 1735.52799.8839
1790.614790.96391792.617 791.6361824.097793.46611946.557791.74691989.452794.6121
2070.746 793.6652093.231793.40912139.881800.55912158.299 793.0392199.815 800.642
2217.194793.00212377.933 794.3532491.053794.30393085.362793.86133459.315794.2189
#Mann= 19 ,-1 , 0
       0    .052       0250.4538    .046       0357.0009    .052       0
1320.766    .082       01332.874    .037       01359.511    .082       0
1395.488    .026       01447.377    .052       01508.953    .026       0
1566.032    .052       01792.617    .026       01824.097    .052       0
1946.557    .026       01989.452    .052       02070.746    .036       0
2093.231    .052       02377.933    .046       02491.053    .036       0
3085.362    .052       0
Levee=-1,1309.665,795.1287,-1,1454.228,795.2018,,
#XS Ineff= 7 ,-1
  365.76  655.32795.22321381.3351449.592793.0896 1463.04 1539.24793.3944
 1615.44 1737.36793.69921755.6851825.347793.0896 1859.28 2270.76793.6992
 2468.883459.315794.6136
Permanent Ineff=
       T       T       T       T       T       T       F
Bank Sta=1309.665,1454.228
XS Rating Curve= 0 ,0
Exp/Cntr=0.3,0.1