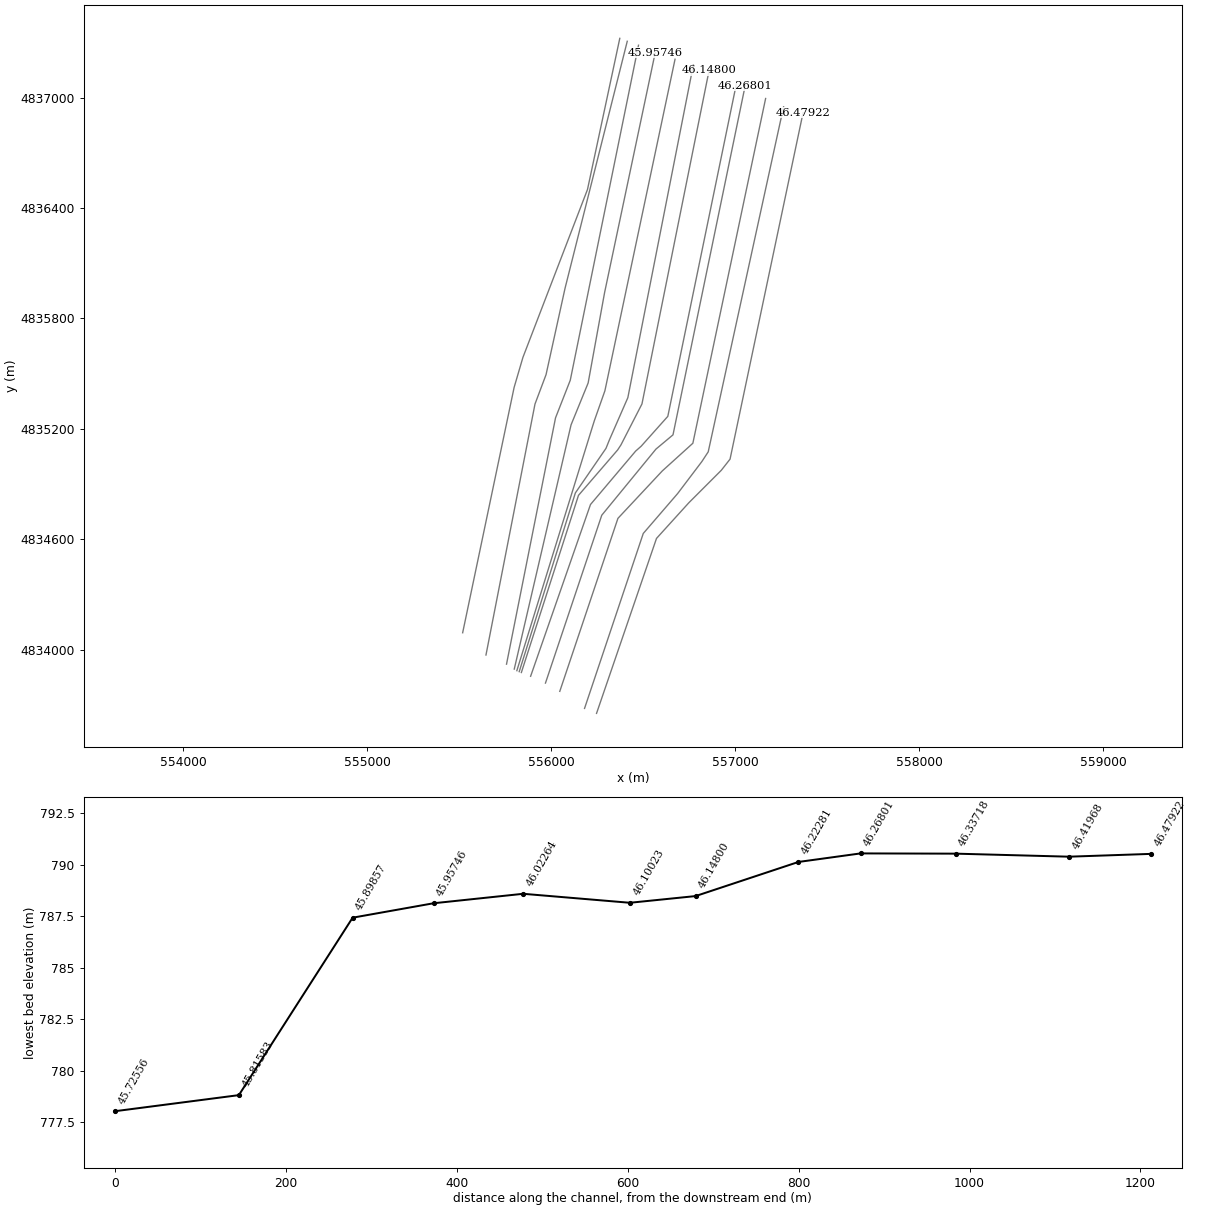
HEC-RAS study Boise2.prj: BoiseRiver_All_reaches

--- Boise2.g01 (geometry) --- (continued)

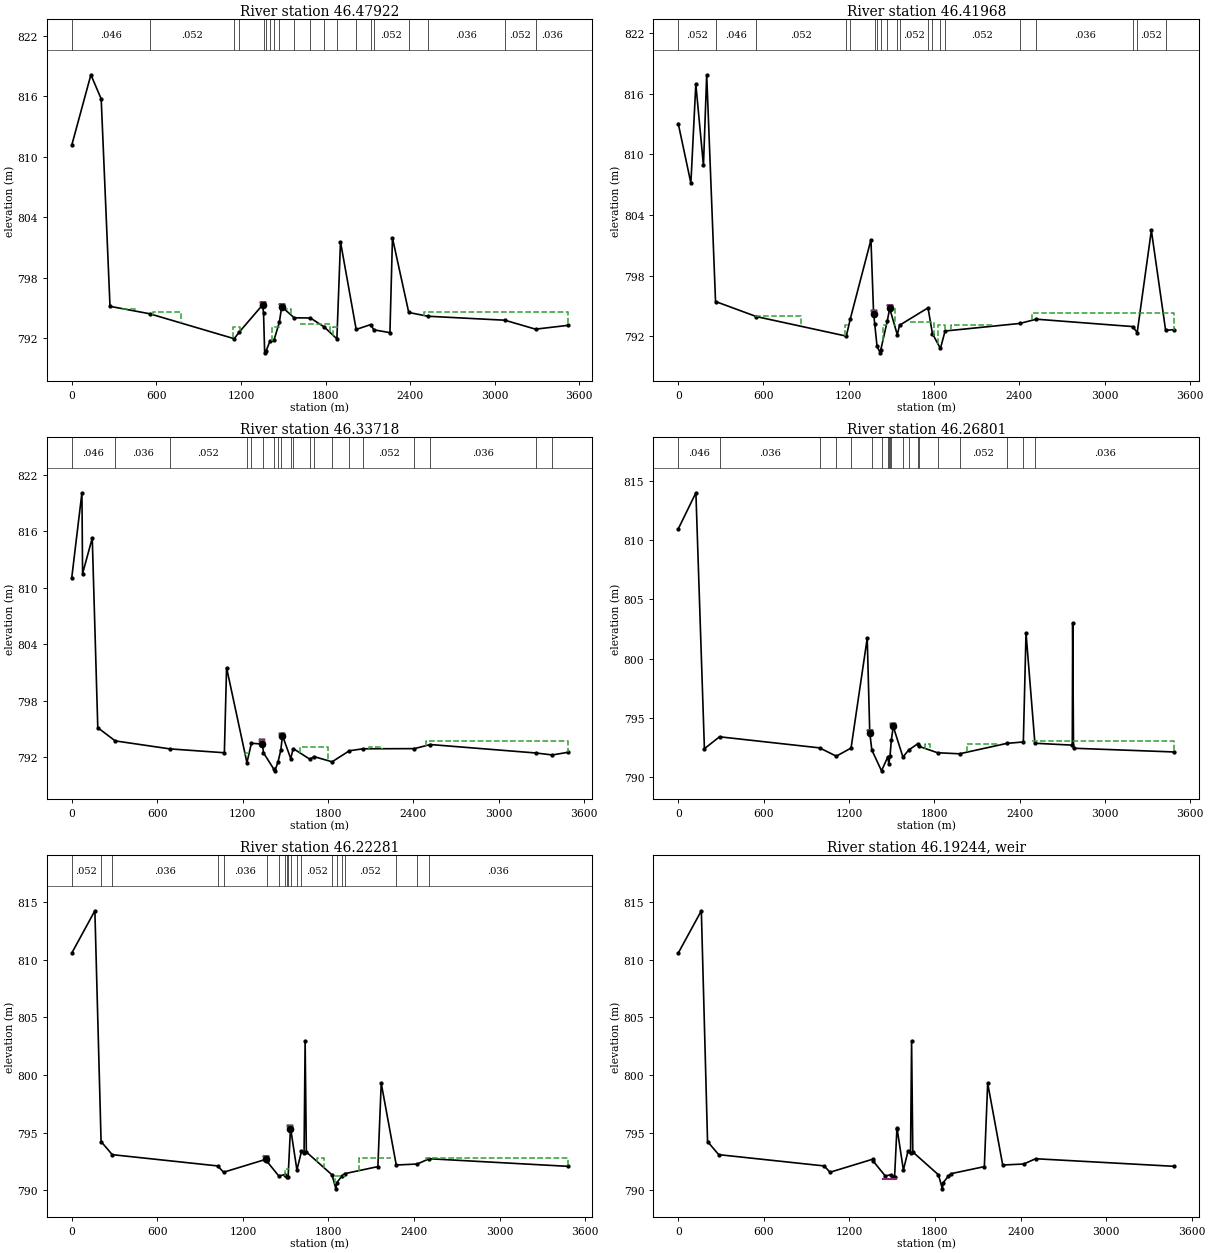
Type RM Length L Ch R = 1 ,46.47922,90.617,95.7611,104.276
XS GIS Cut Line= 6
       556246.88      4833653.14       556572.73      4834603.97
       556748.26      4834797.52       556925.01      4834974.33
        556972.5      4835034.92       557369.36      4836917.55
#Sta/Elev= 30
       0811.1459135.5961 818.135208.6469 815.738271.1601 795.137552.9331794.3981
1151.944791.92191189.581 792.6081353.071 795.2741360.174 794.4881368.118790.5189
1378.816 790.7361406.252791.68211434.039791.76311472.379793.5651 1488.82795.1087
1577.197794.00011692.567 793.9791788.943793.10911880.396791.9061 1905.99 801.542
2017.222792.84092118.875793.32012142.793 792.8042256.631792.52392274.572801.9239
2390.168794.52892524.078794.15523071.735 793.759 3289.46792.87023517.389 793.246
#Mann= 20 ,-1 , 0
       0    .046       0552.9331    .052       01151.944    .026       0
1189.581    .052       01360.174    .082       01378.816    .037       0
1406.252    .082       01434.039    .026       01472.379    .052       0
1577.197    .052       01692.567    .036       01788.943    .052       0
1880.396    .052       02017.222    .052       02118.875    .036       0
2142.793    .052       02390.168    .046       02524.078    .036       0
3071.735    .052       0 3289.46    .036       0
Levee=-1,1353.071,795.2902,-1,1488.82,795.1104,,
#XS Ineff= 9 ,-1
  358.14   457.2794.9184  579.12  777.24794.61361143.622 1194.67793.0896
1422.3431473.382793.0896 1493.52 1554.48794.9184 1615.44  1828.8793.3944
1855.9121890.641793.0896    1905    2286793.3944 2499.363517.389794.6136
Permanent Ineff=
       T       T       T       T       T       T       T       T       F
Bank Sta=1353.071,1488.82
XS Rating Curve= 0 ,0
Exp/Cntr=0.3,0.1

Type RM Length L Ch R = 1 ,46.41968,137.1691,132.7099,118.5072
XS GIS Cut Line= 6
       556181.69      4833680.11       556500.81      4834630.95
       556687.51      4834847.67       556819.26      4835021.68
       556853.91      4835074.57       557263.43      4836949.77
#Sta/Elev= 30
       0813.0461 88.9949807.1631123.7171816.9591177.3631 808.903200.2771817.8702
262.4401795.4561550.0079793.96711182.726792.03591210.296793.71111356.216801.5579
1374.834794.26181382.697793.25421399.099 791.017 1421.16 790.3831424.572 790.629
 1471.34793.5389 1487.96 794.7771541.836792.16391557.191 793.106 1757.86  794.83
 1788.92792.27391845.108 790.8131877.913 792.541 2403.84793.28892520.402793.7092
3198.138792.97893229.899792.38613329.529802.48693429.869 792.6123489.896792.6738
#Mann= 20 ,-1 , 0
       0    .052       0262.4401    .046       0550.0079    .052       0
1182.726    .026       01210.296    .052       01382.697    .082       0
1399.099    .037       01424.572    .082       0 1471.34    .052       0
1541.836    .026       01557.191    .052       0 1757.86    .026       0
 1788.92    .052       01845.108    .026       01877.913    .052       0
 2403.84    .046       02520.402    .036       03198.138    .052       0
3229.899    .052       03429.869    .036       0
Levee=-1,1374.834,794.2905,-1,1487.96,794.7904,,
#XS Ineff= 8 ,-1
  548.64  861.06 794.0041172.1051210.144793.08961440.1591471.821793.0896
 1493.52    1524 794.827 1630.68 1798.32793.39441826.4681879.244793.0896
 1920.24 2225.04793.0896 2491.743489.896794.3088
Permanent Ineff=
       T       T       T       T       T       F       T       F
Bank Sta=1374.834,1487.96
XS Rating Curve= 0 ,0
Exp/Cntr=0.3,0.1

Type RM Length L Ch R = 1 ,46.33718,105.7891,111.2551,108.3381
XS GIS Cut Line= 5
       556047.11      4833772.81       556363.14      4834713.04
       556604.21      4834970.79       556770.36      4835121.22
       557165.89      4836995.04
#Sta/Elev= 30
       0811.0969  71.354 820.119  75.904811.5142   143.9815.3062182.7809 795.118
305.2051793.7169  689.15792.86621072.079 792.4551087.546 801.5071230.574791.3979
1261.931793.46511339.892793.37791346.594792.45811418.366 790.738 1426.99790.5302
1449.723791.51991468.537 792.7331480.368794.28751538.218791.83511555.639792.9009
1671.658791.77811703.712792.0389 1828.79  791.491950.384 792.6662045.847 792.876
2407.146792.89392518.636793.32893258.306 792.4333376.065792.22093484.074792.4971
#Mann= 20 ,-1 , 0
       0    .046       0305.2051    .036       0  689.15    .052       0
1230.574    .026       01261.931    .052       01346.594    .082       0
1418.366    .037       01449.723    .082       01468.537    .052       0
1538.218    .026       01555.639    .052       01671.658    .026       0
1703.712    .052       0 1828.79    .052       01950.384    .036       0
2045.847    .052       02407.146    .046       02518.636    .036       0
3258.306    .052       03376.065    .036       0
Levee=-1,1339.892,793.5925,-1,1480.368,794.1198,,
#XS Ineff= 4 ,-1
1219.0751260.479  792.48  1600.2 1798.32793.0896 2087.88 2179.32793.0896
 2491.743484.074793.6992
Permanent Ineff=
       T       T       T       F
Bank Sta=1339.892,1480.368
XS Rating Curve= 0 ,0
Exp/Cntr=0.3,0.1

Type RM Length L Ch R = 1 ,46.26801,76.4609,72.7131,79.2892
BEGIN DESCRIPTION:
FEMA XS "AO"
PROJECT XS "AO"
END DESCRIPTION:
XS GIS Cut Line= 5
        555969.3      4833817.85       556275.25      4834730.01
       556569.95       4835089.6       556662.43      4835166.89
       557054.96      4837065.53
#Sta/Elev= 30
       0810.9368 124.177 813.987183.9489792.4069290.0641 793.413993.9589792.4778
  1111.1791.77891214.994 792.4621328.642 801.7271346.439793.75121361.072792.2999
1429.055790.54211472.635 791.7011480.653791.14891489.021 791.8171498.085793.1381
1511.503794.28181579.666791.70211620.456 792.3021682.164792.80491694.018 792.601
1822.665792.06881977.807791.97892310.405792.85882426.152792.97592444.884802.1669
2507.384792.86712770.264792.70892772.893802.99712779.039 792.4483486.351792.1332
#Mann= 20 ,-1 , 0
       0    .046       0290.0641    .036       0993.9589    .052       0
  1111.1    .036       01214.994    .052       01361.072    .082       0
1429.055    .037       01472.635    .057       01480.653    .026       0
1489.021    .082       01498.085    .052       01579.666    .026       0
1620.456    .052       01682.164    .026       01694.018    .052       0
1822.665    .052       01977.807    .052       02310.405    .036       0
2426.152    .046       02507.384    .036       0
Levee=-1,1346.439,793.7267,-1,1511.503,794.257,,
#XS Ineff= 7 ,-1
1473.7841487.567791.56561571.9851591.769791.56561680.2251693.414791.5656
 1737.36 1767.84792.78481779.5411814.459791.5656 2026.92 2255.52792.7848
 2484.123486.351793.0896
Permanent Ineff=
       T       T       T       F       F       F       T
Bank Sta=1346.439,1511.503
XS Rating Curve= 0 ,0
Exp/Cntr=0.3,0.1

Type RM Length L Ch R = 1 ,46.22281,92.0331,120.3271,136.306
XS GIS Cut Line= 6
       555888.57      4833854.71       556213.98      4834788.23
       556459.58      4835078.79       556489.51      4835105.17
       556634.29      4835267.48        557008.1      4837080.06
#Sta/Elev= 30
       0810.5602161.9329814.2269205.5081794.2281283.7481793.08991023.022 792.113
1064.402791.56591363.544792.69521367.275 792.5271451.773791.24011491.762791.3559
1507.062791.10991517.146791.19321533.281795.31491534.185795.40091578.694791.7579
1610.678  793.371628.832793.21521636.268802.94021644.771793.32091824.887791.3392
1851.952 790.1271858.269790.66311892.695791.20381912.515  791.442146.382 792.053
2169.838799.28192275.198792.19292422.288 792.2772506.091792.73613477.302792.0789
#Mann= 20 ,-1 , 0
       0    .052       0205.5081    .046       0283.7481    .036       0
1023.022    .052       01064.402    .036       01367.275    .082       0
1451.773    .037       01491.762    .057       01507.062    .026       0
1517.146    .082       01534.185    .052       01578.694    .026       0
1610.678    .052       01824.887    .026       01858.269    .052       0
1892.695    .026       01912.515    .052       02275.198    .036       0
2422.288    .046       02506.091    .036       0
Levee=-1,1363.544,792.6964,-1,1533.281,795.4,,
#XS Ineff= 5 ,-1
1497.1841521.043791.8704 1722.12 1767.84792.78481842.2931913.278791.2608
 2011.68 2240.28792.7848 2484.123477.302792.7848
Permanent Ineff=
       T       T       T       F       T
Bank Sta=1363.544,1533.281
XS Rating Curve= 0 ,0
Exp/Cntr=0.5,0.3

Type RM Length L Ch R = 5 ,46.19244,,,
BEGIN DESCRIPTION:
Little Dry Creek Diversion Structure RM 46.19
END DESCRIPTION:
IW Pilot Flow=0
#Inline Weir SE= 2
 1432.56 790.956    1524 790.956
IW Dist,WD,Coef,Skew,MaxSub,Min_El,Is_Ogee,SpillHt,DesHd
39.624,4.572,1.88,0,0.98,, 0 ,,,1,1,

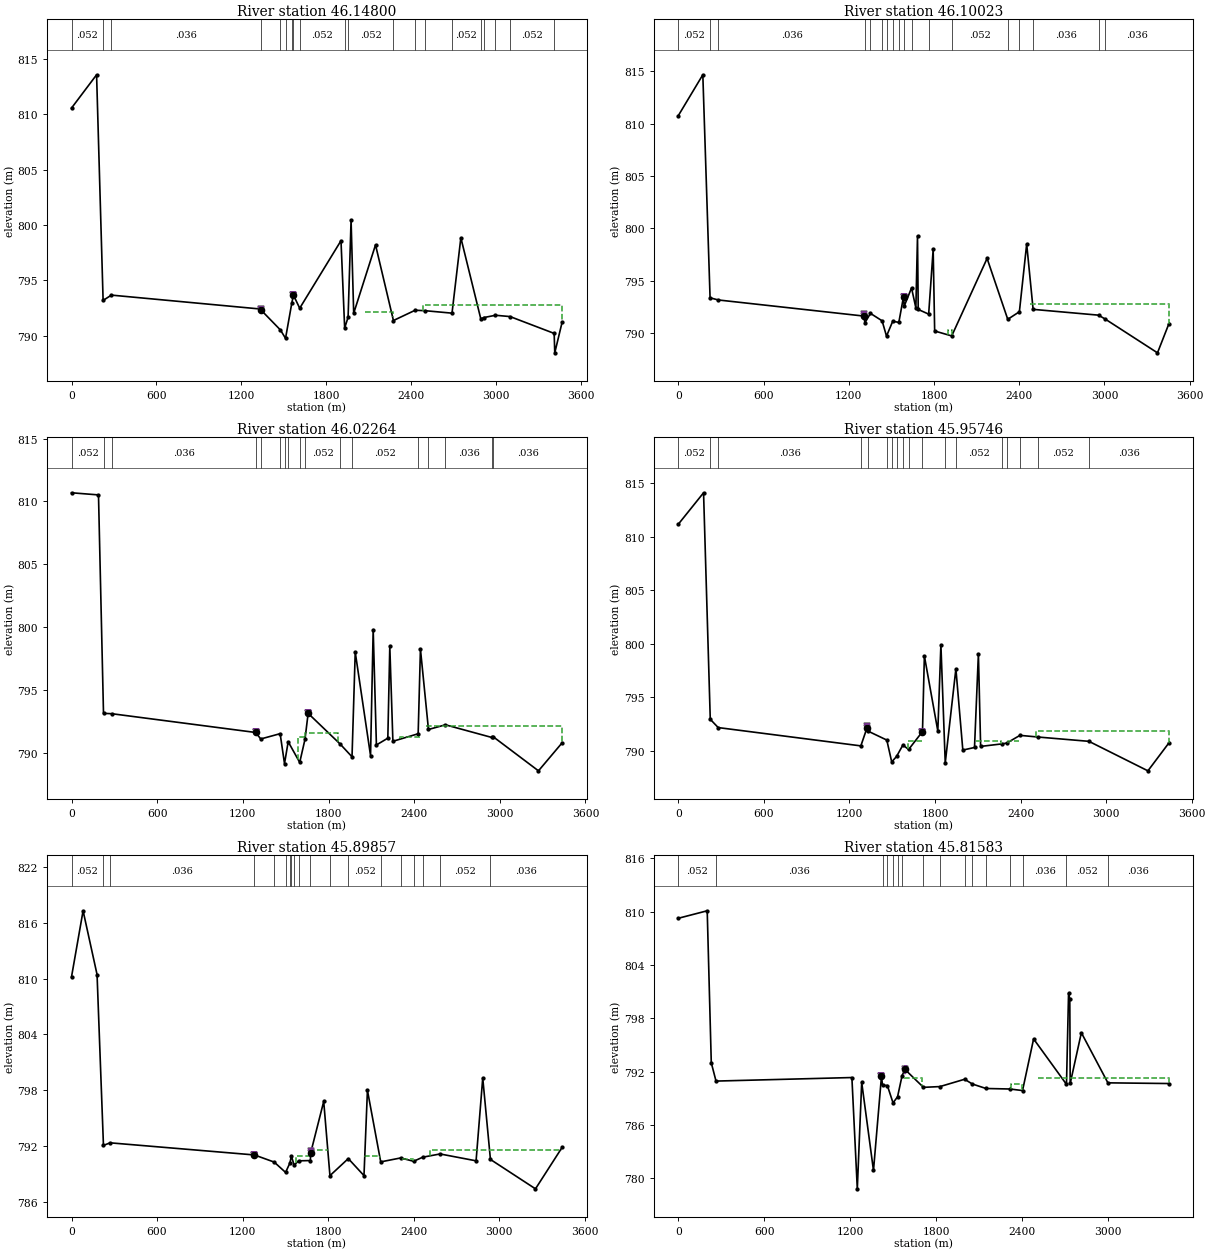
Type RM Length L Ch R = 1 ,46.14800,70.0369,76.845,81.5971
XS GIS Cut Line= 6
       555838.32      4833875.25       556148.77       4834838.1
       556361.41      4835084.62       556379.65      4835112.43
       556493.75      4835334.88       556858.59      4837147.46
#Sta/Elev= 30
       0810.5659177.2811813.5701223.4321793.2009282.0659793.68091338.858792.4221
 1338.98792.34831477.288790.5339 1513.37789.77891557.432792.94211569.229 793.702
1569.372793.67361613.637 792.4981905.512 798.5931931.438 790.7181955.724791.6768
1976.799800.44811995.355792.0429 2149.65798.21512276.301 791.3872429.997792.3151
2502.161792.27182690.552792.05212753.077 798.8582894.208 791.5322914.331791.6519
2997.945791.86183100.986791.74393412.891790.22383417.064  788.473469.441791.2541
#Mann= 20 ,-1 , 0
       0    .052       0223.4321    .046       0282.0659    .036       0
1338.858    .082       01477.288    .037       0 1513.37    .082       0
1557.432    .057       01569.229    .082       01613.637    .052       0
1931.438    .026       01955.724    .052       02276.301    .036       0
2429.997    .046       02502.161    .036       02690.552    .052       0
2894.208    .036       02914.331    .052       02997.945    .036       0
3100.986    .052       03412.891    .036       0
Levee=-1,1338.98,792.4282,-1,1569.372,793.7023,,
#XS Ineff= 4 ,-1
 1615.44 1889.76  792.481929.3141952.116790.6512 2072.64 2270.76792.1752
 2484.123469.441792.7848
Permanent Ineff=
       T       T       F       F
Bank Sta=1338.98,1569.372
XS Rating Curve= 0 ,0
Exp/Cntr=0.5,0.3

Type RM Length L Ch R = 1 ,46.10023,114.7761,124.8071,136.6211
XS GIS Cut Line= 6
       555826.66      4833880.01        556131.8      4834851.22
        556298.2      4835093.42       556316.92      4835139.89
       556417.04      4835368.97       556772.76      4837176.39
#Sta/Elev= 30
       0810.7439172.7991814.6429223.8241 793.388281.8519793.18291304.663791.6518
1314.272791.01911352.958791.90391434.819791.19711465.906789.73621509.773791.1611
1552.603791.04411585.765 793.5061590.252 792.5871642.063794.33011672.578792.4221
1684.049799.28311689.192792.2809 1762.61791.83291794.351797.99691804.863 790.226
1924.951789.75692173.968 797.1412319.406  791.342401.267792.05972452.652798.5151
2497.981 792.2882958.407 791.7363005.038791.36683373.523788.14513454.067790.9271
#Mann= 18 ,-1 , 0
       0    .052       0223.8241    .046       0281.8519    .036       0
1314.272    .082       01352.958    .057       01434.819    .082       0
1465.906    .037       01509.773    .082       01552.603    .057       0
1590.252    .082       01642.063    .052       0 1762.61    .082       0
1924.951    .052       02319.406    .036       02401.267    .046       0
2497.981    .036       02958.407    .052       03005.038    .036       0
Levee=-1,1304.663,791.8064,-1,1585.765,793.4919,,
#XS Ineff= 4 ,-1
  1638.3 1798.32792.17521899.8031926.193790.3464 2026.92 2263.14791.8704
  2476.53454.067792.7848
Permanent Ineff=
       T       T       F       F
Bank Sta=1304.663,1585.765
XS Rating Curve= 0 ,0
Exp/Cntr=0.3,0.1

Type RM Length L Ch R = 1 ,46.02264,113.88,104.8259,104.3071
XS GIS Cut Line= 5
       555813.81      4833885.26       556221.38      4835200.53
       556234.95      4835243.67       556292.26      4835406.17
       556673.57      4837208.35
#Sta/Elev= 30
       0 810.693188.9751810.5239224.0649793.1521 281.456793.12491289.392791.6318
1289.404791.63391325.488791.11511461.232791.53611491.818789.15581517.598790.8951
1598.352 789.2511635.123791.08011657.356793.15251882.213 790.7041964.691789.6968
1987.212798.02012094.439789.79192112.956799.81292135.523790.63812215.503791.1791
2229.302798.48092250.991790.93012427.941  791.53 2443.92 798.262 2500.11 791.871
2619.015 792.2412944.459 791.2332955.112791.27783270.586 788.5813436.577 790.813
#Mann= 17 ,-1 , 0
       0    .052       0224.0649    .046       0 281.456    .036       0
1289.404    .082       01325.488    .057       01461.232    .082       0
1491.818    .037       01517.598    .082       01598.352    .026       0
1635.123    .052       01882.213    .082       01964.691    .052       0
2427.941    .046       0 2500.11    .052       02619.015    .036       0
2944.459    .052       02955.112    .036       0
Levee=-1,1289.392,791.6418,-1,1657.356,793.1597,,
#XS Ineff= 6 ,-1
1587.7821637.602791.26081637.602  1866.9791.56561882.6251969.407790.3464
 2103.12 2240.28791.2608 2301.24 2453.64791.2608 2484.123436.577792.1752
Permanent Ineff=
       T       T       T       T       T       F
Bank Sta=1289.392,1657.356
XS Rating Curve= 0 ,0
Exp/Cntr=0.3,0.1

Type RM Length L Ch R = 1 ,45.95746,93.5529,94.73,98.4501
XS GIS Cut Line= 5
       555799.69      4833893.87       556108.35      4835221.06
       556201.29      4835448.88       556290.82      4835940.95
       556565.82      4837244.05
#Sta/Elev= 30
       0811.1719177.2519814.1141 224.327792.9391280.0649792.16521280.249790.4549
1322.435792.10211327.041791.85791462.257 790.9981496.663 788.9551530.725 789.467
1574.765 790.5291615.364 790.1231709.428 791.7391712.389791.71711725.698798.8649
1819.984 791.8471841.585799.91281872.033788.86111946.694 797.6571995.326790.0629
2077.258790.30412104.548 799.0712120.216790.4049 2266.67790.63682302.453 790.713
2396.037791.43912522.651791.28222879.442790.8801 3293.27788.12193440.604790.7341
#Mann= 18 ,-1 , 0
       0    .052       0 224.327    .046       0280.0649    .036       0
1280.249    .082       01327.041    .057       01462.257    .082       0
1496.663    .037       01530.725    .082       01574.765    .057       0
1615.364    .026       01712.389    .052       01872.033    .082       0
1946.694    .052       0 2266.67    .036       02302.453    .052       0
2396.037    .046       02522.651    .052       02879.442    .036       0
Levee=-1,1322.435,792.3,-1,1709.428,791.7728,,
#XS Ineff= 6 ,-1
1608.5971713.573 790.9561713.573 1859.28791.26081861.2151926.177790.0416
 2087.88 2263.14 790.956 2308.86 2392.68 790.956 2506.983440.604791.8704
Permanent Ineff=
       T       T       T       T       T       F
Bank Sta=1322.435,1709.428
XS Rating Curve= 0 ,0
Exp/Cntr=0.3,0.1

Type RM Length L Ch R = 1 ,45.89857,132.378,133.0909,136.743
BEGIN DESCRIPTION:
FEMA XS "AN"
PROJECT XS "AN"
END DESCRIPTION:
XS GIS Cut Line= 6
       555757.62      4833920.64       555941.89      4834846.65
       556024.02      4835259.38       556104.08      4835463.67
       556203.47      4835951.62       556474.94      4837284.49
#Sta/Elev= 30
       0810.1721 81.2021  817.27179.2401810.4229 224.113 792.084270.9331792.3599
 1283.33791.05911283.402 791.0591422.139 790.2931502.007789.18511532.302790.1918
 1542.63 790.9391561.908789.96991593.236790.42681675.858790.45791677.708791.2585
1769.524   796.81813.218 788.8371941.972790.66712052.085 788.8412076.303 797.999
2169.528790.31412308.953 790.7362400.526 790.379 2463.87 790.8172586.082791.1651
 2838.57790.42812885.315 799.3212939.293790.57713255.377 787.4213442.603 791.879
#Mann= 19 ,-1 , 0
       0    .052       0 224.113    .046       0270.9331    .036       0
1283.402    .057       01422.139    .082       01502.007    .037       0
1532.302    .082       0 1542.63    .057       01561.908    .082       0
1593.236    .026       01675.858    .052       01813.218    .082       0
1941.972    .052       02169.528    .036       02308.953    .052       0
2400.526    .046       0 2463.87    .036       02586.082    .052       0
2939.293    .036       0
Levee=-1,1283.33,791.0657,-1,1677.708,791.4589,,
#XS Ineff= 6 ,-1
 1574.421680.329 790.9561680.329 1798.32791.56561804.6321898.355789.7368
  2057.4 2164.08 790.956 2316.48 2392.68790.6512  2514.63442.603791.5656
Permanent Ineff=
       T       T       T       T       T       F
Bank Sta=1283.33,1677.708
XS Rating Curve= 0 ,0
Exp/Cntr=0.3,0.1

Type RM Length L Ch R = 1 ,45.81583,134.3851,145.2,149.961
XS GIS Cut Line= 5
       555645.96      4833970.39       555912.39      4835334.42
       555972.53       4835494.3       556075.96      4835964.63
       556413.83      4837306.01
#Sta/Elev= 30
       0809.2681201.9711 810.113230.4239792.9979263.4179 790.9381212.049 791.337
1249.843778.80521280.558 790.7931362.789780.8729 1418.57791.4625 1426.02790.4549
 1459.59790.43991499.325788.4819 1530.84789.16721562.696791.56291582.476792.2477
1711.704 790.2331826.457790.3181  1999.1791.1431 2052.88790.60912148.108790.1041
2315.271790.04582403.305  789.872480.617795.68492710.227790.56892724.667 800.805
2733.281800.19512736.199790.67012814.005796.38292999.336790.73993425.464790.6619
#Mann= 16 ,-1 , 0
       0    .052       0263.4179    .036       0 1426.02    .057       0
 1459.59    .082       01499.325    .037       0 1530.84    .082       0
1562.696    .052       01711.704    .082       01826.457    .036       0
  1999.1    .052       0 2052.88    .052       02148.108    .036       0
2315.271    .052       02403.305    .036       02710.227    .052       0
2999.336    .036       0
Levee=-1,1418.57,791.4833,-1,1582.476,792.1021,,
#XS Ineff= 5 ,-1
1208.8731418.158790.65121572.768 1699.26791.26081712.5461761.269790.0416
2325.624  2400.3790.6512  2514.63425.464791.2608
Permanent Ineff=
       T       T       T       T       F
Bank Sta=1418.57,1582.476
XS Rating Curve= 0 ,0
Exp/Cntr=0.3,0.1

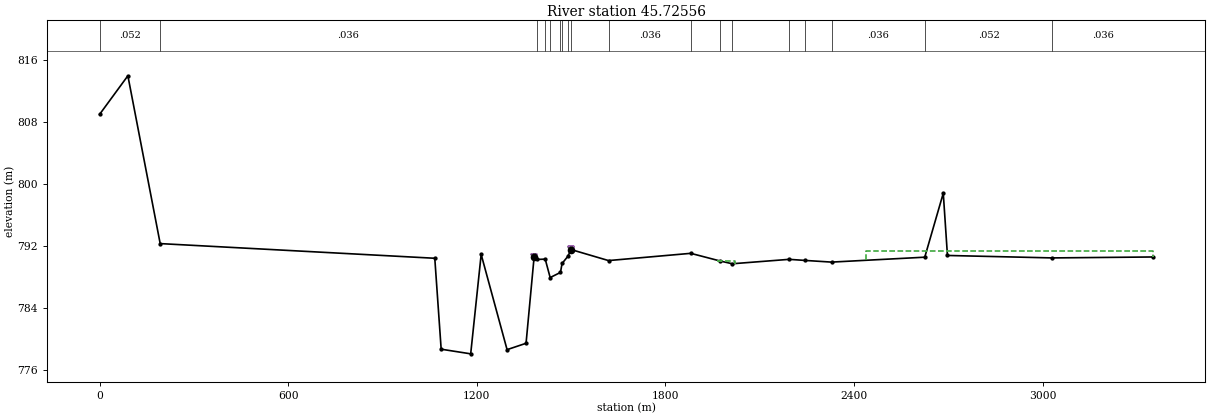
Type RM Length L Ch R = 1 ,45.72556,143.4261,41.1181,71.4841
XS GIS Cut Line= 5
       555519.24      4834091.27       555798.94      4835424.67
       555846.69      4835587.67       556197.75      4836500.59
       556373.27      4837321.98
#Sta/Elev= 30
       0 808.945 89.8599  813.92192.6421792.25421066.227790.36111086.511 778.621
1180.436778.02311213.765790.8561 1296.17778.56321356.573779.38611382.219790.5435
1390.705 790.2091417.507790.25011433.254787.86991466.087788.53591471.112789.6859
1489.204790.59481499.951791.4667 1500.93791.4711 1618.86790.06381880.517 790.998
1974.326 790.0052012.519789.65112193.435 790.2222243.019790.08522328.451 789.866
2624.952   790.52683.845798.75892697.131790.72313030.672 790.4073350.291 790.528
#Mann= 18 ,-1 , 0
       0    .052       0192.6421    .036       01390.705    .057       0
1417.507    .082       01433.254    .037       01466.087    .057       0
1471.112    .082       01489.204    .057       0 1500.93    .082       0
 1618.86    .036       01880.517    .052       01974.326    .026       0
2012.519    .052       02193.435    .036       02243.019    .052       0
2328.451    .036       02624.952    .052       03030.672    .036       0
Levee=-1,1382.219,790.5689,-1,1499.951,791.5138,,
#XS Ineff= 4 ,-1
1062.1091382.643790.34641764.7861809.125790.04161962.5162022.449790.0416
  2438.43350.291791.2608
Permanent Ineff=
       T       T       T       F
Bank Sta=1382.219,1499.951
XS Rating Curve= 0 ,0
Exp/Cntr=0.3,0.1

Chan Stop Cuts=-1
Use User Specified Reach Order=0